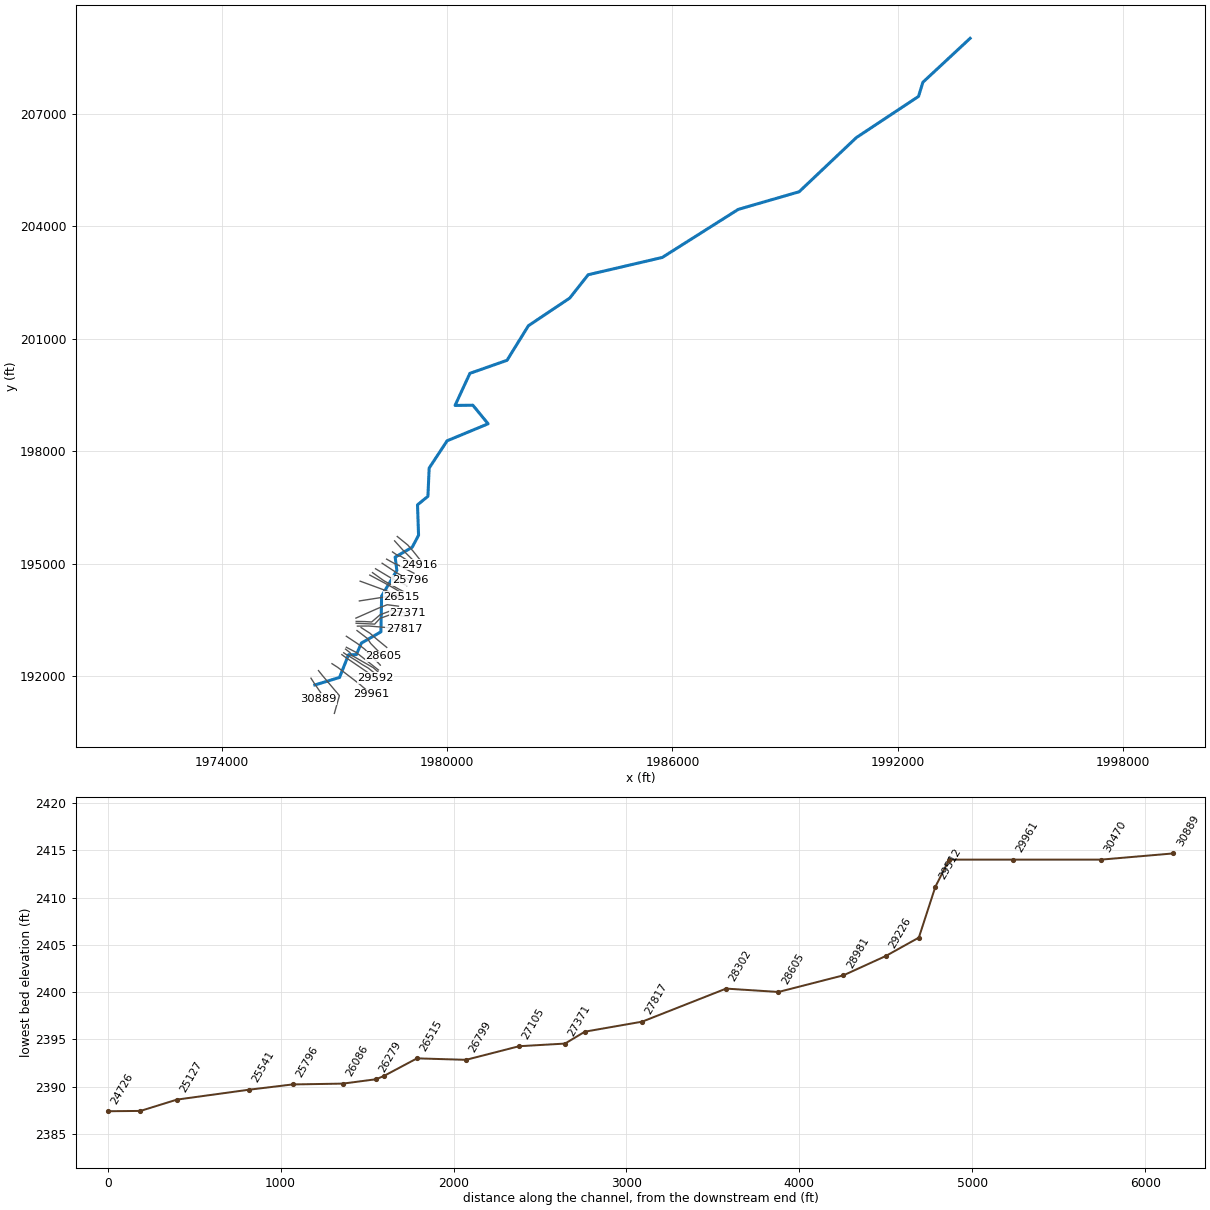
--- PIPESTCK2_A.prj (project) ---

Proj Title=PIPESTCK2_A
Current Plan=p01
Default Exp/Contr=0,0
English Units
Geom File=g01
Flow File=f01
Plan File=p01
Background Map Layer=Inundation Boundary (01pct Value_0)
BEGIN DESCRIPTION:
Stream Name: Pipestem Creek
Flood Zone: Approximate
Summers County, West Virginia
HEC-RAS Version: 5.0.7
Hydrology Method:
Regression.
Model Notes:
Known WSEL from Pipestem_AE creek
END DESCRIPTION:
DSS File=dss
DSS Export Rating Curves= 0
DSS Export Rating Curve Sorted= 0
DSS Export Volume Flow Curves= 0
DXF OffsetX= 0
DXF OffsetY= 0
DXF ScaleX= 0
DXF ScaleY= 0

--- PIPESTCK2_A.p01 (plan) ---

Plan Title=Floodplain
Program Version=5.07
Short Identifier=Floodplain
Geom File=g01
Flow File=f01
Subcritical Flow
K Sum by GR= 0
Std Step Tol= 0.01
Critical Tol= 0.01
Num of Std Step Trials= 20
Max Error Tol= 0.3
Flow Tol Ratio= 0.001
Split Flow NTrial= 30
Split Flow Tol= 0.02
Split Flow Ratio= 0.02
Log Output Level= 0
Friction Slope Method= 1
Unsteady Friction Slope Method= 2
Unsteady Bridges Friction Slope Method= 1
Parabolic Critical Depth
Global Vel Dist= 0 , 0 , 0
Global Log Level= 0
CheckData=True
Encroach Param=-1 ,0,0, 0
Computation Interval=0.1SEC
Output Interval=1MIN
Instantaneous Interval=Max Profile
Mapping Interval=1HOUR
Computation Time Step Use Courant=        0
Computation Time Step Use Time Series=    0
Computation Time Step Count To Double=0
Computation Time Step Max Doubling=0
Computation Time Step Max Halving=0
Computation Time Step Residence Courant=0
Run HTab= 0
Run UNet= 0
Run Sediment= 0
Run PostProcess= 0
Run WQNet= 0
Run RASMapper= 0
UNET Theta= 0
UNET Theta Warmup= 0
UNET ZTol= 0
UNET ZSATol= 0
UNET MxIter= 0
UNET Max Iter WO Improvement= 0
UNET MaxInSteps= 0
UNET DtIC= 0
UNET DtMin= 0
UNET MaxCRTS= 0
UNET WFStab= 0
UNET SFStab= 0
UNET WFX= 1
UNET SFX= 1
UNET 1D Methodology=Finite Difference
UNET DSS MLevel= 1
UNET Pardiso=0
UNET DZMax Abort= 0
UNET Use Existing IB Tables= 0
UNET Froude Reduction=False
UNET Froude Limit= 0
UNET Froude Power= 0
UNET D1 Cores= 0
UNET D2 Coriolis=0
UNET D2 Cores= 0
UNET D2 Theta= 1
UNET D2 Theta Warmup= 1
UNET D2 Z Tol= 0.01
UNET D2 Volume Tol= 0.01
UNET D2 Max Iterations= 20
UNET D2 Equation= 0
UNET D2 RampUpFraction=0.1
UNET D2 TimeSlices= 1
UNET D2 Eddy Viscosity=0.3
UNET D2 BCVolumeCheck=0
UNET D1D2 MaxIter= 0
UNET D1D2 ZTol=0.01
UNET D1D2 QTol=0.1
UNET D1D2 MinQTol=1
DSS File=dss
Write IC File= 0
Write IC File at Fixed DateTime=0
Write IC File at Sim End=0
Echo Input=False
Echo Parameters=False
Echo Output=False
Write Detailed= 0
HDF Write Warmup=0
HDF Write Time Slices=0
HDF Flush=0
HDF Face Node Velocities=0
HDF Compression= 1
HDF Chunk Size= 1
HDF Spatial Parts= 1
HDF Use Max Rows=0
HDF Fixed Rows= 1
Calibration Method= 0
Calibration Iterations= 20
Calibration Max Change=0.05
Calibration Tolerance=0.2
Calibration Maximum=1.5
Calibration Minimum=0.5
Calibration Optimization Method= 1
WQ AD Non Conservative
WQ ULTIMATE=-1
WQ Max Comp Step=1HOUR
WQ Output Interval=15MIN
WQ Output Selected Increments= 0
WQ Output face flow=0
WQ Output face velocity=0
WQ Output face area=0
WQ Output face dispersion=0
WQ Output cell volume=0
WQ Output cell surface area=0
WQ Output cell continuity=0
WQ Output cumulative cell continuity=0
WQ Output face conc=0
WQ Output face dconc_dx=0
WQ Output face courant=0
WQ Output face peclet=0
WQ Output face adv mass=0
WQ Output face disp mass=0
WQ Output cell mass=0
WQ Output cell source sink temp=0
WQ Output nsm pathways=0
WQ Output nsm derived pathways=0
WQ Output MaxMinRange=-1
WQ Daily Max Min Mean=-1
WQ Daily Range=0
WQ Daily Time=0
WQ Create Restart=0
WQ Fixed Restart=0
WQ System Summary=0
WQ Write To DSS=0
WQ Use Fixed Temperature=0
Sorting and Armoring Iterations= 10
XS Update Threshold= 0.02
Bed Roughness Predictor= 0
Hydraulics Update Threshold= 0.02
Energy Slope Method= 1
Volume Change Method= 1
Sediment Retention Method= 0
XS Weighting Method= 0
Number of US Weighted Cross Sections= 1
Number of DS Weighted Cross Sections= 1
Upstream XS Weight=0
Main XS Weight=1
Downstream XS Weight=0
Number of DS XS's Weighted with US Boundary= 1
Upstream Boundary Weight= 1
Weight of XSs Associated with US Boundary= 0
Number of US XS's Weighted with DS Boundary= 1
Downstream Boundary Weight= 0.5
Weight of XSs Associated with DS Boundary= 0.5
Percentile Method= 0
Sediment Output Level= 3
Mass or Volume Output= 0
Output Increment Type= 1
Profile and TS Output Increment= 1
XS Output Flag= 0
XS Output Increment= 10
Write Gradation File= 0
Read Gradation Hotstart= 0
Write HDF5 File= 1
Write Binary Output= 1
Write DSS Sediment File= 0
SV Curve= 0
Specific Gage Flag= 0

--- PIPESTCK2_A.f01 (steady flow) ---

Flow Title=Flows
Program Version=5.07
Number of Profiles= 6
Profile Names=01pct,10pct,04pct,02pct,0_2pct,01plus
River Rch & RM=PIPESTCK2_A,Main            ,30889
     388     202     270     327     545     573
River Rch & RM=PIPESTCK2_A,Main            ,28302
     440     230     308     372     618     651
River Rch & RM=PIPESTCK2_A,Main            ,27817
     505     266     354     427     707     747
River Rch & RM=PIPESTCK2_A,Main            ,26799
     735     392     519     623    1022    1087
River Rch & RM=PIPESTCK2_A,Main            ,23976
     840     451     595     714    1165    1243
River Rch & RM=PIPESTCK2_A,Main            ,20984
     983     530     698     836    1359    1454
River Rch & RM=PIPESTCK2_A,Main            ,20892
     983     530     698     836    1359    1454
River Rch & RM=PIPESTCK2_A,Main            ,15265
    1208     657     862    1029    1664    1786
River Rch & RM=PIPESTCK2_A,Main            ,12667
    1347     736     963    1149    1851    1992
River Rch & RM=PIPESTCK2_A,Main            ,7108
    1727     952    1241    1476    2363    2554
River Rch & RM=PIPESTCK2_A,Main            ,4582
    2015    1118    1452    1725    2749    2980
River Rch & RM=PIPESTCK2_A,Main            ,0
    2075    1153    1496    1777    2829    3069
Boundary for River Rch & Prof#=PIPESTCK2_A,Main            , 1
Up Type= 0
Dn Type= 1
Dn Known WS=1686.9
Boundary for River Rch & Prof#=PIPESTCK2_A,Main            , 2
Up Type= 0
Dn Type= 1
Dn Known WS=1686
Boundary for River Rch & Prof#=PIPESTCK2_A,Main            , 3
Up Type= 0
Dn Type= 1
Dn Known WS=1686.4
Boundary for River Rch & Prof#=PIPESTCK2_A,Main            , 4
Up Type= 0
Dn Type= 1
Dn Known WS=1686.6
Boundary for River Rch & Prof#=PIPESTCK2_A,Main            , 5
Up Type= 0
Dn Type= 1
Dn Known WS=1687.8
Boundary for River Rch & Prof#=PIPESTCK2_A,Main            , 6
Up Type= 0
Dn Type= 1
Dn Known WS=1688
DSS Import GetInterval= 0
DSS Import GetPeak= 0
DSS Import FillOption= 0

--- PIPESTCK2_A.g01 (geometry) ---

Geom Title=Geometry
Program Version=5.07

River Reach=PIPESTCK2_A     ,Main
Reach XY= 30
1976470.99873534191763.1481258931977129.89041435191965.109327998
     1977367.474192567.946000032     1977577.196192572.112000008
      1977710.53192880.4460000251978231.36300003193179.751000041
1978250.48000002 194132.718000041978656.03500004194817.093000036
1978611.56000002195172.7790000291979066.74900001195437.032999993
     1979234.616195756.025000029     1979206.491196566.442000018
     1979484.095196794.567000026     1979517.158197546.771999972
     1979995.232198273.759999986     1981087.224198727.369999986
     1980681.495199222.683000029     1980207.133199216.816000021
     1980603.077200072.3820000221981591.78600002200420.219000013
1982161.70300001201341.9540000511983262.74500002 202079.45400003
1983754.41100002202701.8500000141985727.84900001203162.266000026
1987752.32800002204444.037000017     1989374.724204913.828999988
1990899.90899999206358.6900000351992555.92399999207456.078000025
1992672.85100001 207833.844000031993930.99093348209004.945607307

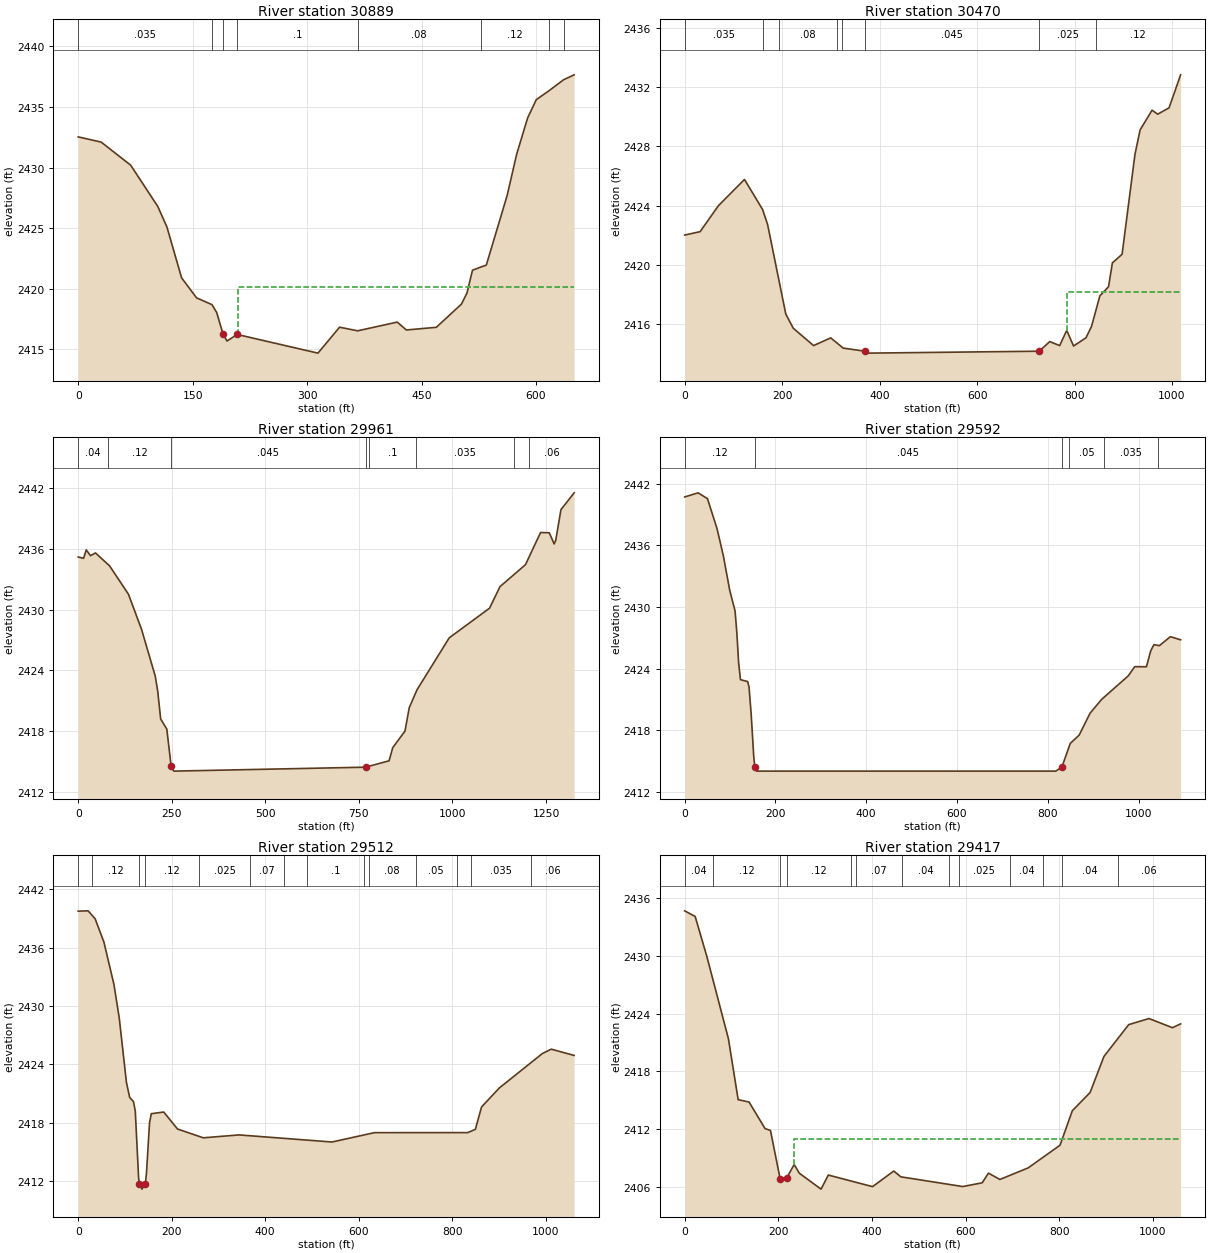
Type RM Length L Ch R = 1 ,30889   ,345.9,419.2,599.4
XS GIS Cut Line= 4
1976367.67035371191944.4684142061976451.14479569191815.083029137
 1976628.5279849 191558.399120051976551.31412606191391.450236091
#Sta/Elev= 30
       0 2432.53    30.1  2432.1    68.7  2430.2   104.3 2426.79   116.3 2425.09
   135.5  2420.9   155.1 2419.25   175.3 2418.69   181.5 2418.04  189.89 2416.24
     195 2415.69   208.3 2416.23   314.2 2414.69   342.5 2416.83   366.2 2416.53
   418.1 2417.25     430  2416.6   469.3 2416.82   502.3 2418.74   509.5 2419.65
   516.7 2421.53   527.6 2421.79   534.8 2421.95   562.1 2427.69   574.6  2431.1
     589  2434.1   600.3  2435.6   616.8 2436.33     636 2437.24649.9277 2437.65
#Mann= 8 ,-1 , 0
       0    .035       0   175.3      .1       0  189.89    .045       0
   208.3      .1       0   366.2     .08       0   527.6     .12       0
   616.8      .1       0     636     .12       0
#XS Ineff= 2 , 0
                           209.9         2420.11
Permanent Ineff=
       F       F
Bank Sta=189.89,208.3
XS Rating Curve= 0 ,0
Exp/Cntr(USF)=0,0
Exp/Cntr=0.3,0.1

Type RM Length L Ch R = 1 ,30470   ,472.5,509.4,590.2
XS GIS Cut Line= 4
1976568.00901446192146.8939360071976670.26520589192019.595411988
1977125.20091468191479.0984001691976991.36292979191006.204728522
#Sta/Elev= 30
       0 2422.01    31.7 2422.24    69.1 2423.99   122.7 2425.77     160 2423.73
   170.2 2422.72   207.5 2416.67   222.9 2415.71   264.5 2414.54   299.7 2415.06
   325.3 2414.37     370 2414.16   376.6 2414.03   727.7 2414.16   749.1 2414.81
   769.5 2414.54     784 2415.57     798 2414.51   823.6 2415.07   834.9 2415.84
     852  2417.9   869.8 2418.52   877.7 2420.13   897.6 2420.71     924 2427.46
   934.6 2429.12   959.1 2430.45   970.7 2430.18     994 2430.61  1017.7 2432.84
#Mann= 8 ,-1 , 0
       0    .035       0     160     .04       0  193.28     .08       0
  313.28     .05       0  323.28    .025       0     370    .045       0
   727.7    .025       0  843.28     .12       0
#XS Ineff= 2 , 0
                          784.41         2418.14
Permanent Ineff=
       F       F
Bank Sta=370,727.7
XS Rating Curve= 0 ,0
Exp/Cntr(USF)=0,0
Exp/Cntr=0.3,0.1

Type RM Length L Ch R = 1 ,29961   ,342.9,368.3,398.5
XS GIS Cut Line= 4
1976927.99580873192331.2897062291977084.89941621192230.061572366
1977653.46410141191793.0934611931977974.01985864191519.777499764
#Sta/Elev= 30
       0 2435.19    14.3 2435.06    21.5 2435.89    32.9 2435.32    46.1 2435.59
    83.7 2434.32   134.4  2431.5   169.5 2428.01   205.8 2423.42   212.4 2421.94
   220.3 2419.18   236.7 2418.19   248.4  2414.5   255.4 2414.03   767.8 2414.42
   830.6 2415.05   840.4 2416.35   873.1 2417.99   884.4 2420.29   905.1 2422.06
   991.3  2427.2    1099 2430.13  1126.9 2432.26    1195 2434.43  1235.4 2437.61
  1258.7 2437.58  1271.6 2436.48  1275.9 2436.84  1289.8 2439.871325.063 2441.53
#Mann= 8 ,-1 , 0
       0     .04       0      80     .12       0   248.4    .045       0
   767.8    .025       0  776.72      .1       0  903.81    .035       0
 1163.81     .04       0 1203.81     .06       0
Bank Sta=248.4,767.8
XS Rating Curve= 0 ,0
Exp/Cntr(USF)=0,0
Exp/Cntr=0.3,0.1

Type RM Length L Ch R = 1 ,29592   ,76.3,79.8,174
XS GIS Cut Line= 4
1977191.18895677192572.5500919341977260.36151491192520.248889439
1977943.65141848192054.5994736711978089.45451846191950.562886705
#Sta/Elev= 30
       02440.724  29.6312441.125  50.1962440.556  71.106 2437.67  85.1592435.008
  99.3132431.624 111.0182429.628 114.9892427.482 118.9592424.538 122.9182422.939
  138.812422.747 141.8142422.207 146.5362419.573 152.0482415.541  154.432414.439
 158.6612414.031 817.7212414.031  831.272414.443 849.4832416.723 869.3342417.546
 893.1552419.669 918.6142421.011 977.4842423.313 991.5292424.2021017.402 2424.19
1026.811 2425.741033.8672426.3411046.001 2426.251070.1832427.1211092.7052426.817
#Mann= 6 ,-1 , 0
       0     .12       0  154.43    .045       0  831.27    .025       0
  846.72     .05       0  923.59    .035       0 1043.59     .06       0
Bank Sta=154.43,831.27
XS Rating Curve= 0 ,0
Exp/Cntr(USF)=0,0
Exp/Cntr=0.3,0.1

Type RM Length L Ch R = 1 ,29512   ,105,95.5,144.5
XS GIS Cut Line= 6
1977240.11588814192621.4770233011977290.72995507192586.047176449
1977579.23013658192410.5850777541977731.07233737192309.356943892
1977893.03735155192214.8773522871978120.98003824192032.883586633
#Sta/Elev= 30
       02439.765   21.192439.798  36.1822438.985  55.0282436.577  76.4842432.218
  87.8912428.738 103.1062422.168 110.047  2420.6 118.3212420.161 122.1252419.191
 129.2262412.348  130.732411.736 136.4182411.159  143.662411.727 146.0072412.764
 152.5552417.944 156.359 2418.92 182.9852419.094 212.4612417.346 267.664 2416.44
 344.0482416.738 543.1292416.008  633.812416.971 833.2952416.974 849.824 2417.31
  863.022419.614 901.1812421.575 993.1672425.1131012.0762425.5621061.1662424.917
#Mann= 14 ,-1 , 0
       0     .04       0      30     .12       0  130.73    .045       0
  143.66     .12       0  258.49    .025       0  368.49     .07       0
  439.48    .025       0  489.48      .1       0  611.97    .025       0
  621.97     .08       0  721.97     .05       0  809.48    .025       0
  839.48    .035       0  969.48     .06       0
Bank Sta=130.73,143.66
XS Rating Curve= 0 ,0
Exp/Cntr(USF)=0,0
Exp/Cntr=0.3,0.1

Type RM Length L Ch R = 1 ,29417   ,179.7,191.3,471.9
XS GIS Cut Line= 5
 1977289.0428195192719.3308860351977407.14230901192626.538429994
1977451.00783368192553.9916007261978024.63392557192226.687301237
1978148.42932592192119.542744207
#Sta/Elev= 30
       02434.663   22.442434.073  47.229 2429.95  93.3712421.395 114.2332415.062
 137.5042414.816 171.6342412.064 183.2052411.867  203.752406.873  217.512406.902
 233.7982408.334 244.8892407.428 291.2292405.778 306.782 2407.24 401.2152406.036
 446.5432407.656 461.6532407.054  593.862406.045  635.412406.436 648.7132407.438
 673.1842406.781 733.6212407.985 801.6132410.337 827.8372413.913 865.8282415.806
 895.4062419.551  948.212422.849   991.62423.4831041.7192422.5321059.129 2422.93
#Mann= 13 ,-1 , 0
       0     .04       0      60     .12       0  203.75    .045       0
  217.51     .12       0  354.97      .1       0  364.97     .07       0
  464.97     .04       0  564.97      .1       0  584.97    .025       0
  694.97     .04       0  764.97     .05       0  804.97     .04       0
  925.41     .06       0
#XS Ineff= 2 , 0
                           233.8            2411
Permanent Ineff=
       F       F
Bank Sta=203.75,217.51
XS Rating Curve= 0 ,0
Exp/Cntr(USF)=0,0
Exp/Cntr=0.3,0.1

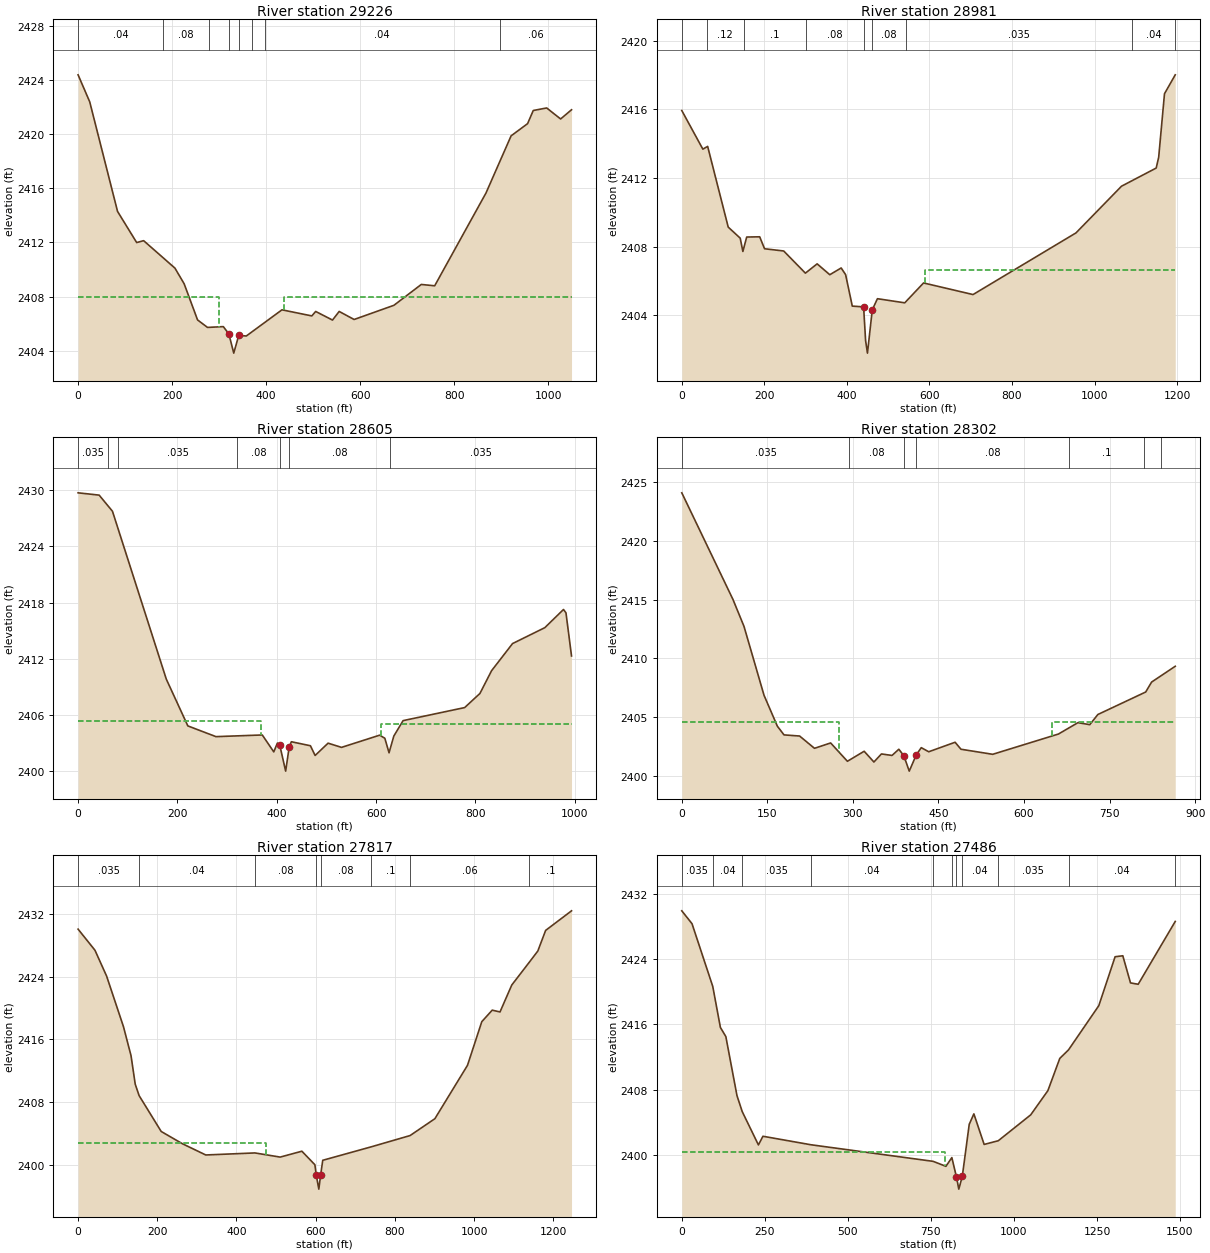
Type RM Length L Ch R = 1 ,29226   ,243.1,244.8,237.2
XS GIS Cut Line= 4
1977310.97558184192768.2578174021977558.81579625192639.023233171
 1977644.9103241192574.7939822351978165.06885651192163.968134981
#Sta/Elev= 30
       02424.379  24.7652422.384  83.9662414.291 124.6672411.993 139.4672412.133
 206.0692410.105 225.6952408.946  254.172406.281 275.3662405.727 308.9722405.786
   320.7 2405.25 331.1732403.829   341.82405.139 357.9022405.094 433.7112407.026
 497.2312406.577 505.4652406.906 541.233 2406.27 555.4572406.906 587.2322406.313
  671.91 2407.36 730.137  2408.9  758.632408.801 867.7632415.651 921.2442419.875
 956.2822420.773 968.3362421.745  996.932421.9321026.5632421.1191049.754  2421.8
#Mann= 8 ,-1 , 0
       0     .04       0     180     .08       0  279.51     .04       0
   320.7    .045       0   341.8     .04       0  369.51      .1       0
  396.92     .04       0  896.92     .06       0
#XS Ineff= 2 , 0
             300 2407.97  437.18         2407.97
Permanent Ineff=
       F       F
Bank Sta=320.7,341.8
XS Rating Curve= 0 ,0
Exp/Cntr(USF)=0,0
Exp/Cntr=0.3,0.1

Type RM Length L Ch R = 1 ,28981   ,361.6,375.5,344.4
XS GIS Cut Line= 5
1977310.09827135193062.6629733851977605.27950969192867.242060964
1977800.70042211192716.9182821781978214.77410368 192294.64512177
1978216.06067544192291.265145108
#Sta/Elev= 30
       02415.936  50.9952413.685  62.6512413.845 112.4552409.137 141.4932408.492
 147.9662407.715 157.2312408.557 188.7092408.571 200.5122407.874 246.8932407.743
 299.478 2406.45 327.8862406.993 358.6082406.359  386.172406.753 396.9322406.362
 413.0752404.527   440.52404.483 445.3612402.507  449.852401.784   461.52404.309
 473.9992404.959 540.2262404.719 585.7582405.878 705.6382405.201 955.0972408.798
1065.3772411.5221149.4322412.582 1155.492413.2171169.5482416.9181195.5882418.021
#Mann= 9 ,-1 , 0
       0    .035       0      60     .12       0     150      .1       0
     300     .08       0   440.5    .045       0   461.5     .08       0
  544.01    .035       0 1090.56     .04       0 1195.59     .06       0
#XS Ineff= 2 , 0
                          588.31         2406.64
Permanent Ineff=
       F       F
Bank Sta=440.5,461.5
XS Rating Curve= 0 ,0
Exp/Cntr(USF)=0,0
Exp/Cntr=0.3,0.1

Type RM Length L Ch R = 1 ,28605   ,216.4,303,297.2
XS GIS Cut Line= 5
1977594.34687123193214.353331978 1977874.4957317193001.166882064
1977959.22367974192869.9752205781978273.53703538192548.828965899
1978300.47366545192525.341538459
#Sta/Elev= 30
       02429.703  42.3712429.458  69.2222427.737 177.5762409.836 220.9182404.847
 277.5492403.702 370.777 2403.88 393.9582402.075  401.232403.021   406.12402.767
 417.8412400.024     4252402.604  429.362403.157 467.6742402.732 477.1662401.693
  503.272403.006 530.2952402.556 607.214 2403.86 617.5192403.527 625.976 2401.98
 635.6222403.768 654.2442405.409 778.1932406.801 808.9052408.305 832.3582410.731
 874.5982413.626 939.5462415.324 977.1692417.262 982.1612416.898 993.3152412.304
#Mann= 7 ,-1 , 0
       0    .035       0      60     .12       0      80    .035       0
     320     .08       0   406.1    .045       0     425     .08       0
  628.21    .035       0
#XS Ineff= 2 , 0
          368.82 2405.34  610.19         2405.08
Permanent Ineff=
       F       F
Bank Sta=406.1,425
XS Rating Curve= 0 ,0
Exp/Cntr(USF)=0,0
Exp/Cntr=0.3,0.1

Type RM Length L Ch R = 1 ,28302   ,444.3,485.1,448.9
XS GIS Cut Line= 4
 1977703.6732558193293.6149607931977942.82472205193140.558022393
1978112.28061814192991.600823414  1978386.637582192765.482446606
#Sta/Elev= 30
       02424.109  89.5852415.029 109.0612412.718 144.1182406.851 167.4892404.214
 179.1752403.469 206.5432403.371 232.6082402.325 260.9742402.781 290.3172401.219
 319.7112402.073 336.8142401.156 349.9492401.844  368.532401.716 380.4952402.245
   389.22401.699 398.7512400.379   411.12401.768 419.809 2402.38 432.9142402.031
 479.1512402.841 489.4152402.245 545.0542401.813 660.2912403.542  694.46 2404.51
 715.2852404.342  729.422405.207 813.2972407.126 823.6142407.972 865.084 2409.32
#Mann= 7 ,-1 , 0
       0    .035       0  293.94     .08       0   389.2    .045       0
   411.1     .08       0  679.55      .1       0  809.55     .04       0
  839.55     .06       0
#XS Ineff= 2 , 0
             275 2404.58  649.18         2404.58
Permanent Ineff=
       F       F
Bank Sta=389.2,411.1
XS Rating Curve= 0 ,0
Exp/Cntr(USF)=0,0
Exp/Cntr=0.3,0.1

Type RM Length L Ch R = 1 ,27817   ,281.3,331.5,335.6
XS GIS Cut Line= 4
1977605.30804452193332.7893128441977911.42192132193335.522472458
1978421.78840681193291.5061830841978848.22259362193256.913219745
#Sta/Elev= 30
       0 2430.07    42.6 2427.38    72.1 2424.07   114.8 2417.59   133.7 2413.92
   144.3 2410.28   154.1 2408.82   209.9 2404.24   263.7 2402.67   322.5 2401.24
   446.7  2401.5   510.4 2400.97   565.2 2401.72   598.1 2399.99   601.5 2398.66
     608 2396.88  612.49 2398.66   617.9 2400.56   739.7 2402.27   838.5 2403.72
   901.1 2405.87   983.4 2412.68  1019.6 2418.26  1045.9 2419.73  1065.6  2419.5
  1095.3 2422.94  1139.3 2425.83  1161.1 2427.28  1180.8 2429.91  1246.2 2432.41
#Mann= 8 ,-1 , 0
       0    .035       0   154.1     .04       0   446.7     .08       0
   601.5    .045       0  612.49     .08       0   739.7      .1       0
   838.5     .06       0  1139.3      .1       0
#XS Ineff= 2 , 0
             475 2402.81
Permanent Ineff=
       F       F
Bank Sta=601.5,612.49
XS Rating Curve= 0 ,0
Exp/Cntr(USF)=0,0
Exp/Cntr=0.5,0.3

Type RM Length L Ch R = 1 ,27486   ,142.2,114.8,108.5
XS GIS Cut Line= 6
1977571.20694209193409.0894189071978066.06446881193386.157533048
1978206.11384586193537.7599497691978512.66994824193648.866638594
1978585.85319907193635.7311833161978965.79749542193583.379146476
#Sta/Elev= 30
       0 2429.88    30.8  2428.3    93.2 2420.63   116.2 2415.61   132.6 2414.49
   166.1 2407.27   181.9 2405.31   230.7 2401.23   244.3 2402.29   388.8 2401.25
   756.8 2399.22   795.2 2398.61   813.1 2399.68     827  2397.3     834 2395.82
   844.5 2397.37   865.4 2403.75   879.4 2405.03   910.3 2401.29   952.8 2401.74
  1050.5 2404.91  1102.2 2407.87  1138.1 2411.82  1164.3 2412.86  1255.5 2418.27
  1304.6 2424.26  1327.8 2424.38    1351 2421.06  1374.1 2420.89  1485.7 2428.58
#Mann= 11 ,-1 , 0
       0    .035       0    93.2     .04       0   181.9    .035       0
   388.8     .04       0   756.8      .1       0   813.1     .04       0
     827    .045       0   844.5     .04       0   952.8    .035       0
  1164.3     .04       0  1485.7    .035       0
#XS Ineff= 2 , 0
             793 2400.39     880         2400.39
Permanent Ineff=
       F       F
Bank Sta=827,844.5
XS Rating Curve= 0 ,0
Exp/Cntr(USF)=0,0
Exp/Cntr=0.5,0.3

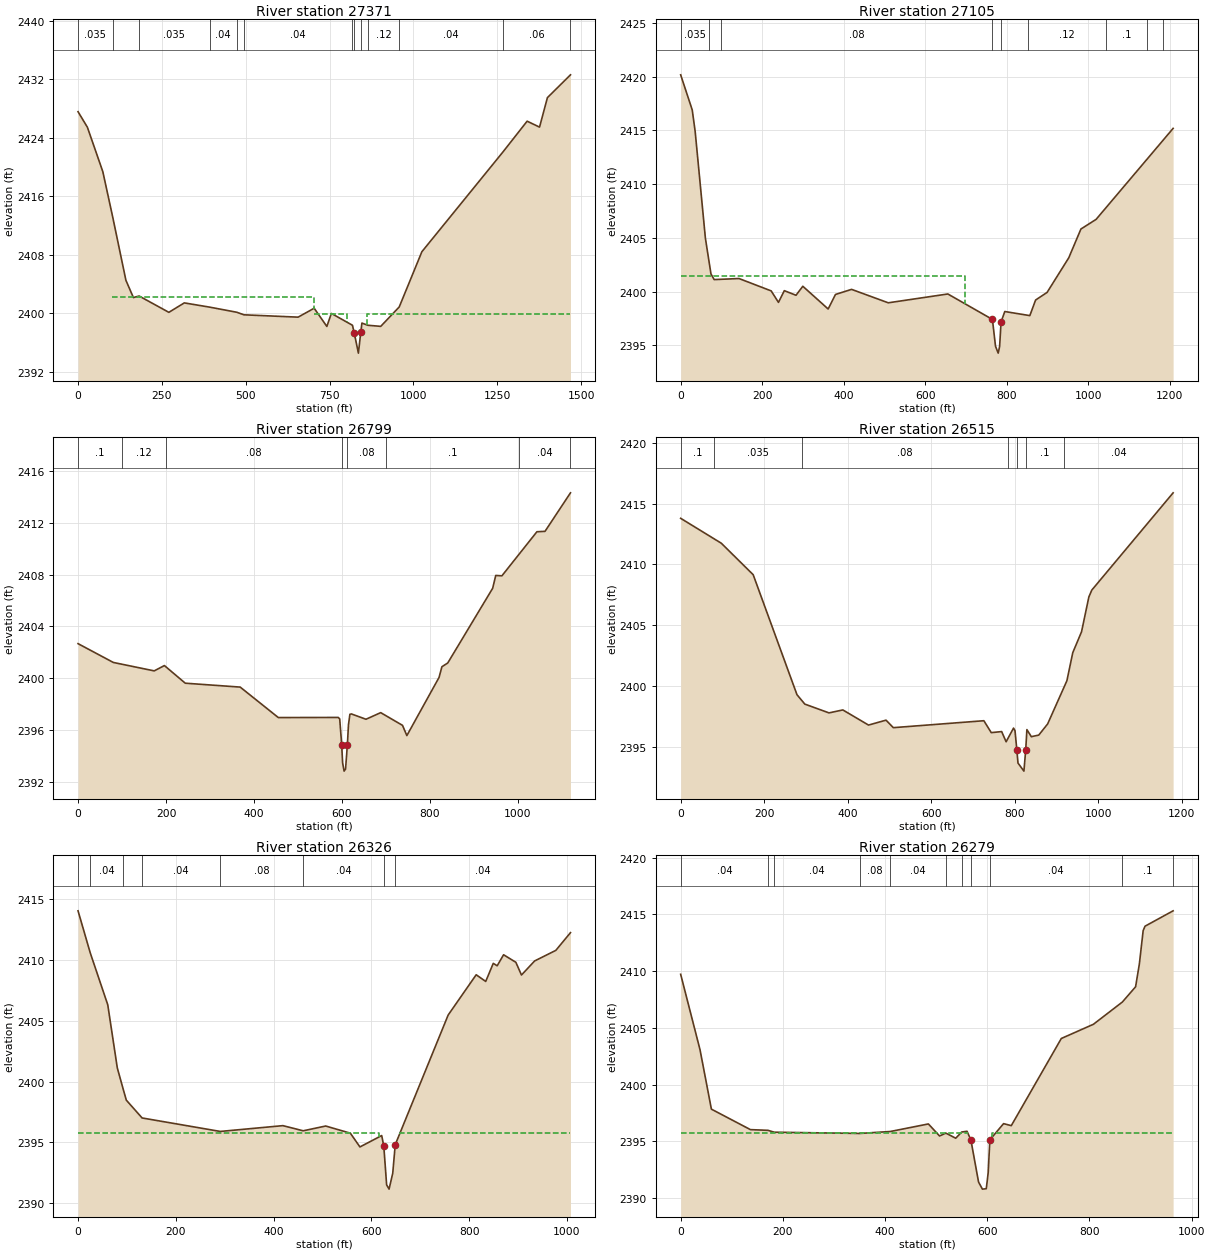
Type RM Length L Ch R = 1 ,27371   ,257.6,265.5,256.9
XS GIS Cut Line= 6
1977574.04611621193458.7288441641977812.73783132193453.711303045
1977983.49874992193442.452341379 1978210.1829418193635.604858871
1978537.12377368193758.5338197711978938.73921524193669.473674326
#Sta/Elev= 30
       0 2427.58    27.9 2425.45    73.9 2419.38   103.4 2413.17   142.8 2404.51
   165.1 2402.16   182.2 2402.37   270.8 2400.14   316.9 2401.43   392.5 2400.85
   473.3 2400.15   494.8  2399.8   656.2 2399.48   704.1  2400.7   741.9 2398.21
   755.4 2399.99   818.3 2398.37   823.4 2397.36     836 2394.56     843  2397.4
   846.5 2398.67   864.2 2398.37   902.6 2398.22   957.8 2400.88  1025.3 2408.43
  1267.7 2422.11  1339.1 2426.28  1376.1 2425.47  1399.6  2429.5  1468.4 2432.62
#Mann= 13 ,-1 , 0
       0    .035       0   103.4     .04       0   182.2    .035       0
   392.5     .04       0   473.3    .035       0   494.8     .04       0
   818.3     .08       0   823.4    .045       0     843     .08       0
   864.2     .12       0   957.8     .04       0  1267.7     .06       0
  1468.4    .035       0
#XS Ineff= 3 ,-1
  702.51  802.68 2399.87     100  702.512402.175  861.89 1468.392399.909
Permanent Ineff=
       F       F       F
Bank Sta=823.4,843
XS Rating Curve= 0 ,0
Exp/Cntr(USF)=0,0
Exp/Cntr=0.5,0.3

Type RM Length L Ch R = 1 ,27105   ,303.1,306.7,289
XS GIS Cut Line= 4
1977566.14645694193546.4814916831978144.20971537 193802.30523158
1978397.57361161193903.1588213471978699.18021998 193864.62758063
#Sta/Elev= 30
       02420.168  28.404  2416.9  35.5792414.901  60.6932404.971  74.3822401.649
   82.22 2401.12 143.2122401.219 222.143 2400.07 240.081    2399 254.432 2400.09
 283.1352399.662 299.878  2400.5 362.0652398.385 380.0042399.737 419.4692400.211
 509.6222398.961 655.8812399.782   765.32397.414 772.9242394.915 779.473 2394.28
 783.0042394.901   786.52397.173 795.656 2398.15  857.16 2397.77 871.2852399.219
 899.5342399.929  952.792403.153 982.5582405.8241019.8732406.7231208.8982415.187
#Mann= 9 ,-1 , 0
       0    .035       0      70     .12       0     100     .08       0
   765.3    .045       0   786.5     .08       0  852.14     .12       0
 1044.84      .1       0 1144.84     .12       0 1184.84      .1       0
#XS Ineff= 2 , 0
          698.95 2401.45
Permanent Ineff=
       F       F
Bank Sta=765.3,786.5
XS Rating Curve= 0 ,0
Exp/Cntr(USF)=0,0
Exp/Cntr=0.3,0.1

Type RM Length L Ch R = 1 ,26799   ,283.8,283.8,253.3
XS GIS Cut Line= 3
1977657.24810523194004.1898664391978540.06060529194142.210699797
1978752.12568125194063.837467164
#Sta/Elev= 30
       0 2402.67    80.2 2401.22   173.2 2400.57   196.4 2400.98   243.8 2399.62
   368.7 2399.32   455.4 2396.97   591.6 2396.98   594.9 2396.87  599.43 2394.89
   601.5 2393.48   604.9 2392.84   608.2    2393  612.36 2394.86   614.8  2396.4
   618.1 2397.22   621.5 2397.25   654.7 2396.84   688.1 2397.35   737.7 2396.37
   747.6 2395.58   820.7 2400.06   827.3 2400.89   840.6 2401.18   942.7 2406.94
   949.7 2407.93   963.7  2407.9  1043.3  2411.3  1061.7 2411.33  1119.6  2414.3
#Mann= 8 ,-1 , 0
       0      .1       0     100     .12       0     200     .08       0
  599.43    .045       0  612.36     .08       0     700      .1       0
 1003.54     .04       0 1119.62     .12       0
Bank Sta=599.43,612.36
XS Rating Curve= 0 ,0
Exp/Cntr(USF)=0,0
Exp/Cntr=0.3,0.1

Type RM Length L Ch R = 1 ,26515   ,185.5,188.7,169.7
XS GIS Cut Line= 4
1977678.49618845194531.4329213011978358.41182089194281.736857773
1978537.24819071194207.5028929411978781.82133599194116.335842372
#Sta/Elev= 30
       02413.795  97.2982411.745  173.612409.155 278.4622399.282 297.155 2398.51
 355.0592397.787 388.2912398.029 449.7212396.784 491.6622397.189 509.1372396.571
 725.8572397.142 743.6182396.161 768.4842396.249 779.1412395.411 796.9022396.534
 800.4542396.316  804.71 2394.77 807.5592393.661 821.7682392.995 826.1072394.765
 828.8722396.412 839.5292395.829  857.29 2395.96 878.604 2396.88 924.6852400.435
 938.6912402.739 959.699 2404.46 977.2062407.321 984.2082407.887 1178.962415.892
#Mann= 7 ,-1 , 0
       0      .1       0      80    .035       0     290     .08       0
  784.32      .1       0  804.71    .045       0 826.107      .1       0
  917.95     .04       0
Bank Sta=804.71,826.107
XS Rating Curve= 0 ,0
Exp/Cntr(USF)=0,0
Exp/Cntr=0.5,0.3

Type RM Length L Ch R = 1 ,26326   ,54,47.2,45.5
XS GIS Cut Line= 4
1977934.94079423194693.3979354811978409.02588782 194438.64046526
1978591.23652877194335.725195833  1978812.808892194200.052263279
#Sta/Elev= 30
       02414.035  24.8872410.591  60.806 2406.31  80.3352401.118  91.2812399.531
   98.732398.471 131.0632397.006 290.9592395.898 419.0392396.375 460.5452395.951
 506.5762396.344 557.0642395.753 576.5982394.623  621.122395.561   625.42394.693
 631.1982391.511 636.1922391.156 643.7282392.469   648.82394.807 757.106 2405.47
  814.372408.778 833.903 2408.23 849.2912409.716 857.3182409.518 870.4292410.423
  895.562409.804 906.9962408.756 933.9252409.914 977.2352410.7821007.2752412.241
#Mann= 8 ,-1 , 0
       0      .1       0  24.887     .04       0  91.281    .035       0
 131.063     .04       0 290.959     .08       0 460.545     .04       0
   625.4    .045       0   648.8     .04       0
#XS Ineff= 2 , 0
             615 2395.76     658         2395.76
Permanent Ineff=
       F       F
Bank Sta=625.4,648.8
XS Rating Curve= 0 ,0
Exp/Cntr(USF)=0,0
Exp/Cntr=0.5,0.3

Type RM Length L Ch R = 1 ,26279   ,178.8,192.6,192.9
XS GIS Cut Line= 4
 1978007.4876235194759.1962224921978307.79775396194544.930005816
 1978694.1517982194327.2895180111978828.58409767194257.629144648
#Sta/Elev= 30
       02409.718  37.8682403.074  60.1372397.836 136.521 2396.03 170.8682395.969
 182.9582395.804 350.5622395.693 410.3382395.866 484.8072396.531 506.6872395.469
 519.0122395.722 538.2842395.274 550.0432395.821 560.4332395.883     5682395.118
 583.0272391.404 590.5582390.787 598.0892390.821 601.8542392.239   605.1 2395.13
 631.9392396.558 647.041 2396.38 744.9462404.062 807.7752405.314 864.4522407.276
 890.3182408.619 897.7082410.633 905.0982413.562 908.7932413.958 963.7582415.312
#Mann= 11 ,-1 , 0
       0     .04       0 170.868     .08       0 182.958     .04       0
 350.562     .08       0 410.338     .04       0 519.012     .08       0
 550.043     .04       0     568    .045       0   605.1     .04       0
 864.452      .1       0 963.758     .04       0
#XS Ineff= 2 , 0
             562 2395.76     610         2395.76
Permanent Ineff=
       F       F
Bank Sta=568,605.1
XS Rating Curve= 0 ,0
Exp/Cntr(USF)=0,0
Exp/Cntr=0.5,0.3

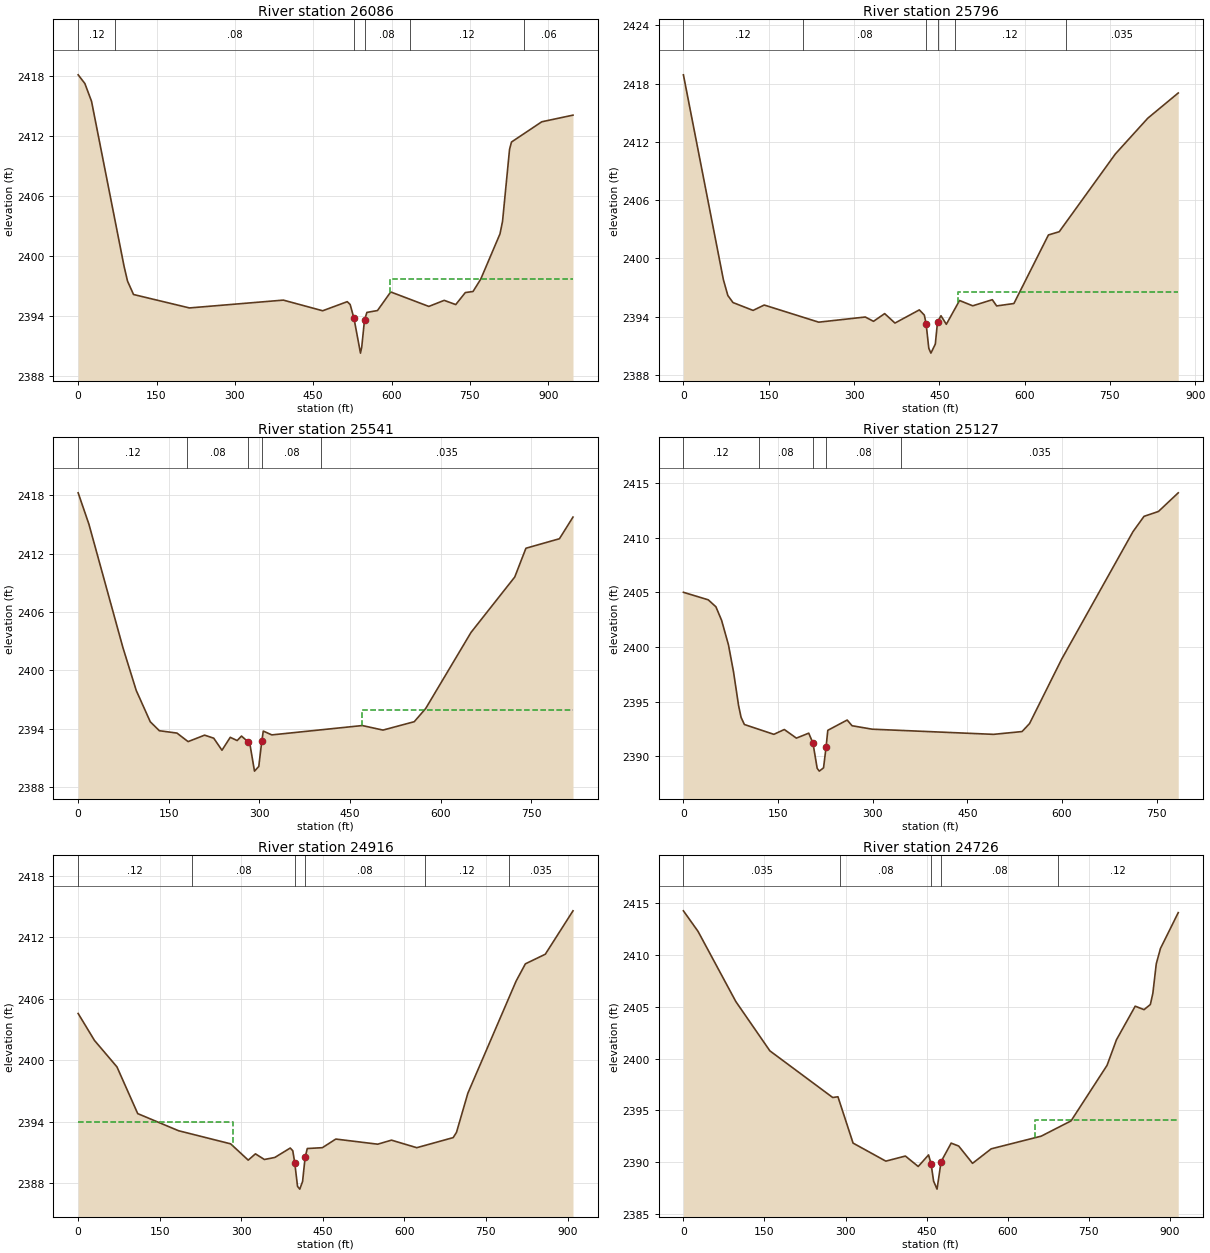
Type RM Length L Ch R = 1 ,26086   ,285.2,290.7,278.2
XS GIS Cut Line= 4
1978088.47013059194862.111491918 1978471.4499037194632.661055163
1978641.85059571194553.3656836381978920.91101279194411.813298163
#Sta/Elev= 30
       02418.121  12.8612417.253  25.6282415.473  87.8392399.008  94.5142397.517
 105.9882396.177 213.0762394.835 392.8322395.616 468.0932394.553 515.1352395.461
 520.681 2395.18   528.12393.785 540.4662390.321 542.9072390.936   548.22393.635
 552.7852394.389 573.0342394.575 598.3652396.432 671.3422394.986 700.7722395.593
 722.844 2395.17 741.2382396.372 755.9532396.478 770.6692397.708 807.5712402.235
 812.4532403.493  825.852410.675 829.5292411.407 887.5752413.431  947.312414.094
#Mann= 6 ,-1 , 0
       0     .12       0      70     .08       0   528.1    .045       0
   548.2     .08       0   634.4     .12       0   854.4     .06       0
#XS Ineff= 2 , 0
                           596.7         2397.68
Permanent Ineff=
       F       F
Bank Sta=528.1,548.2
XS Rating Curve= 0 ,0
Exp/Cntr(USF)=0,0
Exp/Cntr=0.3,0.1

Type RM Length L Ch R = 1 ,25796   ,254.7,254.9,255.2
XS GIS Cut Line= 4
1978263.93222929195008.8922860191978562.55522418194813.184560552
1978702.58747602194725.453511204 1979003.2904555194550.318808869
#Sta/Elev= 30
       02418.896  70.3492397.789  78.1622396.168  87.2052395.443 122.5092394.634
 142.1222395.188  237.942393.424 319.8662393.954 334.331 2393.51 353.9442394.305
 372.0652393.331  414.912394.688 423.6722394.154   426.82393.273 431.5722390.733
 435.2862390.235 443.0292391.165   446.92393.439 452.9942394.085 462.3872393.204
 485.6162395.654 508.8462395.108 543.2762395.737 550.8692395.095 581.2432395.345
 641.9862402.406 660.9742402.739 759.6892410.748  816.642414.425  870.272417.027
#Mann= 6 ,-1 , 0
       0     .12       0     210     .08       0   426.8    .045       0
   446.9     .08       0  477.04     .12       0  672.28    .035       0
#XS Ineff= 2 , 0
                          482.76         2396.51
Permanent Ineff=
       F       F
Bank Sta=426.8,446.9
XS Rating Curve= 0 ,0
Exp/Cntr(USF)=0,0
Exp/Cntr=0.3,0.1

Type RM Length L Ch R = 1 ,25541   ,371.9,414,403.4
XS GIS Cut Line= 4
1978383.71885436195118.5560977041978560.86808862195019.015099405
1978697.52606933194958.2782190881979111.37225015194742.869323708
#Sta/Elev= 30
       02418.226  17.7642415.018  74.2132402.324  96.1352397.954 119.3732394.738
 134.4262393.816 163.5992393.574 182.0292392.698 209.3932393.362 224.4872393.049
 238.1162391.815 251.8282393.139 263.2482392.806 270.4282393.267   281.22392.687
 284.7892392.289  291.97 2389.67 299.0542390.149     3042392.712  306.512393.779
 320.6922393.388 470.4762394.347 504.6572393.881 556.438 2394.74 575.3492396.091
 650.4832403.904 722.8782409.588 741.371 2412.54 796.8512413.516 819.2982415.737
#Mann= 5 ,-1 , 0
       0     .12       0     180     .08       0   281.2    .045       0
     304     .08       0  402.75    .035       0
#XS Ineff= 2 , 0
                          470.76         2395.97
Permanent Ineff=
       F       F
Bank Sta=281.2,304
XS Rating Curve= 0 ,0
Exp/Cntr(USF)=0,0
Exp/Cntr=0.3,0.1

Type RM Length L Ch R = 1 ,25127   ,219.4,210.9,186.3
XS GIS Cut Line= 4
1978540.62246184195310.8895520421978684.02898482195211.348553744
1978763.32435634  195194.47719811979209.43086116194910.465292855
#Sta/Elev= 30
       02405.015  39.3652404.327  51.5032403.689  60.5822402.441  71.471 2400.19
  79.4592397.722  87.4462394.644   91.442393.554  96.6762392.901 143.359    2392
 159.9672392.442 179.1252391.653  198.672392.108   205.42391.191 212.0872388.883
 215.4412388.629  222.152388.931   226.12390.798  228.912392.369  259.592393.311
 267.3692392.788 299.2122392.472 491.6992391.999  536.852392.255 548.7322392.986
 599.6992398.893 712.703 2410.57 730.1962411.974 753.1012412.422  784.48 2414.13
#Mann= 5 ,-1 , 0
       0     .12       0     120     .08       0   205.4    .045       0
   226.1     .08       0  345.64    .035       0
Bank Sta=205.4,226.1
XS Rating Curve= 0 ,0
Exp/Cntr(USF)=0,0
Exp/Cntr=0.3,0.1

Type RM Length L Ch R = 1 ,24916   ,188.4,189.9,185
XS GIS Cut Line= 4
1978596.29793547195606.1382758081978829.12264335195348.006534459
 1979087.2543847195091.5619286731979247.34397642194974.013627059
#Sta/Elev= 30
       02404.557  30.0192401.931  71.3632399.351 109.5472394.795 184.6572393.125
 280.4312391.847 312.7852390.259  326.04 2390.87 342.5292390.321 361.7172390.519
 390.0542391.438 394.7092391.177   398.3 2390.02 403.475  2387.7 407.5592387.431
 412.7552388.172   417.42390.525 421.433 2391.39 449.1812391.472 473.8462392.313
 550.9242391.813 576.2582392.207 622.8092391.471 689.6642392.454 695.7842392.959
 716.7242396.782 805.4482407.714 822.5282409.399  859.162410.336 910.0932414.568
#Mann= 6 ,-1 , 0
       0     .12       0     210     .08       0   398.3    .045       0
   417.4     .08       0  637.62     .12       0  791.48    .035       0
#XS Ineff= 2 , 0
             285    2394
Permanent Ineff=
       F       F
Bank Sta=398.3,417.4
XS Rating Curve= 0 ,0
Exp/Cntr(USF)=0,0
Exp/Cntr=0.3,0.1

Type RM Length L Ch R = 1 ,24726   ,140.6,155.2,157.4
XS GIS Cut Line= 4
1978667.15762917 195722.550629751978947.22213286195494.787328559
 1979087.2543847195334.5094499441979300.57122496195067.519340204
#Sta/Elev= 30
       02414.285  27.065  2412.3   97.032405.517 159.9982400.757  276.26 2396.25
 285.9362396.321 313.9222391.845 374.5172390.102 410.6742390.594 434.4172389.586
 453.5732390.701   458.2 2389.86 462.8742388.177  469.272387.398   476.8 2390.06
 495.4262391.843 509.3772391.559 534.9542389.891 569.4732391.291 662.0162392.516
 717.2172393.991 783.7992399.354 801.3142401.835  835.932405.072 852.2712404.737
 863.9422405.234 868.6112406.325 874.8982409.167 882.6172410.643 915.5642414.112
#Mann= 5 ,-1 , 0
       0    .035       0     290     .08       0   458.2    .045       0
   476.8     .08       0  693.82     .12       0
#XS Ineff= 2 , 0
                          650.67         2394.05
Permanent Ineff=
       F       F
Bank Sta=458.2,476.8
XS Rating Curve= 0 ,0
Exp/Cntr(USF)=0,0
Exp/Cntr=0.3,0.1