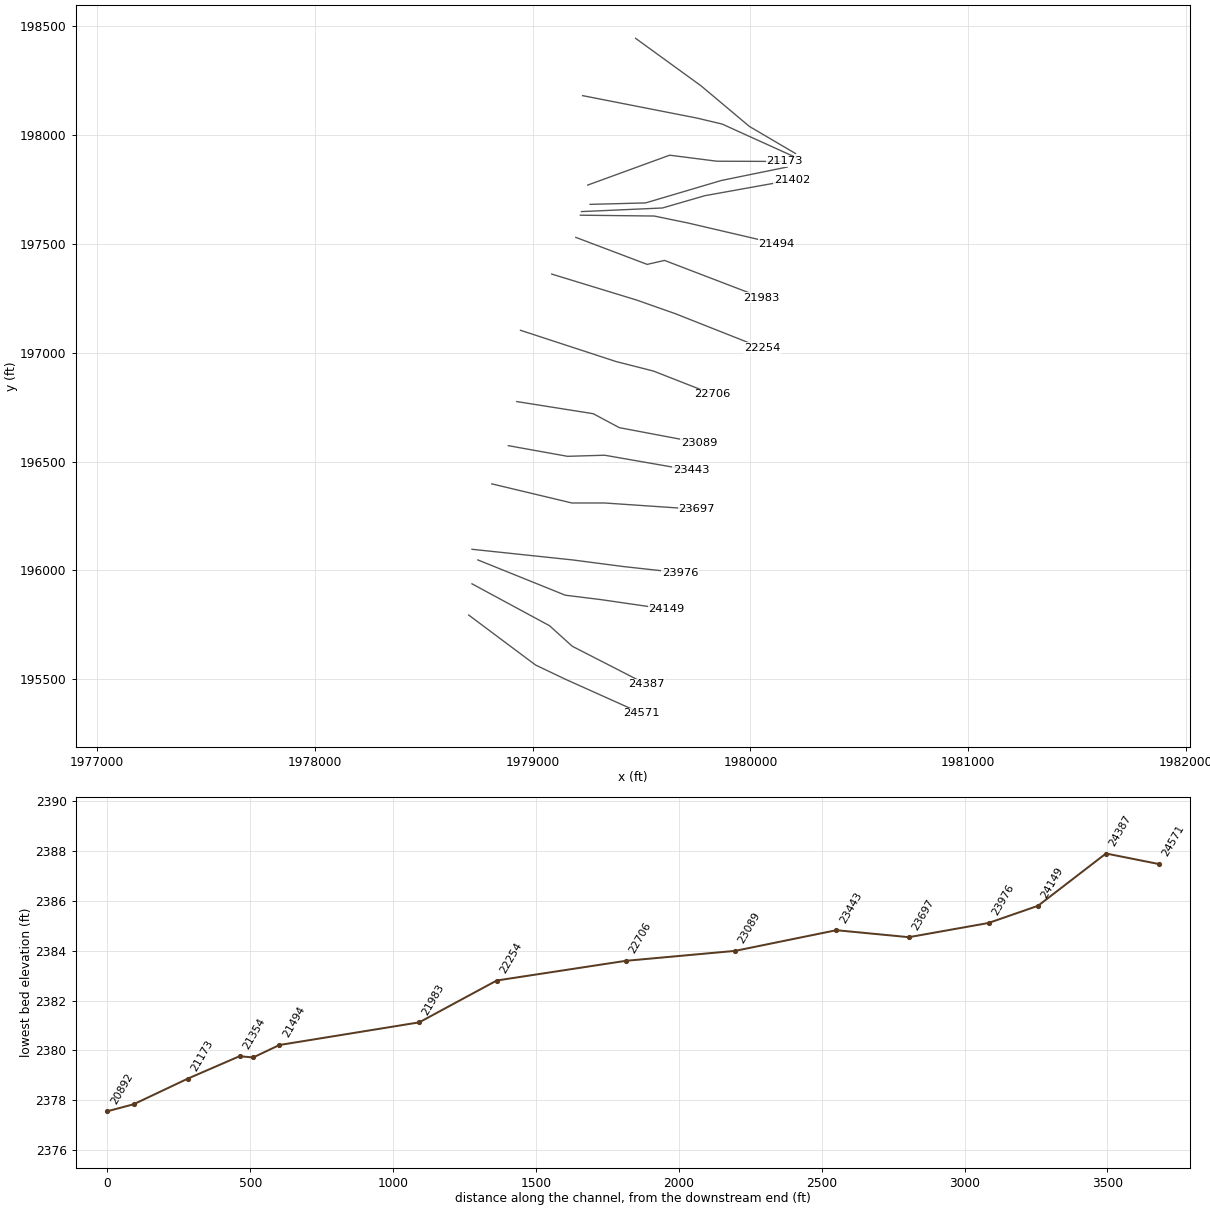
HEC-RAS study PIPESTCK2_A.prj: PIPESTCK2_A

--- PIPESTCK2_A.g01 (geometry) --- (continued)

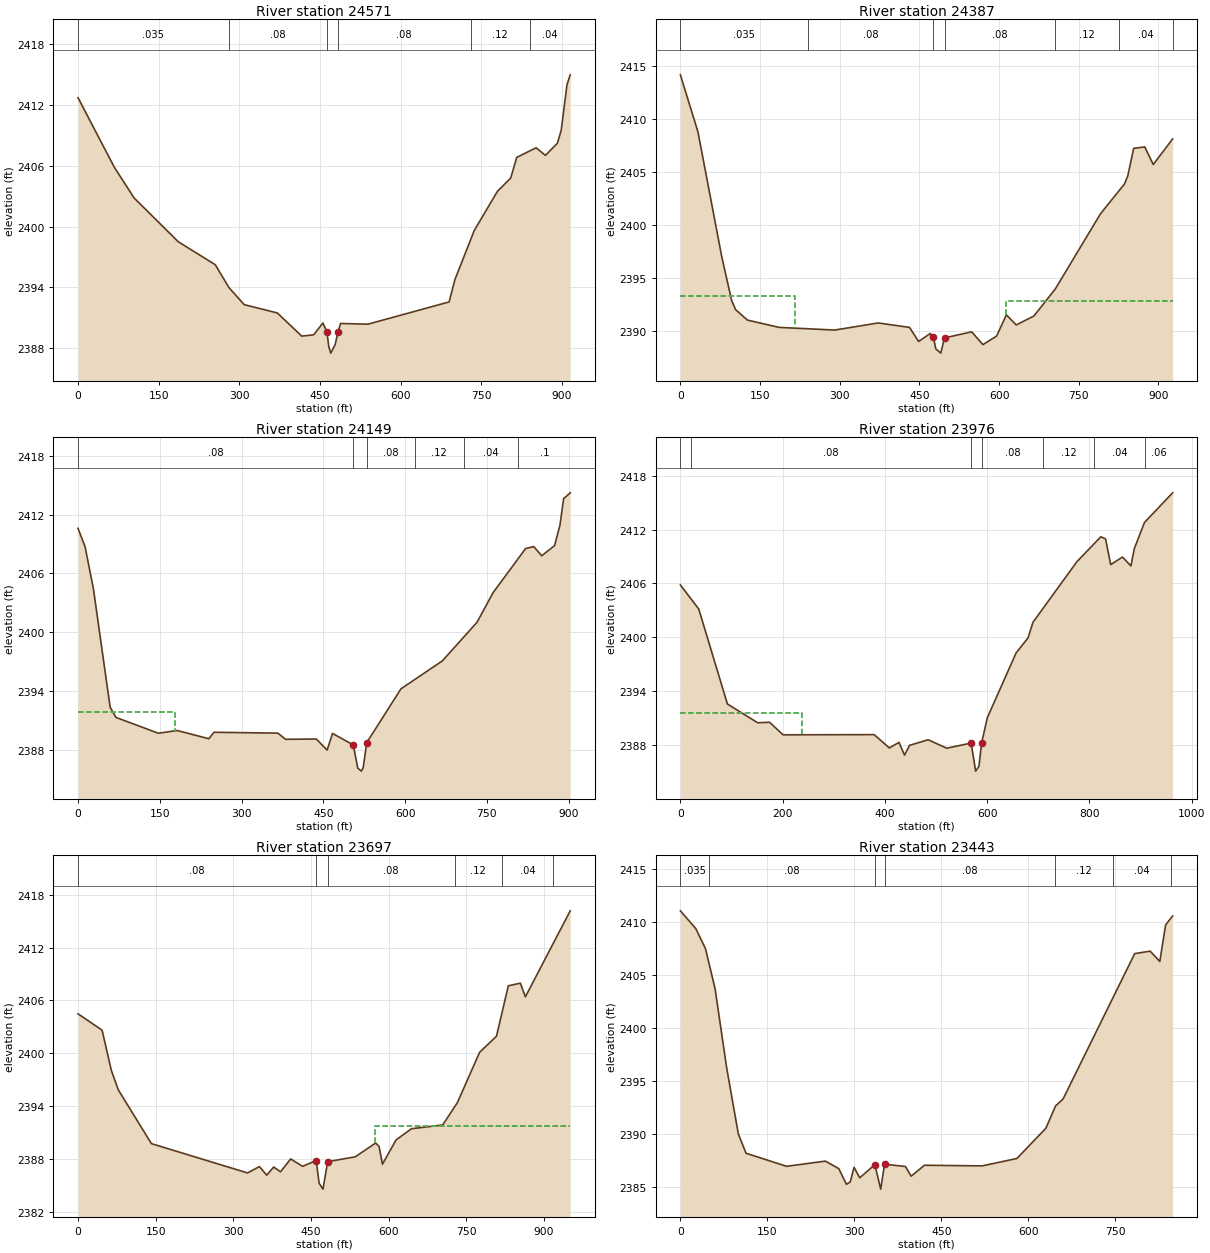
Type RM Length L Ch R = 1 ,24571   ,190.9,184,179.4
XS GIS Cut Line= 4
1978705.96174715195795.0974590181979013.02041987195565.647022263
1979154.73980728195498.1615996881979497.22832684 195344.63226333
#Sta/Elev= 30
       0 2412.73    67.6 2405.85   104.4 2402.82   186.4  2398.5   255.2 2396.23
     281 2393.95   309.2 2392.28   370.7 2391.46   416.2 2389.17   438.4  2389.3
   455.6 2390.47   462.9 2389.59   466.6  2388.1   470.2 2387.49   478.3 2388.33
   483.6 2389.57   488.4 2390.42   539.4 2390.35   690.3 2392.55     701 2394.74
     737  2399.6   780.1 2403.47   804.9 2404.79   816.1 2406.83   852.1 2407.78
   869.5 2407.03   891.6 2408.22   898.8 2409.49   909.6 2414.02 915.611 2414.99
#Mann= 6 ,-1 , 0
       0    .035       0     280     .08       0   462.9    .045       0
   483.6     .08       0  730.28     .12       0  840.28     .04       0
Bank Sta=462.9,483.6
XS Rating Curve= 0 ,0
Exp/Cntr(USF)=0,0
Exp/Cntr=0.3,0.1

Type RM Length L Ch R = 1 ,24387   ,223.6,237.9,249.9
XS GIS Cut Line= 4
1978721.14596723 195938.503981991979077.13157132195746.170527651
1979181.73397631195651.6909360461979520.84822475195477.915972915
#Sta/Elev= 30
       0  2414.2    33.1  2408.8    77.8 2397.04    96.5 2392.88   103.9 2392.02
   126.3 2391.03     186 2390.34   290.5 2390.09   372.4 2390.76   431.4 2390.34
   448.4 2389.01   470.6 2389.77   476.3  2389.4   480.9 2388.31   490.2 2387.91
   497.2 2389.35   548.4 2389.92   569.5 2388.71   595.3 2389.52   613.7 2391.53
   632.2 2390.57   665.6 2391.42   705.9 2393.98   790.7 2401.06     836 2403.89
   842.3 2404.66   853.3 2407.25   874.2 2407.39   890.2 2405.73 926.621 2408.14
#Mann= 7 ,-1 , 0
       0    .035       0     240     .08       0   476.3    .045       0
   497.2     .08       0  705.57     .12       0  825.57     .04       0
  926.62      .1       0
#XS Ineff= 2 , 0
          215.89 2393.29  613.19         2392.88
Permanent Ineff=
       F       F
Bank Sta=476.3,497.2
XS Rating Curve= 0 ,0
Exp/Cntr(USF)=0,0
Exp/Cntr=0.3,0.1

Type RM Length L Ch R = 1 ,24149   ,174.1,173.2,171.8
XS GIS Cut Line= 4
1978748.14013626196048.1677936741979149.67840058195886.202779494
1979313.33055033195865.9571527221979615.32781635195822.091628048
#Sta/Elev= 30
       0 2410.61    12.9 2408.74    28.2 2404.45    58.9 2392.35    69.5  2391.3
   147.3 2389.68   181.9 2389.96   239.9 2389.12   249.7 2389.78   366.7 2389.69
   380.8 2389.06   437.2 2389.09     457 2387.96   466.9 2389.66     505 2388.49
   513.2 2386.12   519.8 2385.81   523.1 2386.15   529.7 2388.72   592.5 2394.22
   668.4 2397.07   732.1 2401.02   761.6 2404.05   821.2 2408.55     836 2408.75
   850.8 2407.81   874.3 2408.85   884.2 2410.94   890.9 2413.64903.0391 2414.24
#Mann= 6 ,-1 , 0
       0     .08       0     505    .045       0   529.7     .08       0
  617.87     .12       0  707.87     .04       0  807.87      .1       0
#XS Ineff= 2 , 0
          178.41 2391.86
Permanent Ineff=
       F       F
Bank Sta=505,529.7
XS Rating Curve= 0 ,0
Exp/Cntr(USF)=0,0
Exp/Cntr=0.3,0.1

Type RM Length L Ch R = 1 ,23976   ,276.3,278.7,281.2
XS GIS Cut Line= 4
1978721.14596723196097.0947250411979183.42111187196048.167793674
1979416.24581975196017.7993535161979677.75183223195989.118048921
#Sta/Elev= 30
       0 2405.84    35.9 2403.16      92 2392.59   151.3  2390.5   174.4 2390.56
   200.8 2389.16     379 2389.18   408.7  2387.7   427.6 2388.32   438.4  2386.9
   448.3 2387.99   484.6 2388.61     521 2387.67   568.7 2388.24   577.5 2385.12
   583.9 2385.65   589.2 2388.25   600.4 2391.07   656.6 2398.27     680 2399.95
   689.7 2401.69   775.6 2408.43   822.4  2411.2   831.7 2410.96   841.6  2408.1
   864.7 2408.94   881.2 2407.96   887.8 2409.87   907.6 2412.78962.7282 2416.09
#Mann= 7 ,-1 , 0
       0    .035       0      20     .08       0   568.7    .045       0
   589.2     .08       0  709.65     .12       0  809.65     .04       0
  909.65     .06       0
#XS Ineff= 2 , 0
          236.88 2391.58
Permanent Ineff=
       F       F
Bank Sta=568.7,589.2
XS Rating Curve= 0 ,0
Exp/Cntr(USF)=0,0
Exp/Cntr=0.3,0.1

Type RM Length L Ch R = 1 ,23697   ,244.4,253.9,246.5
XS GIS Cut Line= 4
1978812.25128771  196397.40485551979180.04684074196309.673806153
1979330.20190597196309.6738061531979751.98579707196280.992501558
#Sta/Elev= 30
       0 2404.47    46.5 2402.61    64.4 2398.03    77.9 2395.82   141.8 2389.72
   327.5 2386.39   350.5 2387.11   364.6 2386.14   378.1 2387.06   391.2 2386.52
   410.9 2387.98   433.9 2387.14   460.1 2387.79   465.9 2385.21   473.3 2384.55
   482.3 2387.67   535.6 2388.22   575.1 2389.79   581.6 2389.41   588.2 2387.38
   614.5 2390.14   644.1 2391.41   704.7 2391.84     733 2394.38     776  2400.1
   808.5 2401.92   831.4 2407.65   854.6 2407.95   864.4  2406.4951.0272 2416.17
#Mann= 6 ,-1 , 0
       0     .08       0   460.1    .045       0   482.3     .08       0
  728.27     .12       0  818.27     .04       0  918.27     .12       0
#XS Ineff= 2 , 0
                          574.21         2391.73
Permanent Ineff=
       F       F
Bank Sta=460.1,482.3
XS Rating Curve= 0 ,0
Exp/Cntr(USF)=0,0
Exp/Cntr=0.3,0.1

Type RM Length L Ch R = 1 ,23443   ,273.7,354.4,281.2
XS GIS Cut Line= 4
 1978888.1723881196572.8669541951979159.80121397196523.940022828
1979330.20190597196529.001429521 1979726.6787636196459.828871382
#Sta/Elev= 30
       0 2411.05    26.5 2409.38    43.2  2407.5    59.9 2403.69    79.9 2396.23
    99.9 2390.04   113.2 2388.21   183.2 2386.98   250.1 2387.47   273.2 2386.76
   286.4 2385.28     293 2385.51   299.5 2386.88   309.4  2385.9   335.4 2387.14
   345.5 2384.83   352.1 2387.18   388.2 2386.96     398 2386.05     421 2387.08
   520.5 2387.02   580.5 2387.72   630.4 2390.57   647.1 2392.67     660 2393.32
   783.6 2407.02   810.3 2407.25   826.9 2406.28   836.9 2409.72848.9418 2410.56
#Mann= 7 ,-1 , 0
       0    .035       0      50     .08       0   335.4    .045       0
   352.1     .08       0  646.48     .12       0  746.48     .04       0
  846.48     .12       0
Bank Sta=335.4,352.1
XS Rating Curve= 0 ,0
Exp/Cntr(USF)=0,0
Exp/Cntr=0.3,0.1

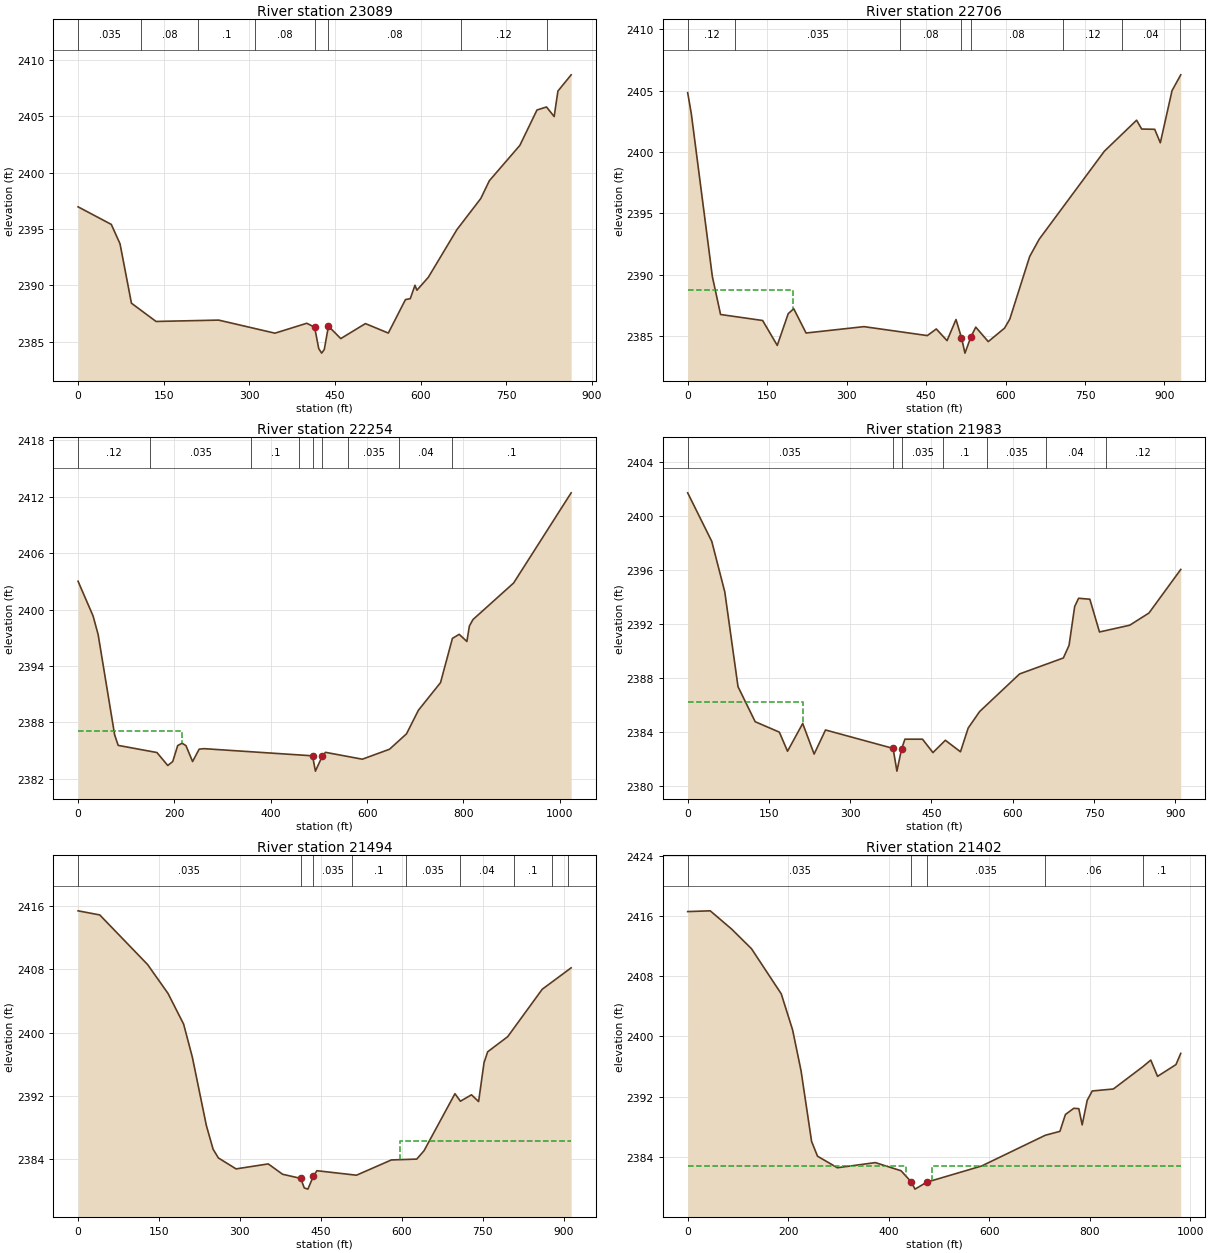
Type RM Length L Ch R = 1 ,23089   ,372,382.8,380
XS GIS Cut Line= 4
1978926.97650609 196775.323221921979277.90070348196719.647748296
1979397.68732855196655.5365968491979763.79574602 196586.36403871
#Sta/Elev= 30
       0 2396.98    58.2 2395.42    73.5  2393.7    93.5 2388.43   136.6 2386.81
   246.3 2386.93   344.9 2385.77   400.6 2386.65   414.4  2386.3   421.6  2384.4
   426.7    2384   431.3 2384.32   438.6 2386.39   460.2 2385.29   503.4 2386.62
   543.5 2385.78   573.5 2388.75   581.9 2388.83   590.2 2390.02   593.6 2389.58
   613.6 2390.73   663.7 2394.96   705.5 2397.72   720.4 2399.29   773.9 2402.43
   803.9 2405.57   820.6 2405.84     834 2404.99   840.6 2407.25863.7634 2408.69
#Mann= 8 ,-1 , 0
       0    .035       0     110     .08       0     210      .1       0
     310     .08       0   414.4    .045       0   438.6     .08       0
  671.18     .12       0  821.18     .04       0
Bank Sta=414.4,438.6
XS Rating Curve= 0 ,0
Exp/Cntr(USF)=0,0
Exp/Cntr=0.3,0.1

Type RM Length L Ch R = 1 ,22706   ,442.8,451.4,410.5
XS GIS Cut Line= 4
1978943.84786173197102.6275214091979382.50310847196959.220998437
1979554.59093603196915.355473763 1979826.2197619196809.065933208
#Sta/Elev= 30
       0 2404.83     6.9 2403.11    46.6 2389.84    62.1 2386.75   141.5 2386.26
   169.1 2384.23   189.8 2386.82   200.2 2387.22   223.5 2385.24   332.8 2385.76
   452.4 2385.03   469.3 2385.57   489.6 2384.62   506.5 2386.34   516.8 2384.87
   523.4  2383.6   534.5 2384.91   543.8 2385.72   567.4 2384.54   598.2 2385.64
   608.1 2386.38   645.6 2391.48   663.6 2392.89   786.5 2400.06   847.4 2402.59
     857 2401.87   881.6 2401.85   892.2 2400.75   914.3    2405930.7765 2406.29
#Mann= 8 ,-1 , 0
       0     .12       0      90    .035       0     400     .08       0
   516.8    .045       0   534.5     .08       0  709.09     .12       0
  819.09     .04       0  929.09     .12       0
#XS Ineff= 2 , 0
           199.4 2388.75
Permanent Ineff=
       F       F
Bank Sta=516.8,534.5
XS Rating Curve= 0 ,0
Exp/Cntr(USF)=0,0
Exp/Cntr=0.3,0.1

Type RM Length L Ch R = 1 ,22254   ,233.8,271.2,262.3
XS GIS Cut Line= 4
 1979087.2543847197360.7592627581979478.66983564197240.972637688
 1979655.8190699197178.5486218061980052.29592752197021.645014319
#Sta/Elev= 30
       0 2403.02    31.2 2399.32    41.7 2397.34    75.9 2386.68    83.3 2385.55
   163.7 2384.79   186.2 2383.41   196.5 2383.83   206.8 2385.53   215.9 2385.78
     224 2385.52   237.7 2383.83   251.4 2385.15   261.7  2385.2   486.7 2384.44
   492.7 2382.81   506.7 2384.38   513.6 2384.81   590.1 2384.08   646.5 2385.14
   681.8 2386.78   706.5 2389.29   752.4 2392.23   777.1 2396.94   791.2 2397.37
   807.1 2396.61   812.3 2398.25   819.7 2398.94   904.1 2402.831023.556 2412.43
#Mann= 9 ,-1 , 0
       0     .12       0     150    .035       0     360      .1       0
  459.33     .08       0   486.7    .045       0   506.7     .08       0
  559.33    .035       0  667.16     .04       0  777.16      .1       0
#XS Ineff= 2 , 0
          215.89 2387.06
Permanent Ineff=
       F       F
Bank Sta=486.7,506.7
XS Rating Curve= 0 ,0
Exp/Cntr(USF)=0,0
Exp/Cntr=0.3,0.1

Type RM Length L Ch R = 1 ,21983   ,472.1,489.4,467.1
XS GIS Cut Line= 4
1979197.98827653197529.2737265211979525.64356972197405.260766946
1979605.27294377197423.5363609891980051.71959824197252.529016733
#Sta/Elev= 30
       0 2401.69    44.5  2398.1    68.5 2394.37    92.9 2387.37   124.6 2384.78
   169.2 2384.01   184.3  2382.6   212.3 2384.65   233.4 2382.39   254.4 2384.17
   379.1 2382.81   386.2 2381.13  394.81 2382.77     401 2383.49   433.4 2383.49
   452.7  2382.5   475.6 2383.41   503.5 2382.56   517.7 2384.31   538.8 2385.53
   612.6 2388.31   693.4 2389.49   703.9 2390.42   714.3 2393.29   721.5  2393.9
   742.3 2393.83   760.1 2391.41   815.9 2391.91   851.4 2392.81   910.1 2396.03
#Mann= 7 ,-1 , 0
       0    .035       0   379.1    .045       0  394.81    .035       0
  472.04      .1       0  552.04    .035       0  662.04     .04       0
  772.04     .12       0
#XS Ineff= 2 , 0
          212.89 2386.27
Permanent Ineff=
       F       F
Bank Sta=379.1,394.81
XS Rating Curve= 0 ,0
Exp/Cntr(USF)=0,0
Exp/Cntr=0.3,0.1

Type RM Length L Ch R = 1 ,21494   ,64.3,91.8,105.2
XS GIS Cut Line= 4
1979218.56245854197631.1369088881979557.96520716 197627.32668193
1979713.18167908197595.2711062071980118.09421453197500.791514602
#Sta/Elev= 30
       0 2415.42    40.2  2414.9   128.8 2408.63   166.7 2404.97   195.6 2401.09
   211.8  2396.9   237.7 2388.28   250.2 2385.27   260.1 2384.16   292.8 2382.78
   352.4 2383.41     379  2382.1   412.5 2381.58   419.2 2380.37   425.9 2380.22
   435.9 2381.84   442.6 2382.55   515.9 2381.98   580.5 2383.91   627.6 2384.02
   641.1 2385.08   698.4 2392.29   708.5 2391.34     729 2392.15   742.2  2391.3
   752.3 2396.22     759 2397.59   796.1  2399.5   860.1  2405.5913.7052 2408.21
#Mann= 9 ,-1 , 0
       0    .035       0   412.5    .045       0   435.9    .035       0
  507.92      .1       0  607.92    .035       0  707.92     .04       0
  807.92      .1       0  877.92     .12       0  907.92      .1       0
#XS Ineff= 2 , 0
                           596.7         2386.37
Permanent Ineff=
       F       F
Bank Sta=412.5,435.9
XS Rating Curve= 0 ,0
Exp/Cntr(USF)=0,0
Exp/Cntr=0.5,0.3

Type RM Length L Ch R = 1 ,21402   ,62.5,47.7,46
XS GIS Cut Line= 4
1979223.72593694197647.6549783451979595.65429725197664.258923002
1979790.47391455197720.7123348351980190.07551596197792.662761681
#Sta/Elev= 30
       0 2416.56    44.9 2416.66    87.6 2414.23     127 2411.63   186.2 2405.64
   208.8 2400.85   225.6 2395.43   246.6 2386.04   258.4 2384.09   297.8 2382.56
   373.4 2383.24   424.6 2382.16   445.1 2380.66   452.3 2379.72   476.1 2380.65
   584.9 2382.79   711.6 2386.87   740.7 2387.39   751.6 2389.62   768.3 2390.45
   778.3  2390.4     785 2388.25     795 2391.51     805 2392.75     847 2393.01
   905.5 2395.96   921.5 2396.85     935 2394.69   971.6 2396.25981.1603 2397.74
#Mann= 5 ,-1 , 0
       0    .035       0   445.1    .045       0   476.1    .035       0
   711.6     .06       0   905.5      .1       0
#XS Ineff= 2 , 0
             435 2382.81     486         2382.81
Permanent Ineff=
       F       F
Bank Sta=445.1,476.1
XS Rating Curve= 0 ,0
Exp/Cntr(USF)=0,0
Exp/Cntr=0.5,0.3

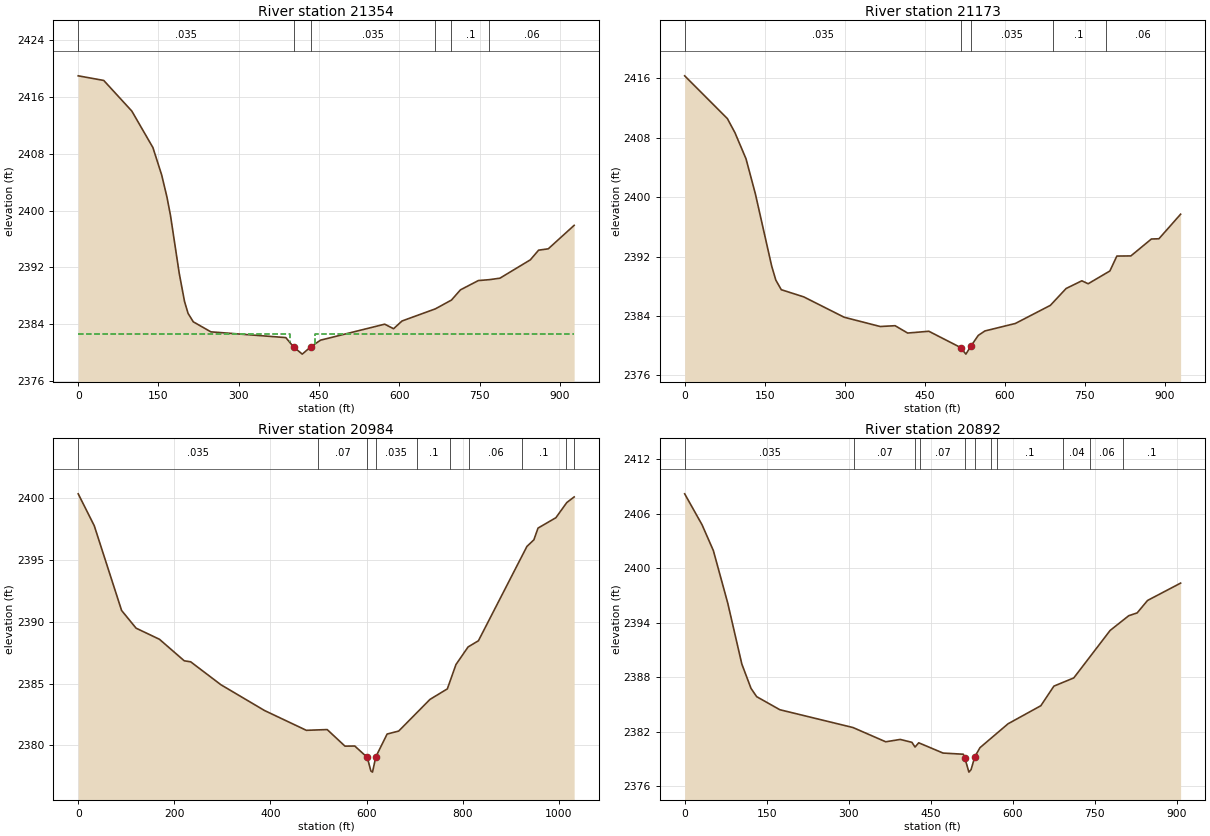
Type RM Length L Ch R = 1 ,21354   ,192.8,181,167
XS GIS Cut Line= 4
1979263.57540411197680.8628676581979518.16922218197687.504445521
1979865.74513033197790.4489023931980169.04385273197852.436962445
#Sta/Elev= 30
       0 2418.99    47.7 2418.34   100.2 2414.02   139.6 2408.88     156 2405.01
   165.9 2401.88   172.4 2399.33   188.8 2391.15   198.7 2387.18   205.3 2385.51
   215.1 2384.32   247.9 2382.91   387.9  2382.1   402.6 2380.77   418.7 2379.77
   435.2 2380.84   452.9 2381.74   572.7 2383.99   589.3 2383.35   605.1 2384.44
   667.4 2386.15   697.5 2387.39   714.3 2388.83   747.8 2390.14   767.9 2390.26
     788 2390.47   844.9 2393.06   860.3 2394.42   878.4 2394.61926.7493 2397.92
#Mann= 6 ,-1 , 0
       0    .035       0   402.6    .045       0   435.2    .035       0
   667.4     .06       0   697.5      .1       0   767.9     .06       0
#XS Ineff= 2 , 0
          395.37 2382.63  441.68         2382.62
Permanent Ineff=
       F       F
Bank Sta=402.6,435.2
XS Rating Curve= 0 ,0
Exp/Cntr(USF)=0,0
Exp/Cntr=0.5,0.3

Type RM Length L Ch R = 1 ,21173   ,189.2,189.7,184.9
XS GIS Cut Line= 4
1979252.50610767197769.4172391611979628.86218656197906.676514991
1979845.82039674197879.003273896  1980155.760697197877.896344252
#Sta/Elev= 30
       0 2416.36      80  2410.6    94.2  2408.7   114.9 2405.19   132.4 2400.48
   163.1 2390.71   170.8 2388.84     181 2387.55   223.2 2386.58   298.8 2383.84
   366.4 2382.59   394.3  2382.7   417.8 2381.71   457.5 2381.95     517 2379.76
   526.9 2378.87   536.9 2380.01   550.1 2381.39   562.5 2381.99   619.6    2383
   685.2 2385.44   714.7 2387.71   744.2 2388.75     756 2388.35   796.7 2390.07
   809.8 2392.08   836.1  2392.1   874.5 2394.38   888.6 2394.41929.2628 2397.72
#Mann= 5 ,-1 , 0
       0    .035       0     517    .045       0   536.9    .035       0
  689.32      .1       0  789.32     .06       0
Bank Sta=517,536.9
XS Rating Curve= 0 ,0
Exp/Cntr(USF)=0,0
Exp/Cntr=0.3,0.1

Type RM Length L Ch R = 1 ,20984   ,100.6,92,83.1
XS GIS Cut Line= 4
1979229.26058515198180.0881370061979753.94523631198077.143680134
1979870.17284891198049.4704390391980214.42796813197893.393359265
#Sta/Elev= 30
       0 2400.34    33.4 2397.76    90.3 2390.91   120.4 2389.48   169.1 2388.58
   220.7 2386.84     234 2386.76   297.2  2384.9   387.8 2382.82   474.8 2381.22
   518.2 2381.28   555.2 2379.94   575.6 2379.95   601.6 2379.03   609.1 2377.93
   612.5 2377.84   619.3 2379.07   642.9 2380.92     667 2381.16   732.1 2383.72
   768.2 2384.57   786.2 2386.54   811.4 2387.96   832.9 2388.46   933.9 2396.09
   948.3 2396.62     957 2397.57   994.2 2398.41  1016.7 2399.631032.149 2400.09
#Mann= 10 ,-1 , 0
       0    .035       0     500     .07       0   601.6    .045       0
   619.3    .035       0  704.16      .1       0  774.16    .035       0
  814.16     .06       0  924.16      .1       0 1014.16     .06       0
 1032.15     .04       0
Bank Sta=601.6,619.3
XS Rating Curve= 0 ,0
Exp/Cntr(USF)=0,0
Exp/Cntr=0.3,0.1

Type RM Length L Ch R = 1 ,20892   ,176.5,157.6,135
XS GIS Cut Line= 4
1979472.29313806198443.2914078621979772.39406371198225.595244584
1979995.00991429198038.6471269671980206.55646844197914.425022498
#Sta/Elev= 30
       0  2408.2    31.7  2404.8    52.4 2401.96    78.7 2396.18   104.5 2389.46
   121.3 2386.78   131.6 2385.87     174 2384.43   307.7 2382.47   367.6  2380.9
   394.1 2381.16   415.5 2380.84   421.2 2380.32   427.9 2380.79   472.4 2379.66
   509.5 2379.53     512 2379.17   519.7 2377.56   523.6 2377.83   530.6 2379.27
   539.9 2380.25   591.2 2382.88   651.2 2384.87   675.1 2387.03   711.4 2387.93
   777.9 2393.16   811.9 2394.78   827.3 2395.09   846.3 2396.46906.7694 2398.37
#Mann= 11 ,-1 , 0
       0    .035       0     310     .07       0  420.75    .035       0
  430.75     .07       0     512    .045       0   530.6     .07       0
  560.75     .04       0  570.75      .1       0  691.45     .04       0
  741.45     .06       0  801.45      .1       0
Bank Sta=512,530.6
XS Rating Curve= 0 ,0
Exp/Cntr(USF)=0,0
Exp/Cntr=0.5,0.3