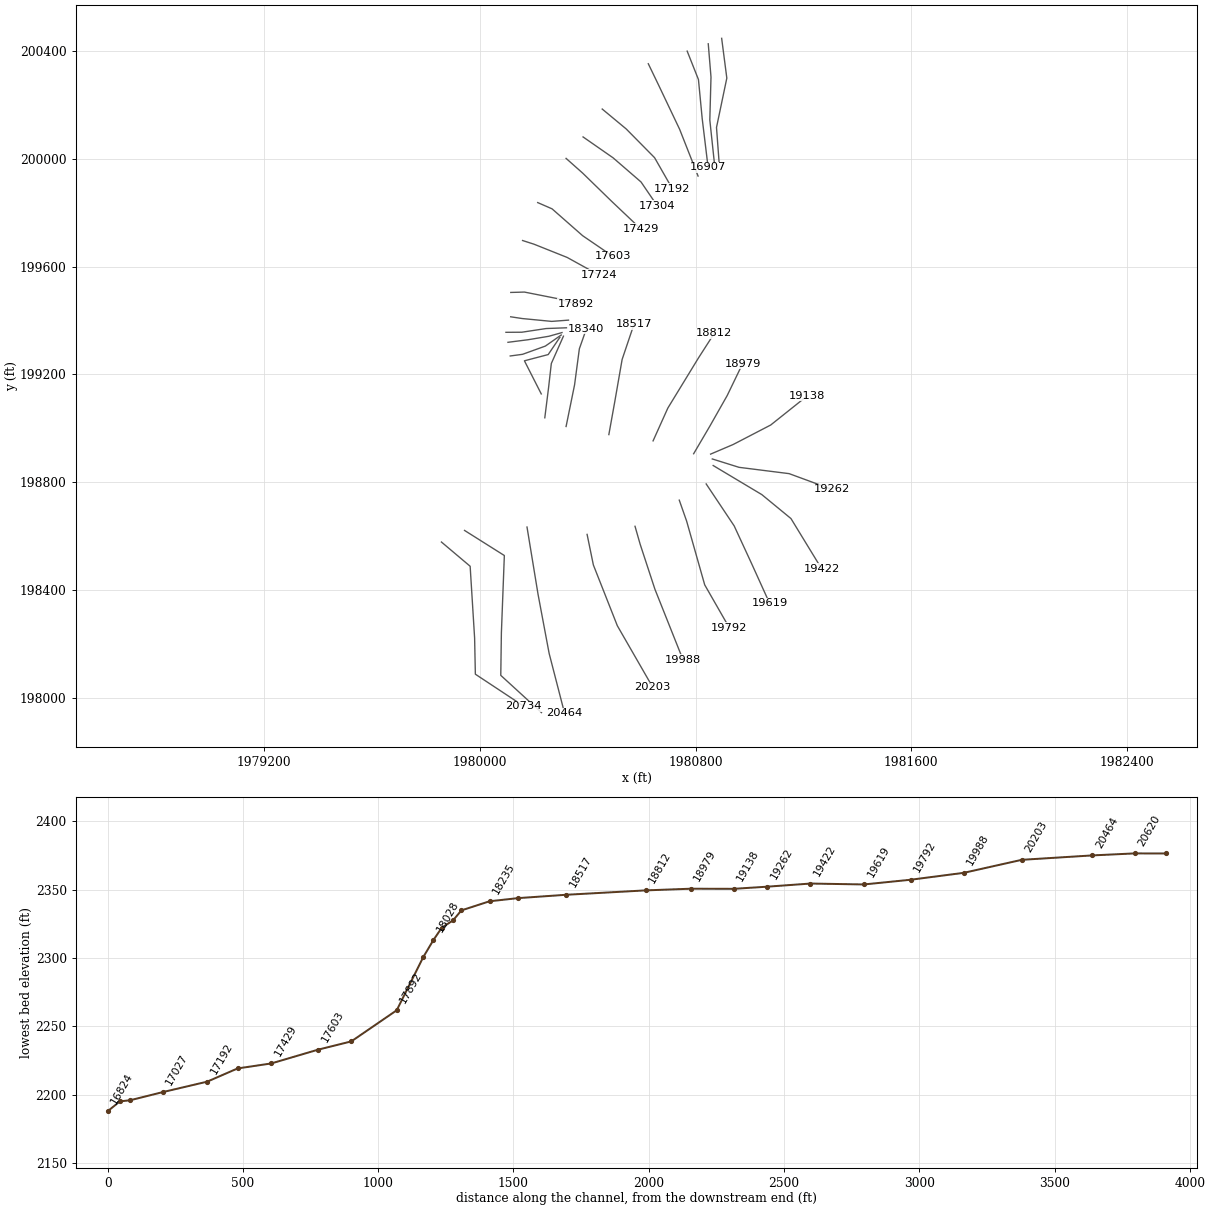
HEC-RAS study PIPESTCK2_A.prj: PIPESTCK2_A

--- PIPESTCK2_A.g01 (geometry) --- (continued)

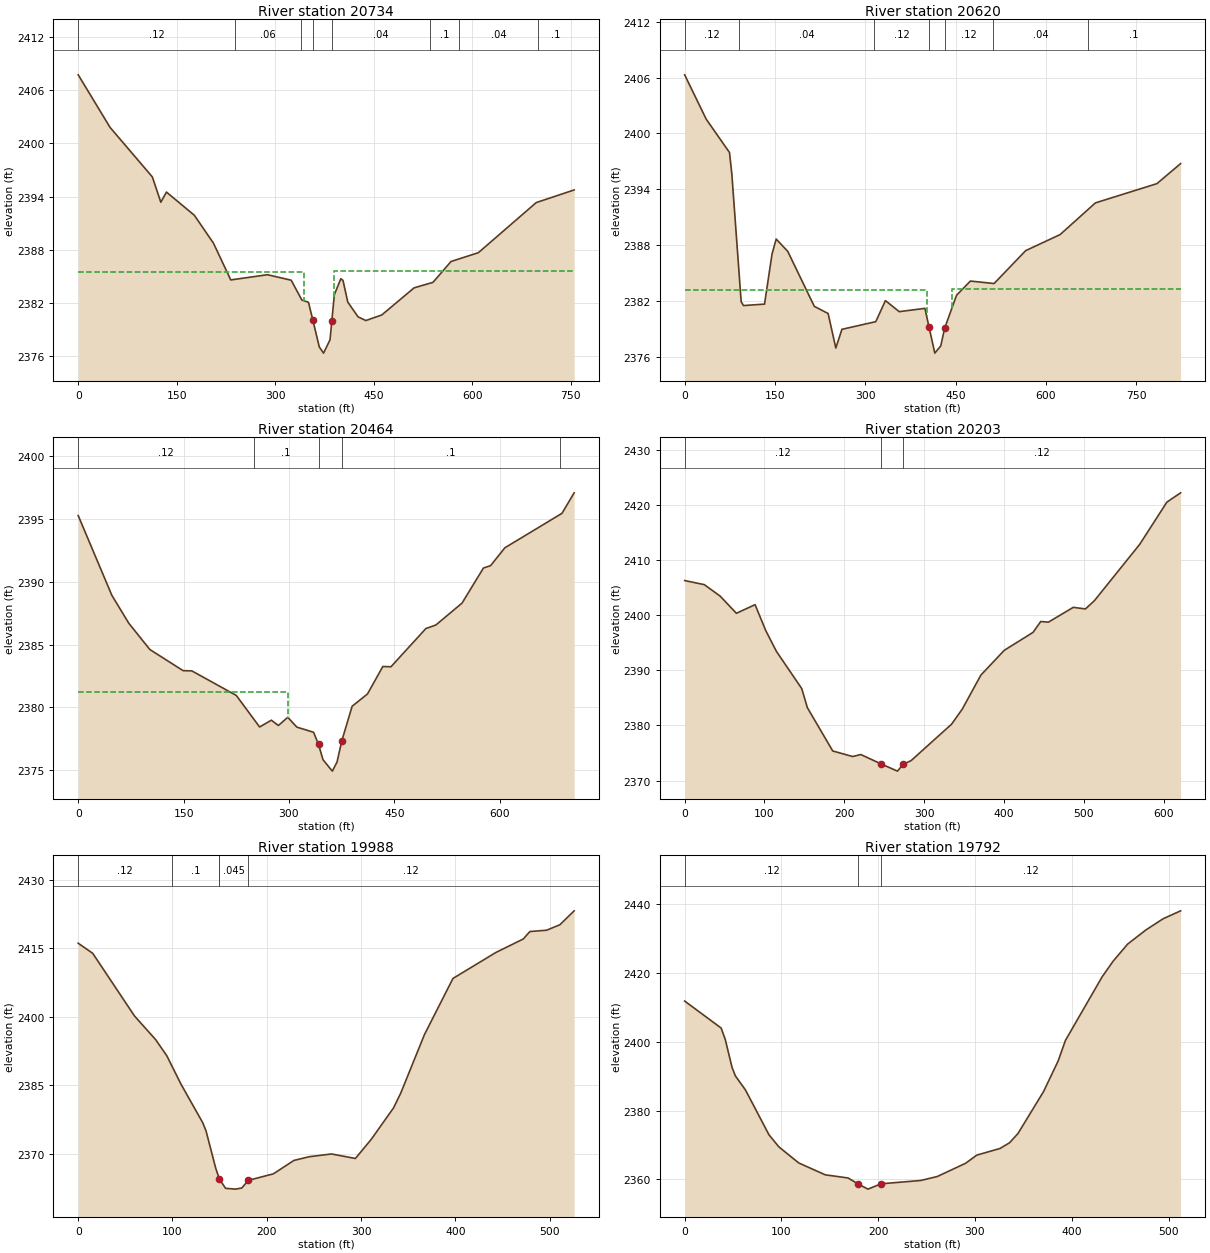
Type RM Length L Ch R = 1 ,20734   ,112.6,114.2,114.1
XS GIS Cut Line= 5
1979858.19260083198578.268752599 1979964.6461422198488.359243921
     1979981.211198221.6360000221979983.94061786198087.844000027
1980163.23547521197969.206109345
#Sta/Elev= 30
       02407.733  48.5262401.804 112.9422396.217 125.8252393.364 134.414 2394.51
 176.9452391.891 206.062 2388.74 232.3592384.603 288.241 2385.19 324.3992384.572
 340.6752382.331 350.6972382.087 357.2712380.117 367.1322377.056 373.7072376.348
 383.5682377.855 386.2382379.938 390.1432382.942 400.004 2384.74 403.2912384.549
 410.5862382.107 426.2672380.441 438.1062380.023 462.364 2380.65 511.5872383.708
 540.3992384.333 567.8252386.681 609.5092387.675 697.6492393.327 755.391 2394.75
#Mann= 8 ,-1 , 0
       0     .12       0  239.34     .06       0  339.34     .04       0
 357.271    .045       0 386.238     .04       0  536.58      .1       0
   580.4     .04       0   700.4      .1       0
#XS Ineff= 2 , 0
          344.23 2385.54  389.81         2385.61
Permanent Ineff=
       F       F
Bank Sta=357.271,386.238
XS Rating Curve= 0 ,0
Exp/Cntr(USF)=0,0
Exp/Cntr=0.5,0.3

Type RM Length L Ch R = 1 ,20620   ,148.7,155.9,161.4
XS GIS Cut Line= 5
 1979943.8391418198621.3270944081980091.41011596198528.199349959
1980080.40571314198240.4529303911980078.17464507198083.523724049
1980229.06022701 197945.31404151
#Sta/Elev= 30
       02406.291   35.672401.542  74.4662397.946  78.3452395.653  93.8632381.924
  97.7432381.509 132.6582381.664 145.1382387.046 152.0562388.651 171.3012387.327
 215.3442381.428 238.3272380.655 251.1082376.946  261.312378.958 317.5162379.779
 333.5412382.042 356.5232380.855 399.2052381.208 406.0612379.171 415.622  2376.4
 425.4712377.174 432.0382379.094 451.7372382.618 474.712 2384.14 514.0862383.876
 566.5852387.408 623.7882389.132 682.4522392.537 784.6262394.603 824.0192396.755
#Mann= 7 ,-1 , 0
       0     .12       0      90     .04       0   314.5     .12       0
 406.061    .045       0 432.038     .12       0  512.46     .04       0
   669.4      .1       0
#XS Ineff= 2 , 0
           401.8 2383.17  443.78         2383.24
Permanent Ineff=
       F       F
Bank Sta=406.061,432.038
XS Rating Curve= 0 ,0
Exp/Cntr(USF)=0,0
Exp/Cntr=0.5,0.3

Type RM Length L Ch R = 1 ,20464   ,254.7,261.1,265.1
XS GIS Cut Line= 4
1980175.39844883198633.9292909591980216.39584305198383.845186252
1980257.39323726198165.1924171091980314.78958916197942.439908544
#Sta/Elev= 30
       0 2395.26    47.9 2388.92      72  2386.7     102 2384.61   149.3 2382.93
   161.8 2382.91     225 2380.96   258.2 2378.45   274.9 2378.99   284.9 2378.57
   298.3 2379.22   311.2 2378.44     335 2378.03   342.1 2377.06   348.4 2375.85
   361.7 2374.94   368.4 2375.66   375.1 2377.33   389.9  2380.1   411.8 2381.08
   433.6 2383.26   445.2 2383.24   494.9 2386.28   509.1 2386.56   546.3  2388.3
   576.8 2391.09     587 2391.28   607.3  2392.7   688.6 2395.44705.9136 2397.07
#Mann= 5 ,-1 , 0
       0     .12       0     250      .1       0   342.1    .045       0
   375.1      .1       0  685.89    .035       0
#XS Ineff= 2 , 0
          298.65 2381.24
Permanent Ineff=
       F       F
Bank Sta=342.1,375.1
XS Rating Curve= 0 ,0
Exp/Cntr(USF)=0,0
Exp/Cntr=0.3,0.1

Type RM Length L Ch R = 1 ,20203   ,212.3,214.7,209.4
XS GIS Cut Line= 4
 1980398.1509574198606.5976948161980421.38281412198493.171570823
1980510.21050158198267.6859026441980641.40216307198039.467074851
#Sta/Elev= 30
       0  2406.3    24.6 2405.56    44.5 2403.47    64.8 2400.36    88.2 2401.93
   101.6 2397.22     115 2393.44   146.7 2386.69   153.7 2383.24   185.5 2375.38
   210.4 2374.37   220.7 2374.73   245.4 2373.07   266.6 2371.72   273.6 2372.93
   273.6 2372.94   283.8 2373.64   334.4 2380.24   347.7 2382.95   371.2 2389.16
   400.4 2393.64   436.5  2396.9   446.1 2398.87   455.7 2398.75   486.9 2401.44
   502.1 2401.15   513.3 2402.64   570.2 2412.89   604.2 2420.54621.3717 2422.22
#Mann= 3 ,-1 , 0
       0     .12       0   245.4    .045       0   273.6     .12       0
Bank Sta=245.4,273.6
XS Rating Curve= 0 ,0
Exp/Cntr(USF)=0,0
Exp/Cntr=0.3,0.1

Type RM Length L Ch R = 1 ,19988   ,195,196.6,194.1
XS GIS Cut Line= 4
1980575.80633233198636.6624505731980594.93844963198569.700040023
1980649.60164191198402.9773035521980753.46170726198141.960560387
#Sta/Elev= 30
       0 2416.11    15.4 2413.89    59.7 2400.16    82.2 2394.96    94.1 2391.39
     109 2385.22   132.1 2376.75   135.6 2374.94   145.9 2366.75   149.8 2364.39
   156.3 2362.38   166.6  2362.2   173.5 2362.44   180.4 2364.12     207 2365.55
   228.8 2368.49   245.1 2369.31   268.7 2369.91     294 2368.92   310.8 2373.11
   334.4 2379.99     342  2383.2   367.2 2396.06   397.5 2408.39     443 2414.08
     472 2417.03   479.1 2418.67   496.8 2418.96   510.9 2420.16526.0182 2423.21
#Mann= 5 ,-1 , 0
       0     .12       0   99.64      .1       0  149.64     .12       0
   149.8    .045       0   180.4     .12       0
Bank Sta=149.8,180.4
XS Rating Curve= 0 ,0
Exp/Cntr(USF)=0,0
Exp/Cntr=0.3,0.1

Type RM Length L Ch R = 1 ,19792   ,168.8,172.3,175.7
XS GIS Cut Line= 4
1980739.79590918198733.6896168811980767.12750533198655.794567873
1980834.08991588198419.3762612371980925.65076296198259.486423801
#Sta/Elev= 30
       0 2411.81    37.7 2403.96      42 2400.59    48.9 2392.58    52.4 2390.06
    62.8 2385.98    87.1 2372.95    97.4 2369.42   117.8 2364.77   145.2 2361.31
   168.9 2360.39   179.2 2358.65   189.4 2357.15     203  2358.7   243.9 2359.66
     261 2360.81   290.3 2364.66     302 2367.05   325.8 2368.95   335.8 2370.64
   344.4  2373.3   370.9 2385.51     386 2394.42   393.5 2400.38   431.4 2418.84
   442.7 2423.37   457.8 2428.37   476.7 2432.48   494.4 2435.72512.5197 2438.03
#Mann= 3 ,-1 , 0
       0     .12       0   179.2    .045       0     203     .12       0
Bank Sta=179.2,203
XS Rating Curve= 0 ,0
Exp/Cntr(USF)=0,0
Exp/Cntr=0.3,0.1

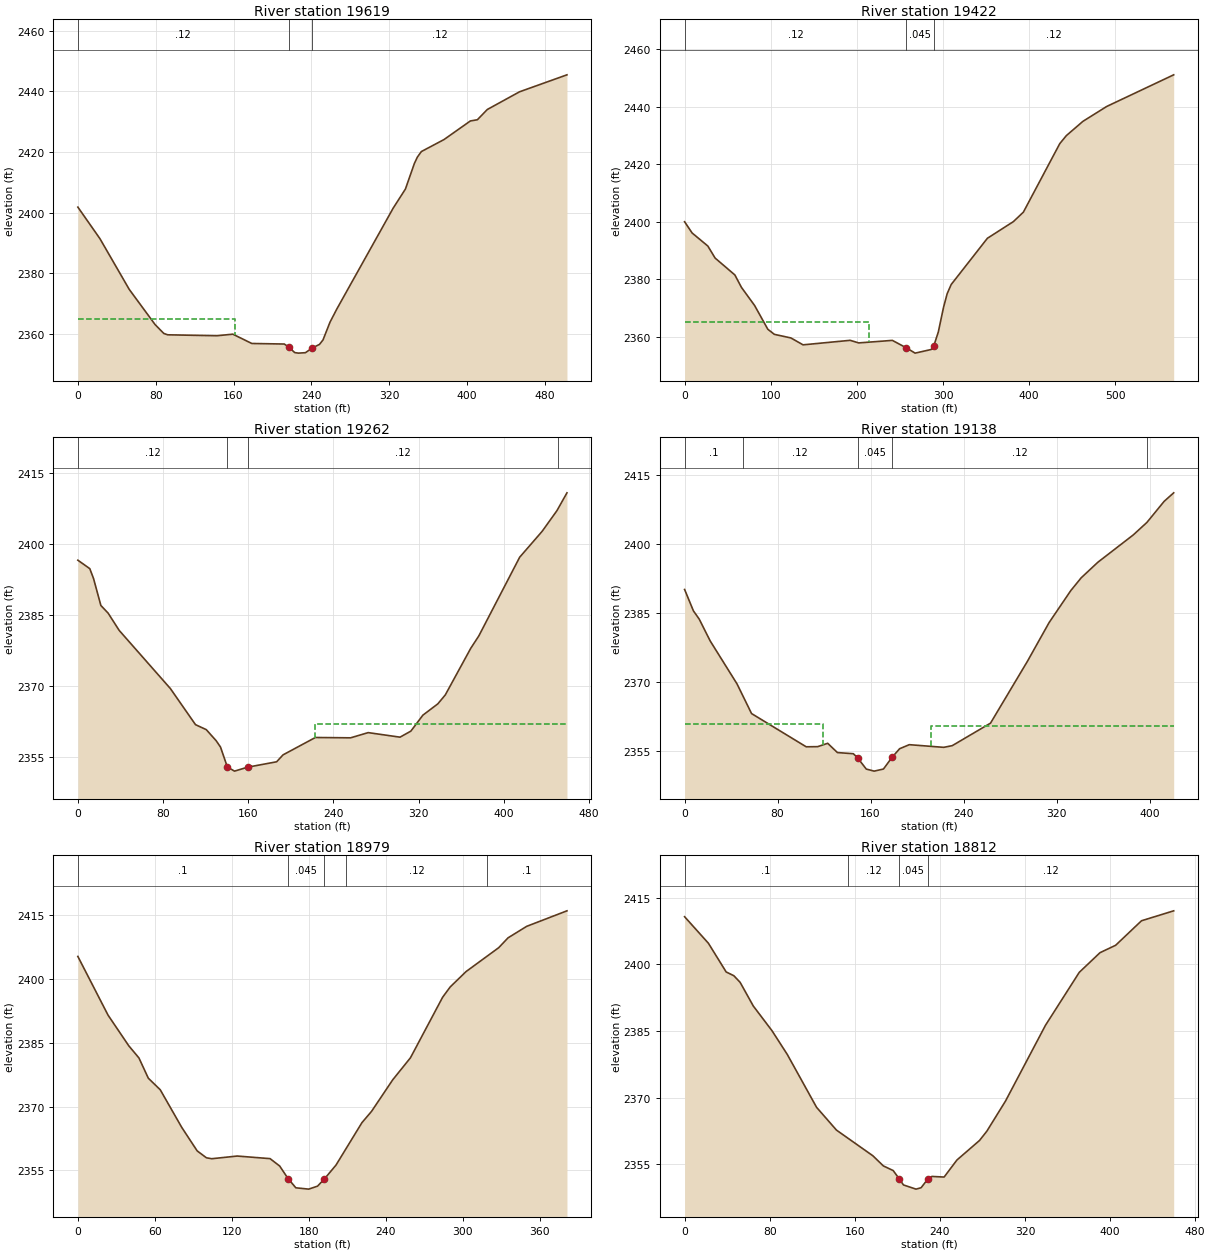
Type RM Length L Ch R = 1 ,19619   ,185.5,197.5,200.5
XS GIS Cut Line= 4
1980839.55623511198793.8191283951980943.41630045 198638.02903038
1981009.01213119198495.9047304371981074.60796193 198351.04727088
#Sta/Elev= 30
       0 2401.86    22.7 2391.45    52.8 2374.74    79.4 2363.13    88.3 2360.22
    92.3 2359.76     143 2359.45   159.3 2359.97   178.8  2356.9   212.2 2356.72
   216.7 2355.74   222.9  2353.9   226.7 2353.72   233.9 2353.86   241.1 2355.43
   248.4  2356.6     252 2358.07   259.2 2363.93   266.4 2368.38   324.2 2401.56
   336.7 2407.81   345.9 2416.23     349 2418.34   353.1 2420.18   376.3 2424.12
   403.5 2430.27   410.7 2430.67   420.9 2434.05     454 2439.88502.7852 2445.48
#Mann= 3 ,-1 , 0
       0     .12       0   216.7    .045       0   241.1     .12       0
#XS Ineff= 2 , 0
          161.02 2365.02
Permanent Ineff=
       F       F
Bank Sta=216.7,241.1
XS Rating Curve= 0 ,0
Exp/Cntr(USF)=0,0
Exp/Cntr=0.3,0.1

Type RM Length L Ch R = 1 ,19422   ,158.1,159.9,182
XS GIS Cut Line= 4
1980865.52125144198862.1481187521981045.90978598198754.188313988
1981153.86959075198665.3606265231981267.29571474198479.505772752
#Sta/Elev= 30
       0 2400.05     8.7 2396.15      27  2391.6    35.4 2387.43    58.4 2381.54
      66 2377.23    81.3 2370.92    96.6 2362.68   104.2 2360.91   123.4 2359.66
   137.5 2357.26   192.2 2358.83   202.1 2357.93   241.2 2358.81   257.2 2356.25
   267.6 2354.38   286.2 2355.64   289.3 2356.94   294.5 2361.69   300.6 2370.32
   304.8 2375.03   309.5 2378.24   351.5  2394.3   381.7  2400.1   393.3  2403.4
   435.5 2427.19   443.2    2430   462.4 2434.95     490 2440.12567.7654 2451.12
#Mann= 3 ,-1 , 0
       0     .12       0   257.2    .045       0   289.3     .12       0
#XS Ineff= 2 , 0
           214.3 2365.07
Permanent Ineff=
       F       F
Bank Sta=257.2,289.3
XS Rating Curve= 0 ,0
Exp/Cntr(USF)=0,0
Exp/Cntr=0.3,0.1

Type RM Length L Ch R = 1 ,19262   ,111,124.3,142.5
XS GIS Cut Line= 4
1980862.22163948198886.5417752711980961.25562841198855.488332897
1981147.01951727198832.0508328831981305.00562841198773.891110659
#Sta/Elev= 30
       0 2396.62    11.2 2394.83    14.7 2392.76    21.6 2387.06    28.4 2385.45
    38.8  2381.8    86.9 2369.52   110.5  2361.9   120.6 2360.85   129.9 2358.51
     134 2357.16   140.4 2352.97   147.1 2352.09  159.61 2352.93   186.7 2354.06
   192.7 2355.52   223.1 2359.19   256.2 2359.12   272.7 2360.22   302.6 2359.26
   312.8 2360.54   324.1 2363.91   338.1 2366.29   345.1 2368.17     369 2378.01
   376.6 2380.63     415 2397.25     436 2402.69     450 2407.08   459.4 2410.84
#Mann= 4 ,-1 , 0
       0     .12       0   140.4    .045       0  159.61     .12       0
  451.03      .1       0
#XS Ineff= 2 , 0
                          222.64         2361.98
Permanent Ineff=
       F       F
Bank Sta=140.4,159.61
XS Rating Curve= 0 ,0
Exp/Cntr(USF)=0,0
Exp/Cntr=0.3,0.1

Type RM Length L Ch R = 1 ,19138   ,145.5,158.7,173.6
XS GIS Cut Line= 4
1980855.95519279198904.5120927741980939.31656103198940.043167759
1981078.70770136199012.4718975381981213.99910226199120.431702302
#Sta/Elev= 30
       0 2390.08     7.6 2385.42    12.6 2383.62      22 2378.88    45.1 2369.52
    57.6 2363.06   104.6 2355.82   114.5 2355.85   123.1 2356.58   131.5 2354.56
   145.2 2354.31   148.9 2353.39   156.3 2350.97   163.1 2350.52   171.1 2350.98
   178.5 2353.53     185  2355.4   193.3 2356.28   222.9  2355.7   230.3 2356.07
   263.2 2360.97     295 2374.46   313.6 2382.87   332.3 2389.85   341.2 2392.62
   355.6 2396.02     386 2401.96   397.7 2404.67   412.6 2409.28  420.79 2411.13
#Mann= 5 ,-1 , 0
       0      .1       0      50     .12       0   148.9    .045       0
   178.5     .12       0   397.7      .1       0
#XS Ineff= 2 , 0
          119.19 2360.68  212.14         2360.44
Permanent Ineff=
       T       F
Bank Sta=148.9,178.5
XS Rating Curve= 0 ,0
Exp/Cntr(USF)=0,0
Exp/Cntr=0.3,0.1

Type RM Length L Ch R = 1 ,18979   ,167.5,166.8,166.1
XS GIS Cut Line= 4
1980793.09252166198905.8786725811980853.22203318199008.372158117
1980917.45128411 199121.798282111980974.84763601199240.690725331
#Sta/Elev= 30
       0 2405.32    23.5 2391.53    39.7  2384.3    47.6 2381.45    54.9 2376.69
    64.2 2373.97      81  2365.1      93 2359.59   100.2 2357.97   104.4 2357.75
   124.2 2358.38   149.8 2357.77   157.3 2356.03   163.9 2353.04   169.9 2350.91
   179.9  2350.6   186.8  2351.3   192.2 2353.01   201.2 2356.26   221.4 2366.23
   228.9 2368.89   245.4 2376.31   259.2 2381.48   284.3 2395.73   290.2 2398.15
   302.5 2401.75     328 2407.38   335.3  2409.7   349.8  2412.4381.2005 2416.05
#Mann= 5 ,-1 , 0
       0      .1       0   163.9    .045       0   192.2      .1       0
  208.83     .12       0  319.18      .1       0
Bank Sta=163.9,192.2
XS Rating Curve= 0 ,0
Exp/Cntr(USF)=0,0
Exp/Cntr=0.3,0.1

Type RM Length L Ch R = 1 ,18812   ,280.6,294.6,298.8
XS GIS Cut Line= 4
1980642.76874288198953.7089658311980697.43193516199075.334568667
1980810.85805916199261.1894224381980869.62099086199352.750269517
#Sta/Elev= 30
       0 2410.76    22.4 2404.78    39.1 2398.31    46.3 2397.47    52.2 2395.98
    64.6 2390.64    82.2 2385.07    96.6 2379.71   124.1 2367.81   142.8 2362.68
     177  2356.9   186.9 2354.61   196.1 2353.57   201.7 2351.74   205.8 2350.32
   217.6 2349.38   222.4  2349.7   228.6 2351.62   232.5 2352.24     244  2352.1
   256.1 2355.95   277.3 2360.34   284.2 2362.44   301.7 2369.21   339.3 2386.29
   371.1 2398.23   390.6 2402.66   405.3 2404.33   429.6 2409.85459.8731 2412.09
#Mann= 4 ,-1 , 0
       0      .1       0  153.34     .12       0   201.7    .045       0
   228.6     .12       0
Bank Sta=201.7,228.6
XS Rating Curve= 0 ,0
Exp/Cntr(USF)=0,0
Exp/Cntr=0.3,0.1

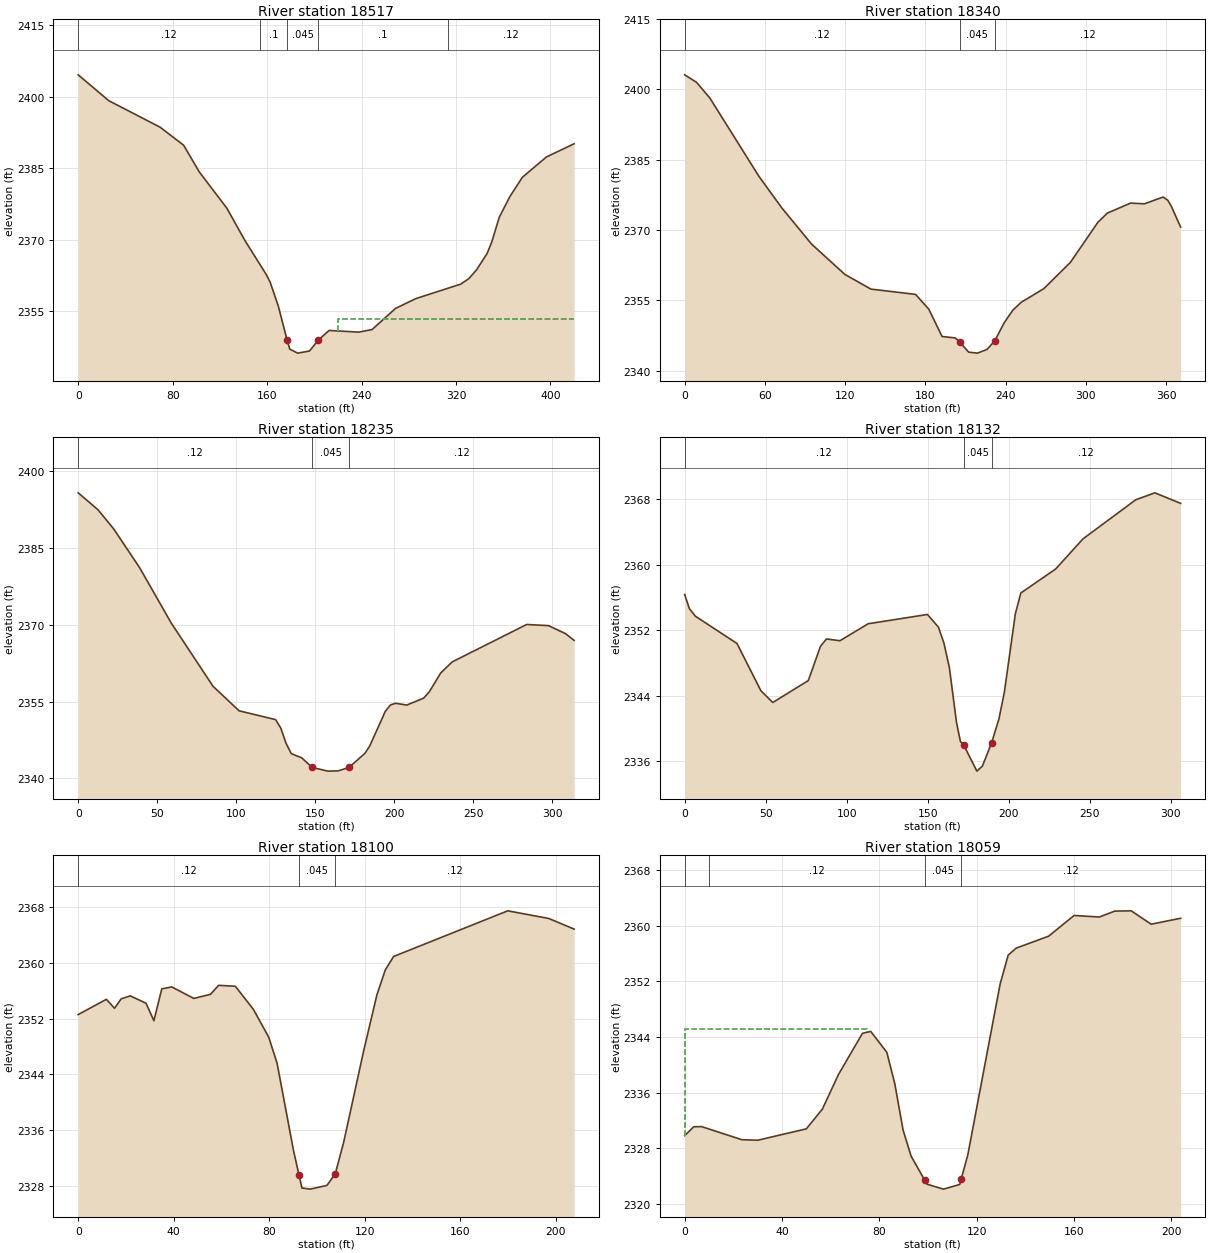
Type RM Length L Ch R = 1 ,18517   ,175.7,177.8,175.4
XS GIS Cut Line= 4
1980478.77916602198976.9408225521980500.64444293199098.566425388
1980527.97603908 199255.72310321 1980571.7065929199385.548184889
#Sta/Elev= 30
       0  2404.6    25.9 2399.17    69.3 2393.61    89.3 2389.82   102.6  2384.2
   125.9  2376.6   141.1 2369.86   159.2 2362.69   162.6 2361.06   169.5 2356.03
   176.9 2348.95   179.2    2347   185.9 2346.16   195.9  2346.6   203.5 2348.93
   212.5 2350.92   237.6 2350.57   248.9 2351.11   268.8 2355.55   285.9  2357.6
     324 2360.65   330.9 2361.81   337.4 2363.64   346.3 2367.06   350.3 2369.49
   356.6 2374.66   365.5 2378.97   376.2 2383.08   396.7 2387.37420.0834 2390.13
#Mann= 5 ,-1 , 0
       0     .12       0  153.58      .1       0   176.9    .045       0
   203.5      .1       0  313.09     .12       0
#XS Ineff= 2 , 0
                          219.64         2353.29
Permanent Ineff=
       F       F
Bank Sta=176.9,203.5
XS Rating Curve= 0 ,0
Exp/Cntr(USF)=0,0
Exp/Cntr=0.3,0.1

Type RM Length L Ch R = 1 ,18340   ,102.5,104.2,105.1
XS GIS Cut Line= 4
1980320.25590839 199007.005578311980351.68724395199161.429096517
1980369.45278145199295.3539176171980395.41779778199369.149227203
#Sta/Elev= 30
       0 2403.13     8.8 2401.55    18.8 2398.19    55.6 2381.43    72.6 2374.74
    94.8 2367.02   119.8 2360.52   139.3 2357.38   172.7 2356.25   182.6 2353.09
   192.5 2347.26   202.4 2346.95   205.6 2346.12   212.4 2343.92     219 2343.71
   226.1  2344.5   231.9 2346.31   238.8 2350.12   245.5  2352.9   251.7 2354.57
   268.6 2357.47   288.5 2363.09   309.1 2371.67   316.1  2373.6   333.5 2375.74
   343.9 2375.59   357.8 2377.04   361.3 2376.35   363.9 2375.11370.9178 2370.63
#Mann= 3 ,-1 , 0
       0     .12       0   205.6    .045       0   231.9     .12       0
Bank Sta=205.6,231.9
XS Rating Curve= 0 ,0
Exp/Cntr(USF)=0,0
Exp/Cntr=0.3,0.1

Type RM Length L Ch R = 1 ,18235   ,125.7,103.9,76.5
XS GIS Cut Line= 4
1980241.36539869199039.2694759651980255.18267769199149.807707988
1980265.54563695199240.7714614231980310.45179371 199342.09817411
#Sta/Elev= 30
       0 2395.73    12.5 2392.43    22.4 2388.71      39 2381.05    58.8 2370.35
    85.3 2357.98   101.8 2353.19   124.9 2351.47   128.2  2349.8   131.5 2346.86
   134.8 2344.84   141.4 2344.02     148 2342.16   157.9 2341.42   164.5 2341.47
   171.42342.153   181.4 2344.89   184.4 2346.29   194.3 2353.08   197.6 2354.34
   200.9 2354.66   207.9 2354.31   218.6 2355.67   222.2 2356.92   229.4 2360.59
   236.6 2362.73   283.8 2370.04   297.6 2369.81   308.3 2368.26   313.8 2366.93
#Mann= 3 ,-1 , 0
       0     .12       0     148    .045       0   171.4     .12       0
Bank Sta=148,171.4
XS Rating Curve= 0 ,0
Exp/Cntr(USF)=0,0
Exp/Cntr=0.3,0.1

Type RM Length L Ch R = 1 ,18132   ,29.6,31,32.6
XS GIS Cut Line= 4
1980228.25039879199127.8672052061980165.81581134199250.773846247
1980253.97712202199273.9392881741980297.20020921199337.835660314
#Sta/Elev= 30
       02356.339   2.8712354.631   6.5512353.696   32.312350.356   47.032344.593
   54.392343.154  76.3182345.829  83.8292350.009  87.5082350.912   95.842350.694
 113.2682352.768  149.852353.901 156.6352352.358 160.0272350.413 163.4192347.395
 167.7842340.738 170.2032338.404 172.3862337.908  180.382334.773 183.7722335.382
 189.4712338.224 193.9492341.105 197.341  2344.4 204.1252353.985 207.5182356.522
 229.0092359.453 245.873 2363.13 278.4412367.903 290.2552368.754 306.1522367.469
#Mann= 3 ,-1 , 0
       0     .12       0 172.386    .045       0 189.471     .12       0
Bank Sta=172.386,189.471
XS Rating Curve= 0 ,0
Exp/Cntr(USF)=0,0
Exp/Cntr=0.3,0.1

Type RM Length L Ch R = 1 ,18100   ,44.3,41.4,37.7
XS GIS Cut Line= 4
1980113.18328436199268.6733377191980158.83691274 199274.83311139
1980243.42680517199305.3794614331980302.16978602199346.499548029
#Sta/Elev= 30
       0 2352.57    11.8 2354.76    15.2 2353.48      18 2354.83    21.8 2355.26
    28.4  2354.2    31.7 2351.68      35 2356.27    39.2 2356.54    48.4 2354.89
    55.4 2355.48    58.8 2356.77    65.8 2356.64    73.4  2353.3    79.8 2349.31
    83.3 2345.56    90.2 2332.97    92.52329.467    93.7 2327.64    97.2 2327.48
   104.2 2328.02   107.7 2329.72   111.2 2334.25   119.5 2347.28   125.1 2355.41
   128.6 2358.98   132.1 2360.92   179.9 2367.48   197.1 2366.38   207.7 2364.85
#Mann= 3 ,-1 , 0
       0     .12       0    92.5    .045       0   107.7     .12       0
Bank Sta=92.5,107.7
XS Rating Curve= 0 ,0
Exp/Cntr(USF)=0,0
Exp/Cntr=0.3,0.1

Type RM Length L Ch R = 1 ,18059   ,31.3,31,32.1
XS GIS Cut Line= 4
1980104.86005462199319.4173274671980179.25436269199328.943427891
1980256.33690216199341.7905178031980305.15584383199355.494080376
#Sta/Elev= 30
       0 2329.82     3.7  2331.1       7 2331.12    23.5 2329.24    30.1 2329.17
      50  2330.8    56.6 2333.63    63.2 2338.59    73.1 2344.53    76.5  2344.8
    83.1 2341.81    86.4 2337.27    89.8 2330.62    93.1 2326.88    98.7 2323.42
    99.7 2322.84   106.4 2322.14   113.1 2322.81   113.72323.586   116.4 2327.05
   129.7 2351.61     133 2355.76   136.3 2356.77   149.6 2358.48   160.1 2361.46
   170.5 2361.24   176.8 2362.09   183.6 2362.13   191.8 2360.21   203.9 2361.06
#Mann= 4 ,-1 , 0
       0     .04       0      10     .12       0    98.7    .045       0
   113.7     .12       0
#XS Ineff= 2 , 0
           74.96 2345.08
Permanent Ineff=
       F       F
Bank Sta=98.7,113.7
XS Rating Curve= 0 ,0
Exp/Cntr(USF)=0,0
Exp/Cntr=0.3,0.1

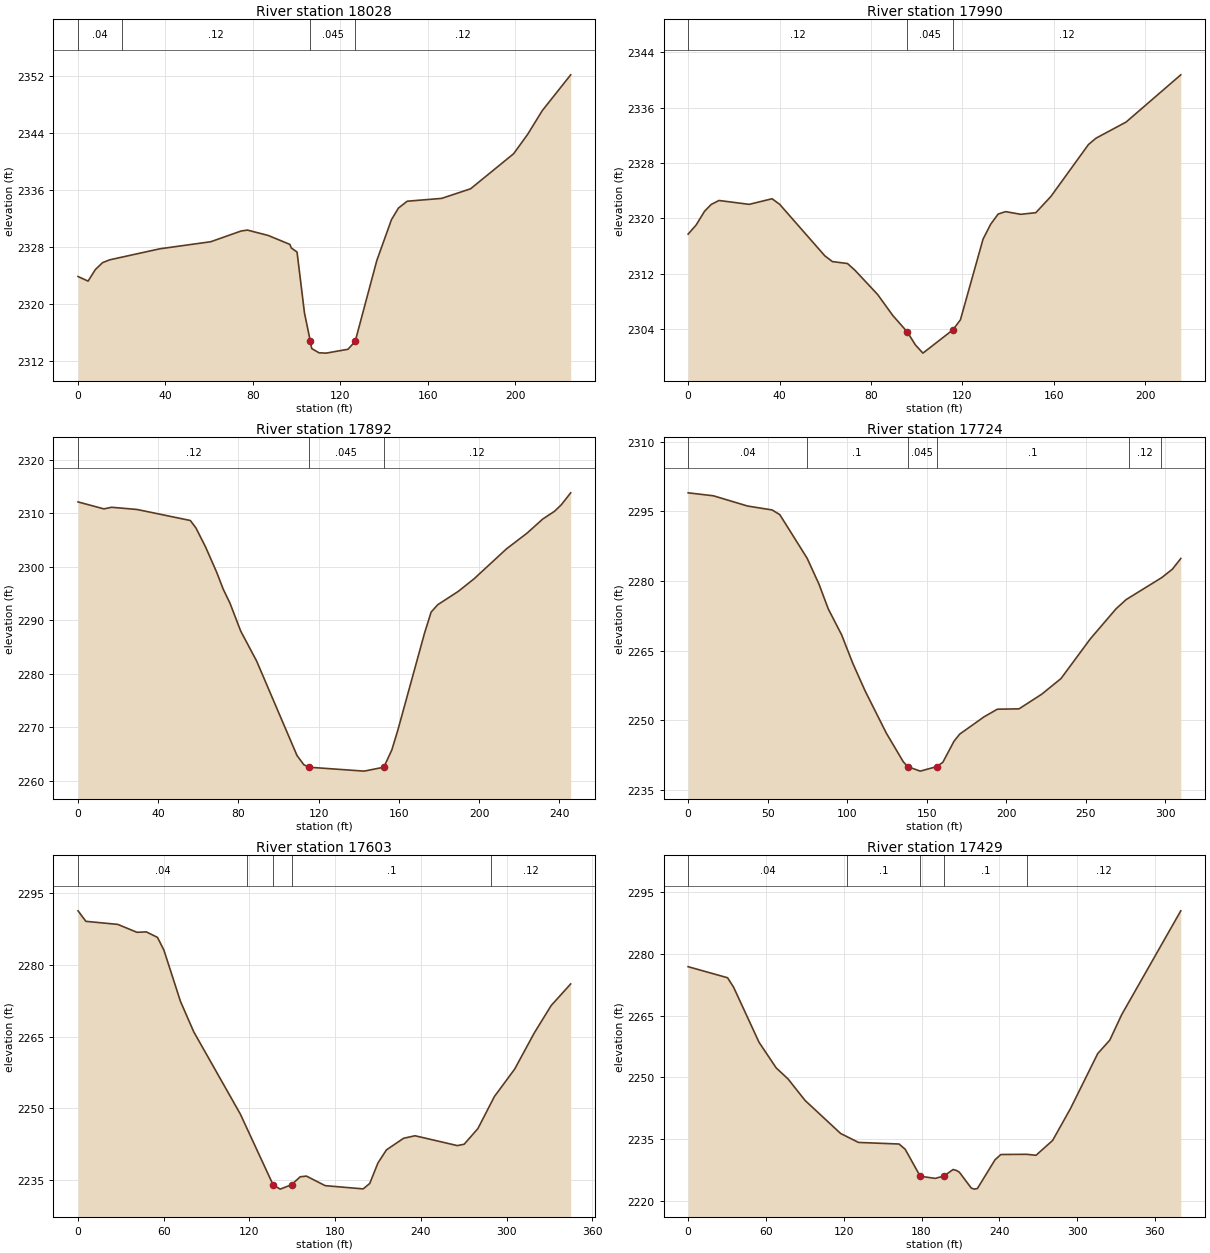
Type RM Length L Ch R = 1 ,18028   ,41.9,38,31.8
XS GIS Cut Line= 4
1980097.33293733199356.4810624791980156.26633153199356.850008938
 1980246.4605988 199370.51580701 1980321.6224882199373.248966624
#Sta/Elev= 30
       0 2323.87     4.6 2323.23     7.9 2324.84    11.2 2325.81    14.5 2326.21
    37.4 2327.75    60.7 2328.74    74.6 2330.24    77.5 2330.37      87 2329.62
    96.9 2328.37    97.6 2327.86   100.2  2327.3   103.6 2318.78   106.3 2314.78
   106.9  2313.8   110.2  2313.2   113.5 2313.15   123.5 2313.69   126.8 2314.79
   136.7 2326.12   143.4 2331.83   146.6 2333.45   150.6 2334.41   166.4 2334.81
   179.6 2336.15   199.3 2341.06   205.8 2343.81   212.4 2347.09   225.4  2352.1
#Mann= 4 ,-1 , 0
       0     .04       0      20     .12       0   106.3    .045       0
   126.8     .12       0
Bank Sta=106.3,126.8
XS Rating Curve= 0 ,0
Exp/Cntr(USF)=0,0
Exp/Cntr=0.3,0.1

Type RM Length L Ch R = 1 ,17990   ,97,97.7,94.7
XS GIS Cut Line= 4
1980114.89260547199414.0722394261980157.66205312199407.592248114
1980266.92399751199397.0185115611980329.19155721199401.717950029
#Sta/Elev= 30
       0 2317.71     3.5 2319.03     7.2 2321.02    10.1    2322    13.5 2322.57
    26.7 2322.01    36.7 2322.82      40 2322.03    59.8 2314.57    63.1 2313.74
    69.7 2313.46      73 2312.48    82.9 2308.98    89.5 2305.96    95.9 2303.56
    99.4  2301.7   102.7 2300.51   115.8 2303.87   119.1 2305.32     129 2316.98
   132.3 2319.12   135.6 2320.61   138.9 2320.96   145.5 2320.57   152.1 2320.81
   158.7 2323.16   175.1 2330.65   178.4 2331.57   191.6 2333.91   215.5 2340.73
#Mann= 3 ,-1 , 0
       0     .12       0    95.9    .045       0   115.8     .12       0
Bank Sta=95.9,115.8
XS Rating Curve= 0 ,0
Exp/Cntr(USF)=0,0
Exp/Cntr=0.3,0.1

Type RM Length L Ch R = 1 ,17892   ,172,168,160.8
XS GIS Cut Line= 4
1980115.26893732 199504.440628111980165.83239018199505.807207917
1980297.02405167199479.8421915811980355.78698338199462.076654089
#Sta/Elev= 30
       0 2312.11    12.9 2310.81    16.7 2311.11    29.4  2310.7      56 2308.64
    58.8 2307.25    63.6  2303.7    69.1 2299.01    72.4 2295.81    75.8 2293.17
    81.1    2288    89.1 2282.35   109.2 2264.73   112.6    2263  115.212262.531
   142.7  2261.8   152.52262.532   156.5 2265.76   159.5 2269.46   172.8 2287.57
   176.1 2291.52   179.4  2292.9   189.6 2295.38   197.6 2297.77   213.6 2303.31
   223.9 2306.26   231.8 2308.92   237.6 2310.35     241 2311.56245.7081 2313.81
#Mann= 3 ,-1 , 0
       0     .12       0  115.21    .045       0   152.5     .12       0
Bank Sta=115.21,152.5
XS Rating Curve= 0 ,0
Exp/Cntr(USF)=0,0
Exp/Cntr=0.3,0.1

Type RM Length L Ch R = 1 ,17724   ,126.4,121.8,115.5
XS GIS Cut Line= 4
1980158.99949115199697.1283809171980201.36346517199683.462582846
1980324.35564781199634.2657097891980440.51493142199570.036458853
#Sta/Elev= 30
       0 2299.02    15.9 2298.38    37.4 2296.17    52.8 2295.33    57.6 2294.33
    74.8 2284.93    82.3 2279.31    88.1    2274    96.5 2268.41   103.5 2262.29
   111.3  2256.3   124.7 2247.17   135.3 2241.03  138.062240.006   145.9 2239.04
  156.182240.007   160.1 2240.93   167.1 2245.46   170.7 2247.01   186.1 2250.76
   194.4 2252.39     208 2252.46   222.3 2255.62   234.4 2258.99   252.8 2267.53
     269 2274.02   275.4 2276.02   297.7 2280.74   304.4 2282.55309.7144 2284.86
#Mann= 6 ,-1 , 0
       0     .04       0   74.51      .1       0  138.06    .045       0
  156.18      .1       0  276.98     .12       0  296.98      .1       0
Bank Sta=138.06,156.18
XS Rating Curve= 0 ,0
Exp/Cntr(USF)=0,0
Exp/Cntr=0.3,0.1

Type RM Length L Ch R = 1 ,17603   ,174,174,172.4
XS GIS Cut Line= 4
1980215.02926324199837.8861010531980268.32587572199814.654244332
1980381.75199971 199714.89391841 1980493.8115439 199638.36544921
#Sta/Elev= 30
       0 2291.36     5.5 2289.16    27.8 2288.52    41.3 2286.86    47.8 2286.95
    55.6  2285.8    60.1 2283.14    71.7  2272.4      81 2266.02   113.6  2248.8
  136.562233.971   141.5 2233.07  149.47 2233.99   155.5 2235.65   159.9  2235.8
     173  2233.8   199.6 2233.12   204.2 2234.25     210 2238.57   215.9 2241.29
   227.9 2243.72   235.9 2244.25   265.5 2242.19   270.3 2242.47   279.9 2245.74
   291.5 2252.47   305.7 2258.22   319.3 2265.73   331.2 2271.51344.8929 2276.05
#Mann= 5 ,-1 , 0
       0     .04       0  118.14      .1       0  136.56    .045       0
  149.47      .1       0  289.19     .12       0
Bank Sta=136.56,149.47
XS Rating Curve= 0 ,0
Exp/Cntr(USF)=0,0
Exp/Cntr=0.3,0.1

Type RM Length L Ch R = 1 ,17429   ,123,124.3,125.2
XS GIS Cut Line= 4
1980320.25590839200001.8756779111980381.75199971199947.212485625
1980488.34522467199843.3524202821980596.30502943199740.858934746
#Sta/Elev= 30
       0 2276.85    30.4 2274.17      35 2271.92    54.7 2258.52    67.9 2252.33
    77.1 2249.63    90.2 2244.43   117.6 2236.43   131.4 2234.26   162.7 2233.87
   167.4 2232.61     179 2226.06   190.6 2225.54   197.5 2226.15   204.3 2227.69
   206.8 2227.48   209.1 2227.07   218.4 2223.19   220.7 2222.94   223.1 2223.09
   236.7 2230.06   241.2 2231.33   261.1 2231.38   268.3 2231.14   281.1 2234.73
     295 2242.53   315.9 2255.79   325.2 2259.05   334.4 2265.23379.9677 2290.39
#Mann= 5 ,-1 , 0
       0     .04       0  122.28      .1       0     179    .045       0
   197.5      .1       0   261.1     .12       0
Bank Sta=179,197.5
XS Rating Curve= 0 ,0
Exp/Cntr(USF)=0,0
Exp/Cntr=0.3,0.1

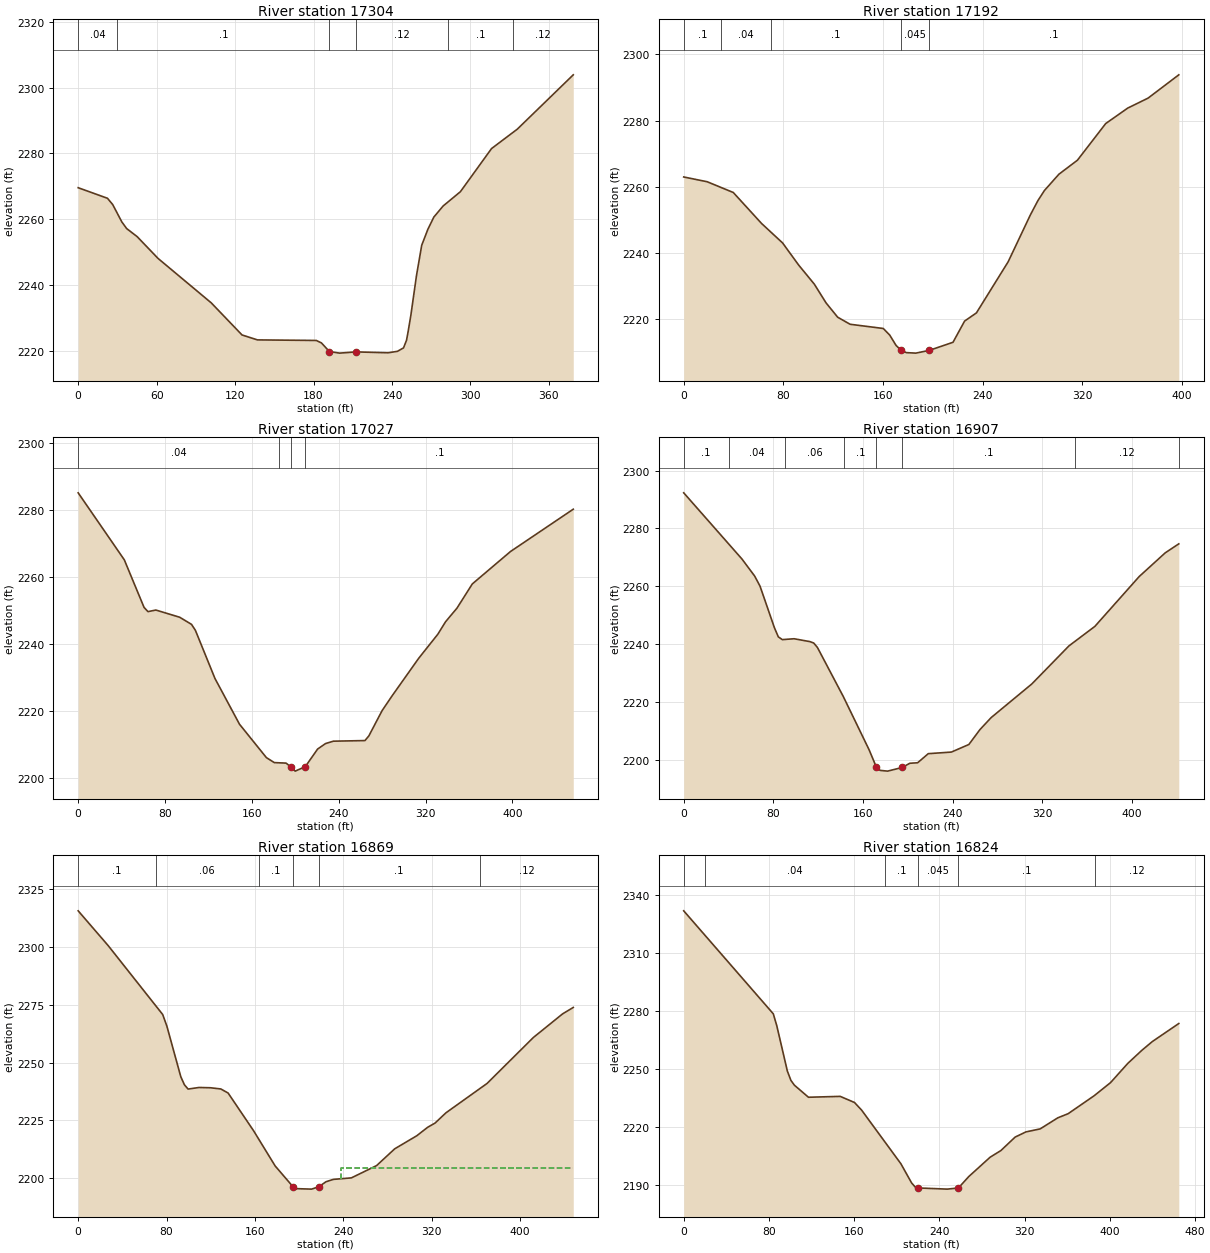
Type RM Length L Ch R = 1 ,17304   ,114.5,112.5,110.5
XS GIS Cut Line= 4
1980383.15306694200081.5234710561980494.57263129200003.927703026
1980598.03365533 199914.394124531980657.72270766199826.850181112
#Sta/Elev= 30
       0 2269.56    22.4 2266.35    26.4 2264.45    33.4 2259.16    37.1 2257.14
    45.1  2254.7    61.1 2248.07   101.8 2234.56   125.3 2224.82   137.1 2223.32
   182.1 2223.15     186 2222.41   192.1 2219.79   199.9  2219.3   212.2 2219.67
   237.1 2219.41   244.1 2219.84   248.8 2220.89   251.1 2223.22   252.3  2225.8
   254.4 2230.78   258.7 2242.82   262.7 2252.06   267.4 2256.91     272 2260.65
   279.1 2264.01   292.3 2268.35   316.1 2281.45   335.8 2287.35   378.6 2303.86
#Mann= 6 ,-1 , 0
       0     .04       0      30      .1       0   192.1    .045       0
   212.2     .12       0   282.6      .1       0   332.6     .12       0
Bank Sta=192.1,212.2
XS Rating Curve= 0 ,0
Exp/Cntr(USF)=0,0
Exp/Cntr=0.3,0.1

Type RM Length L Ch R = 1 ,17192   ,169.3,164.6,157.2
XS GIS Cut Line= 4
1980454.18072949200184.9973720681980543.00841695200111.202062482
 1980648.2350621200004.6088375251980713.83089285199889.816133725
#Sta/Elev= 30
       0 2262.93    18.8  2261.5    39.8 2258.24    62.5 2248.87    79.4 2242.97
    92.3 2236.28   104.9 2230.49   114.3 2224.83   123.6 2220.51   133.6 2218.37
   160.2  2217.1   165.4  2215.1   170.5 2211.96  174.682210.456   178.8 2209.79
   186.3 2209.64  197.022210.455   216.2 2212.92   225.5 2219.33     235 2221.81
   260.5 2237.29   278.3 2251.45   284.4  2255.8   289.6 2258.84   301.2 2263.76
   316.1 2268.01   338.8  2279.1   356.5 2283.78   372.8 2286.79397.4771 2293.84
#Mann= 5 ,-1 , 0
       0      .1       0      30     .04       0      70      .1       0
  174.68    .045       0  197.02      .1       0
Bank Sta=174.68,197.02
XS Rating Curve= 0 ,0
Exp/Cntr(USF)=0,0
Exp/Cntr=0.3,0.1

Type RM Length L Ch R = 1 ,17027   ,127.9,120.3,112.5
XS GIS Cut Line= 4
1980625.00320538200353.0866883471980661.90086018200276.558219147
1980741.16248899200109.8354826751980809.49147935199936.279847168
#Sta/Elev= 30
       0 2285.24    42.5  2265.2    60.7 2250.96    64.3  2249.7    71.6 2250.17
    93.5 2248.02   104.4 2245.89     108  2244.1     126 2229.71   148.6 2216.02
   173.4 2206.02   180.7 2204.53   191.5 2204.38  195.672203.305   199.9 2201.98
   209.22203.303   220.6 2208.59   227.9 2210.23   235.1 2210.94   264.2 2211.12
   267.8 2212.53     280 2220.09     289 2224.41   313.7 2235.74   331.4 2242.97
   338.4 2246.65     349 2250.76   363.1 2257.99   398.3 2267.69456.0856 2280.34
#Mann= 4 ,-1 , 0
       0     .04       0  184.96      .1       0  195.67    .045       0
   209.2      .1       0
Bank Sta=195.67,209.2
XS Rating Curve= 0 ,0
Exp/Cntr(USF)=0,0
Exp/Cntr=0.3,0.1

Type RM Length L Ch R = 1 ,16907   ,40.5,37.9,35.3
XS GIS Cut Line= 4
1980769.14227201200399.8650834861980810.92460864200294.414424368
1980824.85205419200149.1710636971980846.73804004199968.114271628
#Sta/Elev= 30
       0 2292.32      52 2269.41    63.3 2263.53    68.1 2260.03    80.9 2245.69
    84.4  2242.5      88 2241.54    98.5 2241.84   112.7 2240.84     116 2240.36
   119.3 2238.83   142.4 2221.84   165.4 2203.44     172 2197.31   175.3  2196.3
   181.9 2196.05   195.1 2197.33   201.7 2198.77   208.7 2198.94   218.2 2202.09
   238.8 2202.64   254.4 2205.26   264.3 2210.42   274.3 2214.57   310.6 2226.21
   343.7 2239.37   366.8 2246.11   406.4 2263.37   429.6 2271.56   441.7 2274.67
#Mann= 8 ,-1 , 0
       0      .1       0      40     .04       0      90     .06       0
  143.43      .1       0     172    .045       0   195.1      .1       0
  349.34     .12       0  441.71      .1       0
Bank Sta=172,195.1
XS Rating Curve= 0 ,0
Exp/Cntr(USF)=0,0
Exp/Cntr=0.3,0.1

Type RM Length L Ch R = 1 ,16869   ,48,45.1,40.8
XS GIS Cut Line= 4
1980847.24399055200427.0963009771980857.39709835200303.808563388
1980853.04576644200144.259726507 1980870.4510941199980.359557711
#Sta/Elev= 30
       0 2315.63    27.1 2300.62    76.5 2270.77    80.3 2265.72    92.9 2243.83
    96.2 2240.34    99.5 2238.51   109.4  2239.2   119.8 2239.07   129.1 2238.56
   135.7  2236.8   158.7 2220.53   178.3 2205.24   194.8 2196.06     198 2195.42
   211.2 2195.22   217.7 2196.22   224.3 2198.41   230.9 2199.43   247.3 2200.09
   270.1  2205.4   286.5 2212.66   306.5 2218.32   316.3 2221.97     323  2223.8
   332.9 2228.25   370.1 2240.95     412 2260.83   438.4 2271.03   448.1 2273.83
#Mann= 6 ,-1 , 0
       0      .1       0      70     .06       0  163.71      .1       0
   194.8    .045       0   217.7      .1       0  363.31     .12       0
#XS Ineff= 2 , 0
                          237.63         2204.44
Permanent Ineff=
       F       F
Bank Sta=194.8,217.7
XS Rating Curve= 0 ,0
Exp/Cntr(USF)=0,0
Exp/Cntr=0.3,0.1

Type RM Length L Ch R = 1 ,16824   ,158.1,161.9,164.1
XS GIS Cut Line= 4
  1980896.952587 200447.38069504 1980916.0847043200299.790075868
 1980877.8204697200116.6683817111980887.38652835199988.209879839
#Sta/Elev= 30
       0 2331.67    84.1 2278.51    87.4  2272.3    97.3 2248.96   100.6 2244.17
   103.9 2241.68   117.1 2235.45   146.9  2235.9   160.3 2232.75     167 2228.81
   203.9 2201.09   213.9 2191.24   217.3  2189.1  219.952188.644   247.4 2188.03
  257.882188.644   267.6 2194.53   287.7 2204.54   297.7 2207.93   311.1 2214.89
   321.2 2217.56   334.6 2219.12   351.1 2224.82   360.8 2226.95   385.3 2236.24
   400.6 2242.98   416.9 2252.96     430 2259.65   439.9 2264.21464.7164 2273.51
#Mann= 6 ,-1 , 0
       0      .1       0      20     .04       0  188.83      .1       0
  219.95    .045       0  257.88      .1       0   385.9     .12       0
Bank Sta=219.95,257.88
XS Rating Curve= 0 ,0
Exp/Cntr(USF)=0,0
Exp/Cntr=0.3,0.1