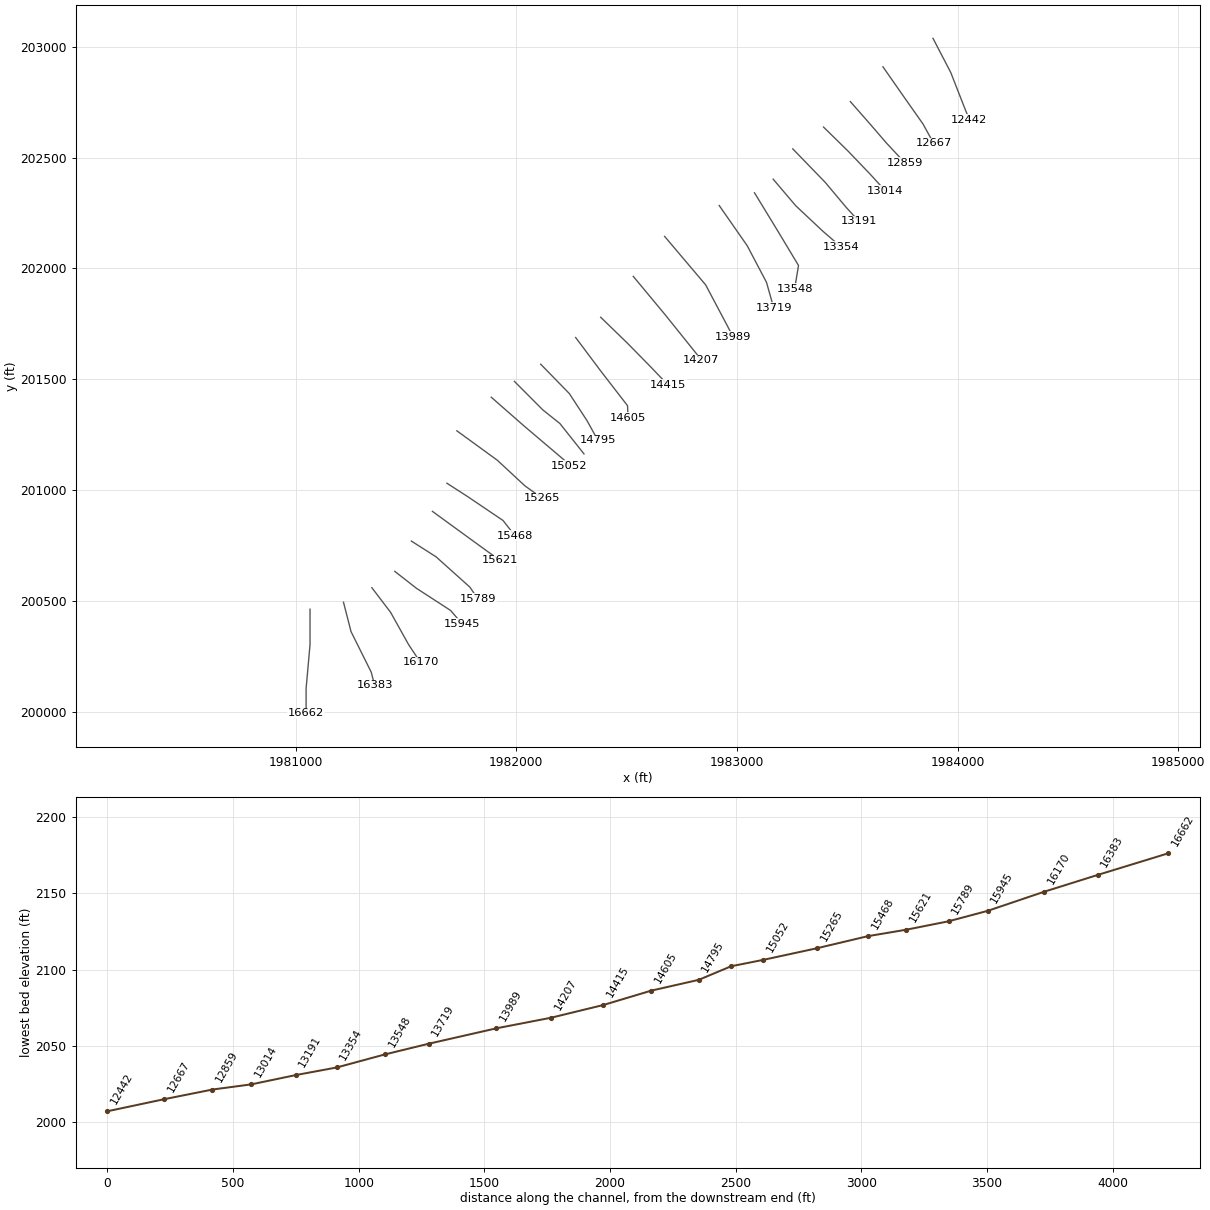
HEC-RAS study PIPESTCK2_A.prj: PIPESTCK2_A

--- PIPESTCK2_A.g01 (geometry) --- (continued)

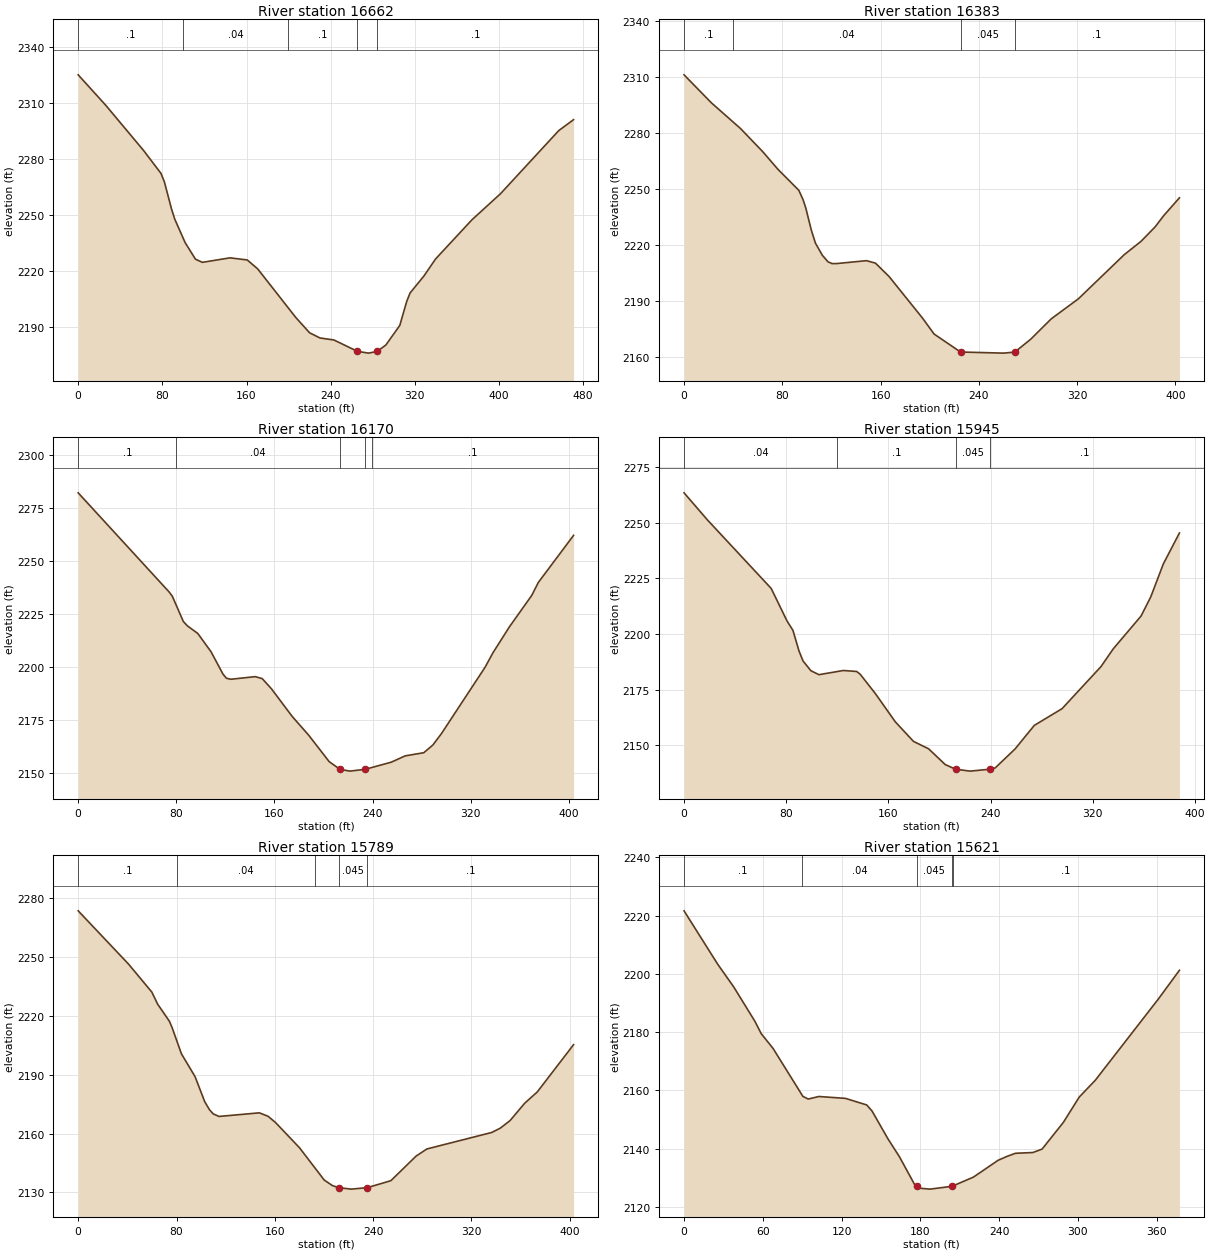
Type RM Length L Ch R = 1 ,16662   ,256.9,279.1,287.4
XS GIS Cut Line= 4
1981065.04190328200462.4130729181981065.04190328200302.523235482
1981047.27636579200104.3691634461981047.27636579199992.309619261
#Sta/Elev= 30
       0 2325.33    26.2 2309.01    62.3 2284.66    78.7 2272.48      82 2267.83
    88.6 2253.65    91.8 2247.93   101.7 2235.31   111.5 2226.44   118.1 2224.76
   144.3 2227.18   160.7 2226.04   170.6 2221.28   206.8 2195.23     220 2186.96
   229.9 2184.19   243.1 2183.12   265.52177.008     276 2176.07  284.362177.008
   292.5 2180.45   305.7 2190.92   312.3 2203.83   315.5 2208.34   328.6  2217.4
   339.7 2226.55   374.3 2247.58   401.5  2261.6   456.8 2295.41470.8983 2301.29
#Mann= 5 ,-1 , 0
       0      .1       0     100     .04       0  199.89      .1       0
   265.5    .045       0  284.36      .1       0
Bank Sta=265.5,284.36
XS Rating Curve= 0 ,0
Exp/Cntr(USF)=0,0
Exp/Cntr=0.3,0.1

Type RM Length L Ch R = 1 ,16383   ,207.2,212.6,212.3
XS GIS Cut Line= 4
1981216.73226188200493.8444084831981250.89675706 200361.28616719
1981342.45760413200178.1644730321981357.98408143 200118.54280021
#Sta/Elev= 30
       0    2311  22.2612296.016  45.9772282.246  64.0752269.844   76.472260.387
   93.41 2249.19  96.7982244.292  99.094 2239.74 103.5742227.939 106.9622220.876
 112.5632214.406 117.1262210.917 120.5142209.932 123.9022209.929 148.5052211.506
 155.8422210.168 166.8462203.054 194.1312180.743 203.527 2172.23  225.082162.595
 260.157    2162  269.252162.568 282.1652169.433 298.8972180.357 320.905 2191.03
 358.4262214.772 371.8752221.788 383.4992229.621  390.282235.477 403.2372245.153
#Mann= 4 ,-1 , 0
       0      .1       0      40     .04       0  225.08    .045       0
  269.25      .1       0
Bank Sta=225.08,269.25
XS Rating Curve= 0 ,0
Exp/Cntr(USF)=0,0
Exp/Cntr=0.3,0.1

Type RM Length L Ch R = 1 ,16170   ,217.6,225.5,238.2
XS GIS Cut Line= 4
1981345.19076375200559.4402392261981429.91871179200448.747274847
1981511.91350022200302.5232354821981565.60020536200221.993177775
#Sta/Elev= 30
       02282.067  74.0132235.469    76.72233.442  85.7152221.494  89.0952219.396
  97.4932215.851 108.2882207.253 118.0162196.746 120.819 2194.76 124.4822194.288
 144.3662195.522 150.0232194.589 157.5462189.799 174.524 2176.74  187.942167.923
 204.6162155.489  213.382151.893 221.4872151.031  234.052151.892 255.2272155.246
 266.6282158.225 281.7372159.699 289.196 2163.37 296.1972168.756 331.7092199.958
 338.0612206.703 351.4242218.869 369.7372233.776 375.0822239.847 403.8272262.042
#Mann= 5 ,-1 , 0
       0      .1       0      80     .04       0  213.38    .045       0
  234.05     .04       0   239.4      .1       0
Bank Sta=213.38,234.05
XS Rating Curve= 0 ,0
Exp/Cntr(USF)=0,0
Exp/Cntr=0.3,0.1

Type RM Length L Ch R = 1 ,15945   ,158.2,155.6,151.5
XS GIS Cut Line= 4
1981449.05082909200633.2355488111981547.44457521200556.707079611
1981701.86809341 200456.946753691981753.81288562200397.097319192
#Sta/Elev= 30
       02263.362  18.3092251.209  68.1852220.483  80.6552205.814  85.2472201.644
  89.9222192.518  93.1242187.927  99.2742183.539 105.593 2181.76 124.6512183.634
 135.1172183.202 137.9882181.885 149.7062173.308  165.332160.628 179.5742151.829
 191.4392148.493 204.3892141.441   212.62139.325 223.918 2138.48  239.132139.326
 243.4482139.875 259.0712148.407 274.1782159.016 295.8482166.491 326.3342185.373
 335.968 2193.37  357.692208.057 365.2872216.637 375.1742231.497 387.7432245.331
#Mann= 4 ,-1 , 0
       0     .04       0     120      .1       0   212.6    .045       0
  239.13      .1       0
Bank Sta=212.6,239.13
XS Rating Curve= 0 ,0
Exp/Cntr(USF)=0,0
Exp/Cntr=0.3,0.1

Type RM Length L Ch R = 1 ,15789   ,167.8,168.6,171.3
XS GIS Cut Line= 4
1981524.21271848200769.8935295261981636.27226267200698.831379554
1981789.32920107 200562.173398841981826.14511187200508.402792281
#Sta/Elev= 30
       02273.578  40.9052246.461  59.9232232.146  64.6782225.961  74.1872217.306
  76.5642213.791  83.9922200.677  95.1632188.938 102.9332176.269 106.8182172.132
 109.8472170.035 114.5882168.717 147.3822170.552 154.5122168.789 160.5772165.606
 180.0722152.742 200.161 2136.29 206.832 2133.45  212.052132.393 222.1522131.646
  235.272132.396 254.4272135.957 274.9312148.501 283.728 2152.13 336.5072160.549
 343.4352162.746 351.3872166.601 363.3162175.483 373.4832181.186 403.0462205.316
#Mann= 5 ,-1 , 0
       0      .1       0      80     .04       0  192.69      .1       0
  212.05    .045       0  235.27      .1       0
Bank Sta=212.05,235.27
XS Rating Curve= 0 ,0
Exp/Cntr(USF)=0,0
Exp/Cntr=0.3,0.1

Type RM Length L Ch R = 1 ,15621   ,151.4,152.6,153.3
XS GIS Cut Line= 4
1981619.87330498200903.8183506261981704.60125303200842.322259304
1981872.69056931200720.6966564691981926.10219323200683.141608396
#Sta/Elev= 30
       02221.685  25.6952203.329  37.8572195.563  54.0722183.698  58.8182179.504
  67.813 2174.45  90.5582157.984  94.6112157.059 102.7192157.934 122.9692157.294
 139.1682155.036 143.2182152.979 155.366 2143.41 164.1362137.239 175.6152127.761
   177.32127.097 179.6642126.441 187.4492126.132  204.172127.097 220.5252130.261
 239.3222136.039  246.372137.423 252.557 2138.44 265.8032138.698 272.8062139.875
 289.0042149.028 301.1532157.757 313.2912163.478 361.4192191.412 377.4632201.273
#Mann= 5 ,-1 , 0
       0      .1       0      90     .04       0   177.3    .045       0
  204.17     .04       0  204.69      .1       0
Bank Sta=177.3,204.17
XS Rating Curve= 0 ,0
Exp/Cntr(USF)=0,0
Exp/Cntr=0.3,0.1

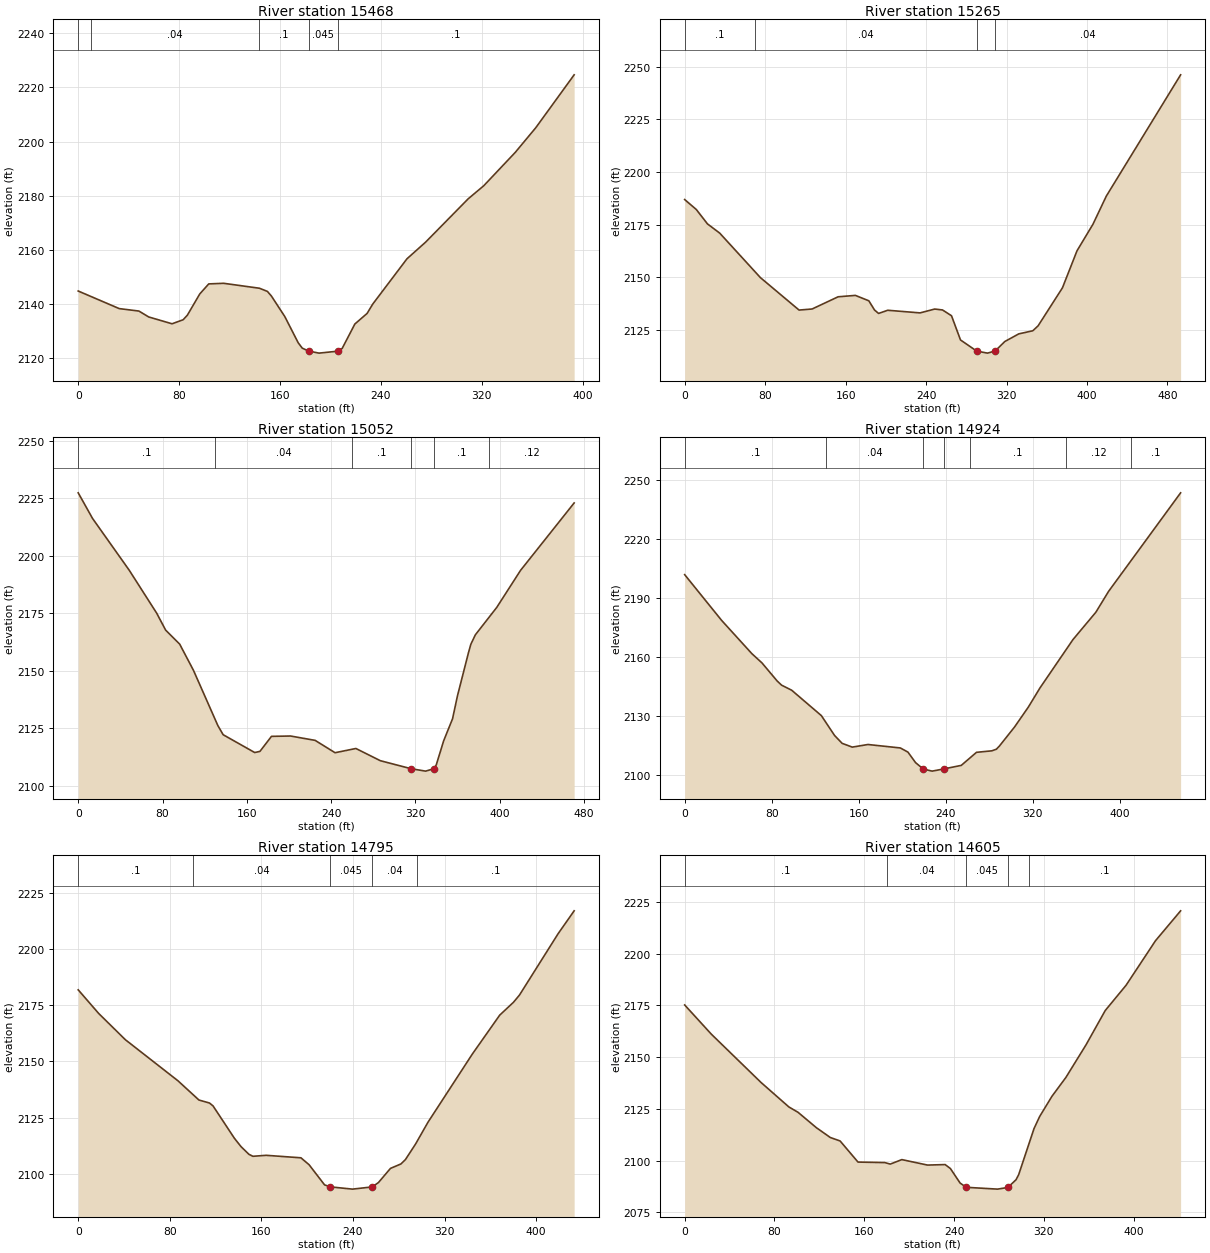
Type RM Length L Ch R = 1 ,15468   ,205.4,203.1,199.2
XS GIS Cut Line= 4
1981685.46913573 201030.910272691981781.12972223200969.414181369
1981939.65297986200862.8209564121981994.50470673200793.240525103
#Sta/Elev= 30
       02144.848  32.5462138.356  48.1482137.449  55.9482135.265  74.4342132.752
   83.252134.248  86.568 2135.93  96.4192143.773 103.5412147.477 115.4042147.699
 143.7722145.875 150.0442144.712 153.228    2143 163.843 2135.43 174.5042125.726
 177.7192123.751  182.972122.641 191.0522121.918  205.882122.638 209.3482123.637
  219.422132.669 229.116 2136.57 233.6042140.026 260.744 2156.74 275.5562162.909
 309.3572178.917 321.606  2183.7 346.6722196.056 362.9282205.151 393.3512224.676
#Mann= 5 ,-1 , 0
       0      .1       0      10     .04       0  143.72      .1       0
  182.97    .045       0  205.88      .1       0
Bank Sta=182.97,205.88
XS Rating Curve= 0 ,0
Exp/Cntr(USF)=0,0
Exp/Cntr=0.3,0.1

Type RM Length L Ch R = 1 ,15265   ,213,213.1,214
XS GIS Cut Line= 4
1981730.56626936201267.3285793261981913.68796352201134.770338033
1982039.41330578201018.6110544261982117.56571192200963.128811896
#Sta/Elev= 30
       0  2186.9  11.578 2182.17  22.6772175.341  34.8282170.976   75.332149.826
 113.7432134.434 126.7022134.946 152.5462140.736 169.6942141.407 183.0892138.841
 188.7362134.471 192.786 2132.84 201.8852134.345 234.0312133.095 248.6052134.919
 256.3652134.488 265.2982131.743 274.2322120.248  290.35 2114.96 301.0322113.995
  308.662114.992 318.2562119.494 332.1872123.137 346.1172124.605 351.403 2126.96
 375.576 2144.98  390.082162.586 405.8492175.108 419.2142188.546 493.0812246.117
#Mann= 4 ,-1 , 0
       0      .1       0      70     .04       0  290.35    .045       0
  308.66     .04       0
Bank Sta=290.35,308.66
XS Rating Curve= 0 ,0
Exp/Cntr(USF)=0,0
Exp/Cntr=0.3,0.1

Type RM Length L Ch R = 1 ,15052   ,128.6,128.2,131.2
XS GIS Cut Line= 4
1981886.35636738201419.0189379191982036.68014616201287.827276434
1982221.16842013201132.0371784191982239.25230727201108.595102498
#Sta/Elev= 30
       02227.359   13.562216.255  48.397 2193.73  74.5242175.013  82.9612167.695
  96.2972161.596 109.3612150.219 132.5452126.173 137.5352122.232 167.4722114.485
 172.4622114.992 183.3882121.517 201.5512121.663 224.8332119.769  243.732114.406
 263.4762116.244 286.6712110.941  315.842107.456 329.5992106.406  337.592107.454
 339.7532109.124 346.7892119.596 355.2082129.164 359.8652139.124 370.2642157.782
 372.5532161.524 376.8472165.644 397.1152177.537 419.789 2193.69 470.595 2222.96
#Mann= 6 ,-1 , 0
       0      .1       0     130     .04       0  259.52      .1       0
  315.84    .045       0  337.59      .1       0  389.52     .12       0
Bank Sta=315.84,337.59
XS Rating Curve= 0 ,0
Exp/Cntr(USF)=0,0
Exp/Cntr=0.3,0.1

Type RM Length L Ch R = 1 ,14924   ,133.6,129,123.7
XS GIS Cut Line= 4
1981991.42441807201490.4021482261982120.51393155 201361.31263475
1982197.38746204201300.3939879421982306.64973509201163.280547253
#Sta/Elev= 30
       02202.071  33.9722178.826  61.8112161.904   71.092157.211   85.012148.043
   89.112145.905   98.392143.336 125.6892130.423 137.8282120.327 144.7882116.336
 154.0672114.428 168.5262115.752 198.2492113.999 205.2562111.892 212.2622106.549
   219.42103.264  227.532102.221     2382103.315 254.2992105.142 268.3112111.777
 282.3532112.533 286.5492113.354 289.3272114.939 303.3292124.684 315.9142134.721
 326.682 2144.52 357.0332169.101 378.0452182.975 389.7182193.557 455.9682243.662
#Mann= 7 ,-1 , 0
       0      .1       0     130     .04       0   219.4    .045       0
     238     .04       0  262.56      .1       0  350.64     .12       0
  410.64      .1       0
Bank Sta=219.4,238
XS Rating Curve= 0 ,0
Exp/Cntr(USF)=0,0
Exp/Cntr=0.3,0.1

Type RM Length L Ch R = 1 ,14795   ,183.6,189.3,187.5
XS GIS Cut Line= 4
1982110.47545575201567.9761368981982240.30053743201435.417895605
1982320.92874605201312.4257129621982369.77225848 201224.50739058
#Sta/Elev= 30
       02181.825  17.8292171.365  41.1762159.681  87.0982141.446 105.4672132.884
 114.6512131.563 117.7852130.265 136.3452115.968 142.2052112.195 149.1182108.776
 152.5862107.901 164.1862108.333 194.5342107.227 201.6432104.161 215.2112095.186
  220.332094.311 239.5562093.315  256.942094.306 262.2872096.255  272.732102.517
 281.9022104.503 285.8252106.446 294.6452113.324 305.4392122.966 344.1472153.226
 368.1492170.578 380.2132176.316 385.4312179.511  419.212206.781 433.1832216.919
#Mann= 5 ,-1 , 0
       0      .1       0     100     .04       0  220.33    .045       0
  256.94     .04       0  295.54      .1       0
Bank Sta=220.33,256.94
XS Rating Curve= 0 ,0
Exp/Cntr(USF)=0,0
Exp/Cntr=0.3,0.1

Type RM Length L Ch R = 1 ,14605   ,182.4,189.9,191.5
XS GIS Cut Line= 4
1982268.99871338201688.2351599271982381.05825756201539.277960948
1982504.05044021201380.7547033191982506.76810391201325.948485293
#Sta/Elev= 30
       02175.154  23.6782161.098  68.1332137.686  92.8742125.904 100.9962123.331
 117.3962115.879 129.8242111.143 138.4832109.493 154.457 2099.29 178.3142099.046
 183.196 2098.32 193.5132100.484  216.382097.844 232.1112098.084 236.787 2096.17
 245.4472089.154  250.922087.106 278.8772086.231  288.04 2087.06 295.2452090.758
 297.5832093.167 311.2592115.422  316.292121.285 327.3162131.092 339.6732140.147
 357.5652155.842 374.7472172.466 393.2882184.652 419.5672206.198 441.9162220.612
#Mann= 5 ,-1 , 0
       0      .1       0     180     .04       0  250.92    .045       0
  288.04     .04       0   306.4      .1       0
Bank Sta=250.92,288.04
XS Rating Curve= 0 ,0
Exp/Cntr(USF)=0,0
Exp/Cntr=0.3,0.1

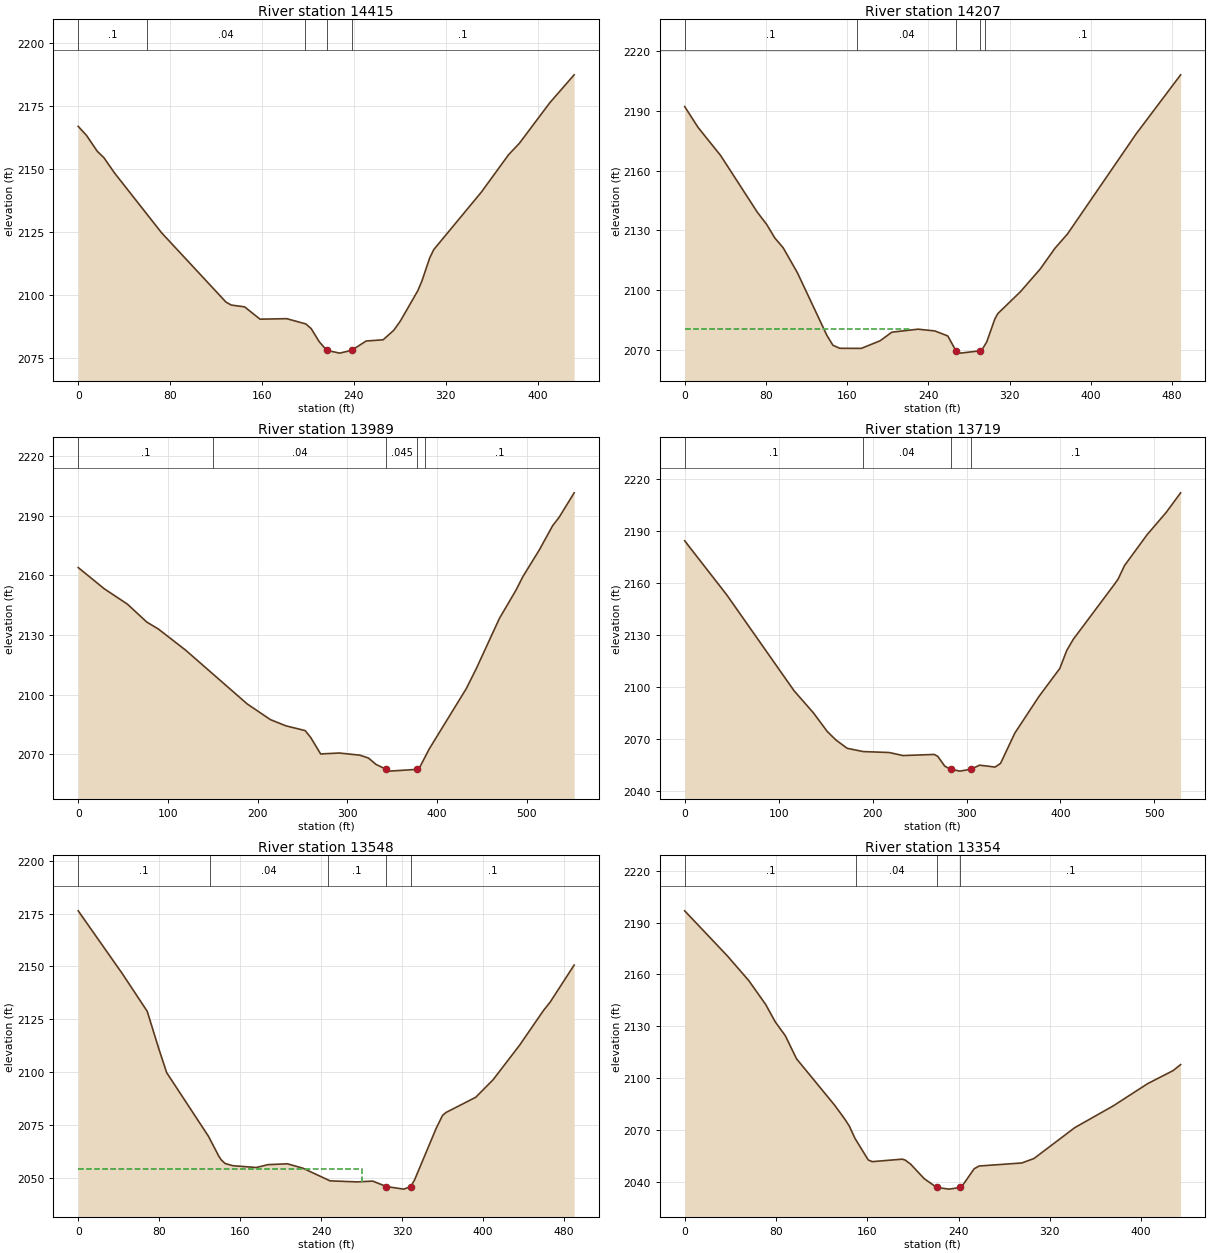
Type RM Length L Ch R = 1 ,14415   ,210.3,208.2,206.2
XS GIS Cut Line= 4
1982382.42483737201779.796007006 1982502.6838604201663.636723398
1982603.81076613201561.1432378621982687.48242728201474.190335103
#Sta/Elev= 30
       02167.045   7.2222163.454  16.6672157.093  22.4062154.575  31.5292148.565
  72.5812124.736 128.6382097.182 133.2782095.976  144.882095.274 158.3382090.375
 181.596 2090.57 198.2412088.467 202.8812086.623 209.8412081.432  216.41 2077.98
 227.6862076.868  238.192078.001 250.7312081.691  265.522082.165   274.82085.965
 280.5092089.622 295.6792101.655 299.194 2105.43 306.0382114.678 309.5992118.036
 351.087 2140.92 374.7452155.766 384.2092160.335 410.822 2176.53 431.8552187.539
#Mann= 5 ,-1 , 0
       0      .1       0      60     .04       0   197.2      .1       0
  216.41    .045       0  238.19      .1       0
Bank Sta=216.41,238.19
XS Rating Curve= 0 ,0
Exp/Cntr(USF)=0,0
Exp/Cntr=0.3,0.1

Type RM Length L Ch R = 1 ,14207   ,221.8,218,212.9
XS GIS Cut Line= 4
1982530.01545654 201964.28428097 1982674.8729161201790.728645463
1982816.99721604201614.4398503411982838.07489211201585.203073865
#Sta/Elev= 30
       02192.095  13.2492181.621  35.4642167.536  71.6292139.108  80.7982133.033
  88.7232126.302  97.1042121.277 111.0792108.807 140.004 2077.52 146.0192072.494
 152.8252070.962 173.9712070.907 192.6052074.746 204.1062079.041  229.88 2080.54
 246.5532079.646 259.1952077.134  267.252069.713 271.8382068.538   290.72069.692
  292.912070.271 297.5442074.139 305.5522085.672 308.5192088.372 330.8382099.363
 350.3372110.753 364.552 2120.95 377.1952128.315 444.6232178.329 488.5522208.009
#Mann= 5 ,-1 , 0
       0      .1       0     170     .04       0  267.25    .045       0
   290.7     .04       0  296.06      .1       0
#XS Ineff= 2 , 0
          223.39 2080.88
Permanent Ineff=
       T       F
Bank Sta=267.25,290.7
XS Rating Curve= 0 ,0
Exp/Cntr(USF)=0,0
Exp/Cntr=0.3,0.1

Type RM Length L Ch R = 1 ,13989   ,267,269.7,270.2
XS GIS Cut Line= 4
1982672.13975649202144.6728155131982857.99461026 201926.02004637
1982959.12151599201736.0654531771982982.25706145201691.129105265
#Sta/Elev= 30
       0 2163.98  29.0392153.304  54.8742145.561  76.4042136.567  89.2622133.086
 119.5862122.475 188.3572095.376 214.1932087.497 231.4162084.375 252.9462081.972
  259.172078.463 270.1692070.229 291.0522070.695 313.7872069.614 323.4892068.175
 331.9362064.953  343.382062.492 346.8042061.587   378.12062.491 380.2552063.229
 391.4052072.907  432.292102.924  443.442112.943 469.4582138.436 488.0422152.716
 495.4762159.358 513.9742172.904 528.7352185.037 536.1152189.352 552.707 2201.56
#Mann= 5 ,-1 , 0
       0      .1       0     150     .04       0  343.38    .045       0
   378.1     .04       0  386.97      .1       0
Bank Sta=343.38,378.1
XS Rating Curve= 0 ,0
Exp/Cntr(USF)=0,0
Exp/Cntr=0.3,0.1

Type RM Length L Ch R = 1 ,13719   ,169.4,171.8,172.5
XS GIS Cut Line= 4
1982919.49070158202284.0639558421983046.58262364202102.308841492
 1983134.0437313201936.9526848271983166.32623149201822.349809157
#Sta/Elev= 30
       02184.278   44.962152.977 116.4892097.784 137.0372085.088 151.8292074.305
 161.0572069.414 173.0672064.615 190.1582062.756 217.7952062.215 232.2392060.469
 265.6942061.106 269.406 2060.02 276.8292054.377  282.962052.579 292.9272051.486
  304.542052.582 313.9442054.919 330.381 2053.83 336.2132055.925 351.4322073.407
 377.0392094.468 399.308 2110.69 406.7312121.102 413.7212127.533 458.0312159.612
  461.442162.287 468.2572170.047 492.1162187.718 512.5682200.653 527.9072211.931
#Mann= 4 ,-1 , 0
       0      .1       0     190     .04       0  282.96    .045       0
  304.54      .1       0
Bank Sta=282.96,304.54
XS Rating Curve= 0 ,0
Exp/Cntr(USF)=0,0
Exp/Cntr=0.3,0.1

Type RM Length L Ch R = 1 ,13548   ,188.3,193.3,200.5
XS GIS Cut Line= 4
1983079.38053901202341.4603077421983187.34034378 202165.17151262
1983278.90119086202013.4811540271983261.56399307201908.815848815
#Sta/Elev= 30
       02176.281  43.4362146.656  68.1912128.734  79.7322110.861  87.4272099.696
 128.6542069.629 138.8752060.234 141.2872058.464 145.1342056.727 152.829 2055.68
 175.9122054.825 187.4532056.179  206.722056.578 222.0182054.494 248.8432048.516
 275.6682048.013 290.9972048.396  304.542045.807 321.6542044.597  328.592045.798
 332.337 2048.98 353.8442073.556 359.9762079.488 363.4032080.872  392.72 2088.05
 409.8382096.312 436.3012112.839  459.582129.057 466.2312133.046 489.9932150.626
#Mann= 5 ,-1 , 0
       0      .1       0     130     .04       0  246.72      .1       0
  304.54    .045       0  328.59      .1       0
#XS Ineff= 2 , 0
             280    2054
Permanent Ineff=
       F       F
Bank Sta=304.54,328.59
XS Rating Curve= 0 ,0
Exp/Cntr(USF)=0,0
Exp/Cntr=0.3,0.1

Type RM Length L Ch R = 1 ,13354   ,165.5,163.3,160.5
XS GIS Cut Line= 4
1983164.10848706202402.9563990631983266.60197259202282.697376035
1983390.96073504202166.5380924281983471.73660478  202097.2054709
#Sta/Elev= 30
       02196.744  37.523 2170.63  56.142 2156.48  70.9932142.648  79.4142132.581
  88.2362124.559  98.0322111.274 131.3442084.537 139.8742076.857 144.2762072.438
 149.2322065.333 160.8612052.836  164.36 2051.86  190.762053.305 193.3592052.719
 198.0012050.424 209.986 2041.99  220.952036.935 231.7012035.984  241.462036.935
 244.4262038.958 253.7112047.775 258.0492049.339 295.4942051.095 306.1132053.668
  341.952071.539 375.5742084.063 405.7982096.942 428.0362104.446 434.6312107.913
#Mann= 4 ,-1 , 0
       0      .1       0     150     .04       0  220.95    .045       0
  241.46      .1       0
Bank Sta=220.95,241.46
XS Rating Curve= 0 ,0
Exp/Cntr(USF)=0,0
Exp/Cntr=0.3,0.1

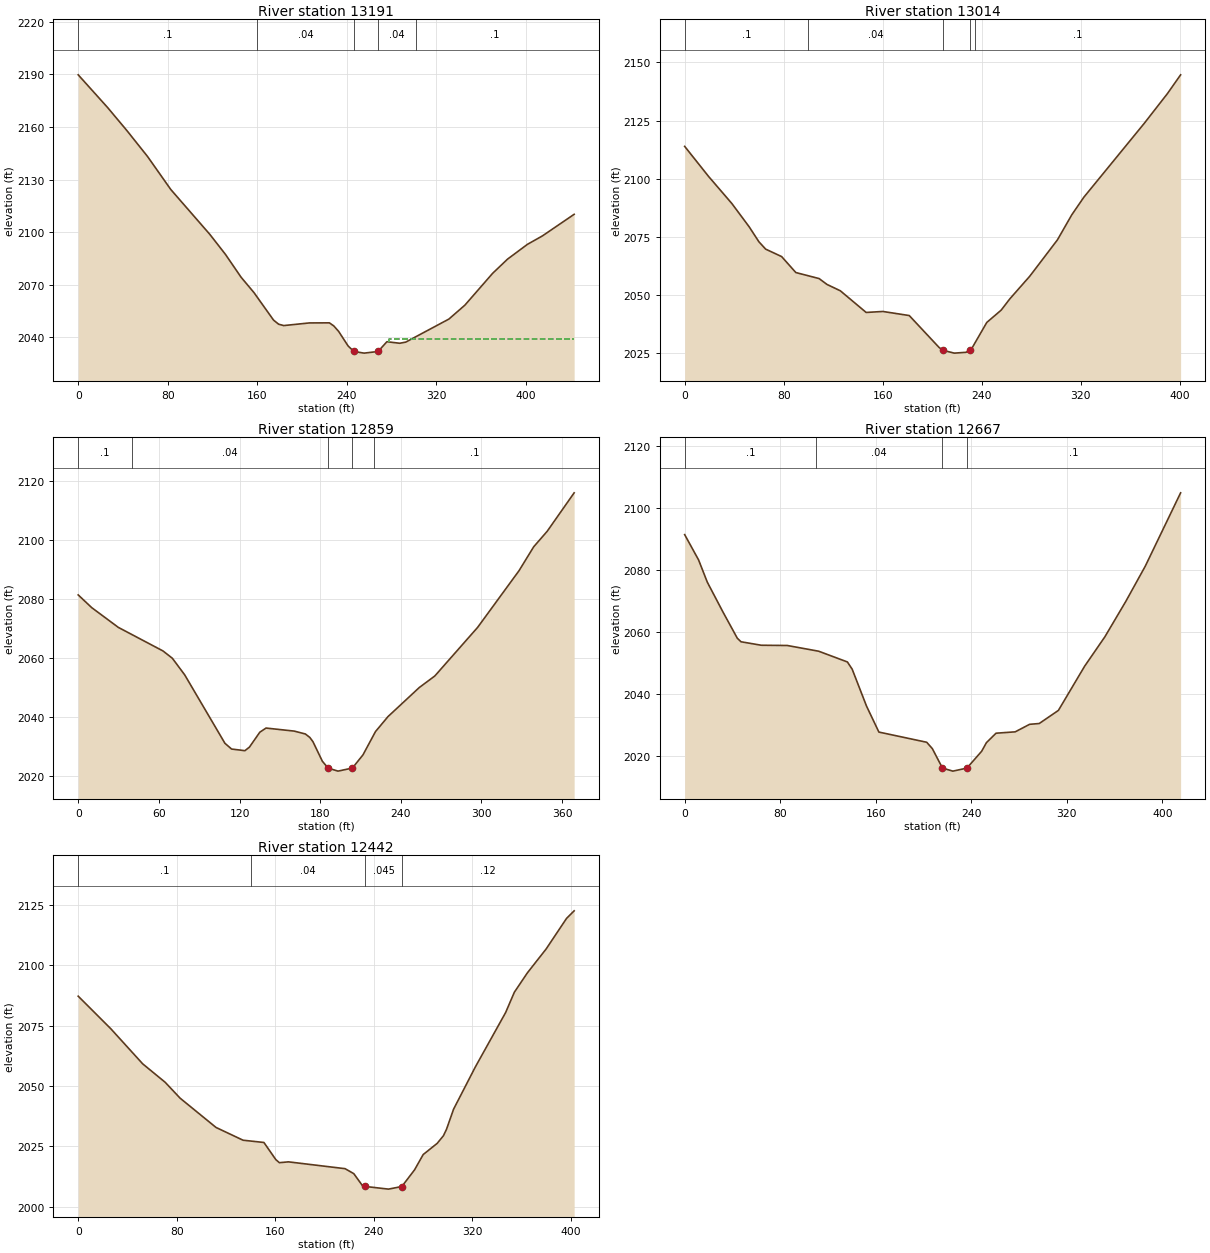
Type RM Length L Ch R = 1 ,13191   ,175.2,176.9,177.9
XS GIS Cut Line= 4
1983252.93617452202539.6143797781983400.52679369202387.924021185
1983494.82080039202275.8644769991983552.22939221202213.176934211
#Sta/Elev= 30
       02189.805  26.2512171.151  43.3912158.077  61.9522143.197  82.7072124.374
 117.6352098.741 131.5562087.345 145.4762074.353 157.0772065.502 174.5072049.851
 179.0842047.498 183.6622046.721 206.5492048.229 224.4062048.284 228.3112046.536
 232.5992043.479 241.1742035.059  246.322031.936 255.4352030.999  267.912031.936
 275.8182037.517 287.2752036.629 292.6282037.278 331.2182050.442 345.4872058.377
 370.2482076.524 383.5942084.638 401.3892093.083 414.7352097.884   443.12110.213
#Mann= 5 ,-1 , 0
       0      .1       0     160     .04       0  246.32    .045       0
  267.91     .04       0  301.64      .1       0
#XS Ineff= 2 , 0
                          278.11         2039.22
Permanent Ineff=
       F       F
Bank Sta=246.32,267.91
XS Rating Curve= 0 ,0
Exp/Cntr(USF)=0,0
Exp/Cntr=0.3,0.1

Type RM Length L Ch R = 1 ,13014   ,156.8,155.1,155.2
XS GIS Cut Line= 4
1983392.32731485202638.0081258921983503.02027923202530.048321128
1983605.51376477202423.4550961711983671.69047142202350.874192104
#Sta/Elev= 30
       02113.864  19.3262100.928  38.1222089.287  52.2182079.187  60.0042072.809
   65.442069.662  78.3362066.462   89.812059.593 108.6052057.003 114.9992054.474
 125.7632051.746 146.6432042.424 160.1152042.849 181.4482041.094  205.632027.326
  209.122026.078 217.8342024.927 227.3012025.277  230.242026.097 232.4952027.409
 244.0972038.129 255.7022043.407  262.66 2048.23 278.9022058.059  301.212073.667
 312.7912084.433  322.53    2092 371.2252123.703 390.0382136.554 400.7192144.648
#Mann= 5 ,-1 , 0
       0      .1       0     100     .04       0  209.12    .045       0
  230.24     .04       0  234.62      .1       0
Bank Sta=209.12,230.24
XS Rating Curve= 0 ,0
Exp/Cntr(USF)=0,0
Exp/Cntr=0.3,0.1

Type RM Length L Ch R = 1 ,12859   ,193.8,191.9,190.1
XS GIS Cut Line= 4
1983513.95291769202752.8008296921983606.88034457202647.574184542
1983676.57591474202566.9459759211983759.88409679202477.842442076
#Sta/Elev= 30
       02081.367   10.022077.057  29.8452070.338  63.0452062.342  70.018 2059.86
  79.2322054.208 109.1472030.972 114.1042029.015 124.0162028.464  127.382029.669
   135.12034.735 139.7492036.145 160.6822035.111 168.9692034.137 172.3132032.953
 174.6392031.514 181.6172024.884  185.932022.554 193.2472021.516  203.982022.562
 211.8552027.043 221.1592034.952 230.463 2040.04  253.712049.902 265.3162053.845
 297.1812070.363 327.9882089.625 338.8262097.699 348.8792102.977 368.9442116.043
#Mann= 5 ,-1 , 0
       0      .1       0      40     .04       0  185.93    .045       0
  203.98     .04       0  220.39      .1       0
Bank Sta=185.93,203.98
XS Rating Curve= 0 ,0
Exp/Cntr(USF)=0,0
Exp/Cntr=0.3,0.1

Type RM Length L Ch R = 1 ,12667   ,231,225.3,220.8
XS GIS Cut Line= 4
1983661.54353686202909.9575075141983754.47096374202777.399266221
1983843.29865121202651.6739239641983891.40477218 202564.65844044
#Sta/Elev= 30
       02091.387  11.6362083.254  18.9362076.086  32.0672066.457  44.0872058.005
  47.2012056.871   64.122055.755  85.9372055.674 112.2012053.828 136.2412050.374
 140.2482048.043 152.2682036.146 162.6182027.782 202.6362024.503 207.3442022.463
  215.872016.176  224.552015.202  236.312016.169 248.653  2021.6  252.672024.378
 260.7042027.417 276.7722027.859 288.8242030.283 296.8582030.537 312.9262034.763
 334.9342049.034 351.8332058.471 369.3522069.875 385.6312081.205 415.2532104.856
#Mann= 4 ,-1 , 0
       0      .1       0     110     .04       0  215.87    .045       0
  236.31      .1       0
Bank Sta=215.87,236.31
XS Rating Curve= 0 ,0
Exp/Cntr(USF)=0,0
Exp/Cntr=0.3,0.1

Type RM Length L Ch R = 1 ,12442   ,180.4,178.7,175.4
XS GIS Cut Line= 4
1983888.39578484203038.4160093861983969.02399347202883.992491178
1984029.15350498202730.9355527781984053.01867566202671.272626086
#Sta/Elev= 30
       02087.193  26.4912073.714  52.3982059.187  70.6332051.569  82.791 2044.98
 111.9692032.863 133.9122027.586 150.8742026.642   160.6 2019.52 163.4322018.286
 170.8342018.624 216.8192015.802 223.8692013.749 230.9182008.779   233.32008.439
 252.0682007.338  262.892008.416 273.2182015.287 280.2672021.646 291.6432026.285
 296.7042029.431 299.2352032.137 304.9422040.416 322.5672057.843 347.2622080.446
 354.3292088.836  364.932096.861 380.1072106.706 396.7322119.388 402.9092122.526
#Mann= 4 ,-1 , 0
       0      .1       0     140     .04       0   233.3    .045       0
  262.89     .12       0
Bank Sta=233.3,262.89
XS Rating Curve= 0 ,0
Exp/Cntr(USF)=0,0
Exp/Cntr=0.3,0.1