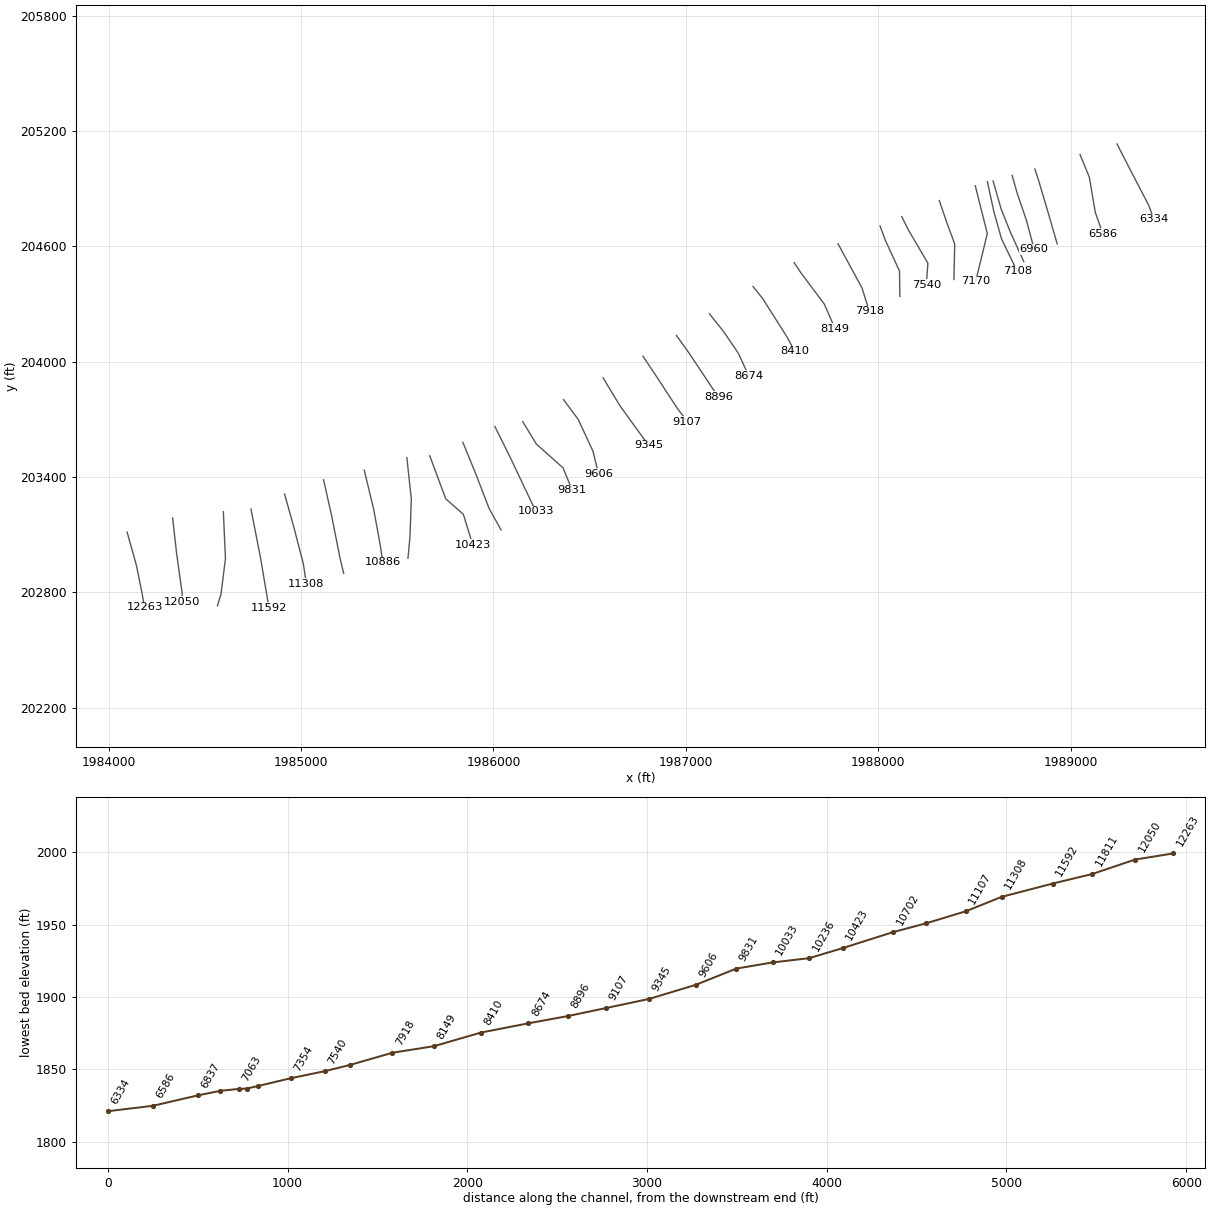
HEC-RAS study PIPESTCK2_A.prj: PIPESTCK2_A

--- PIPESTCK2_A.g01 (geometry) --- (continued)

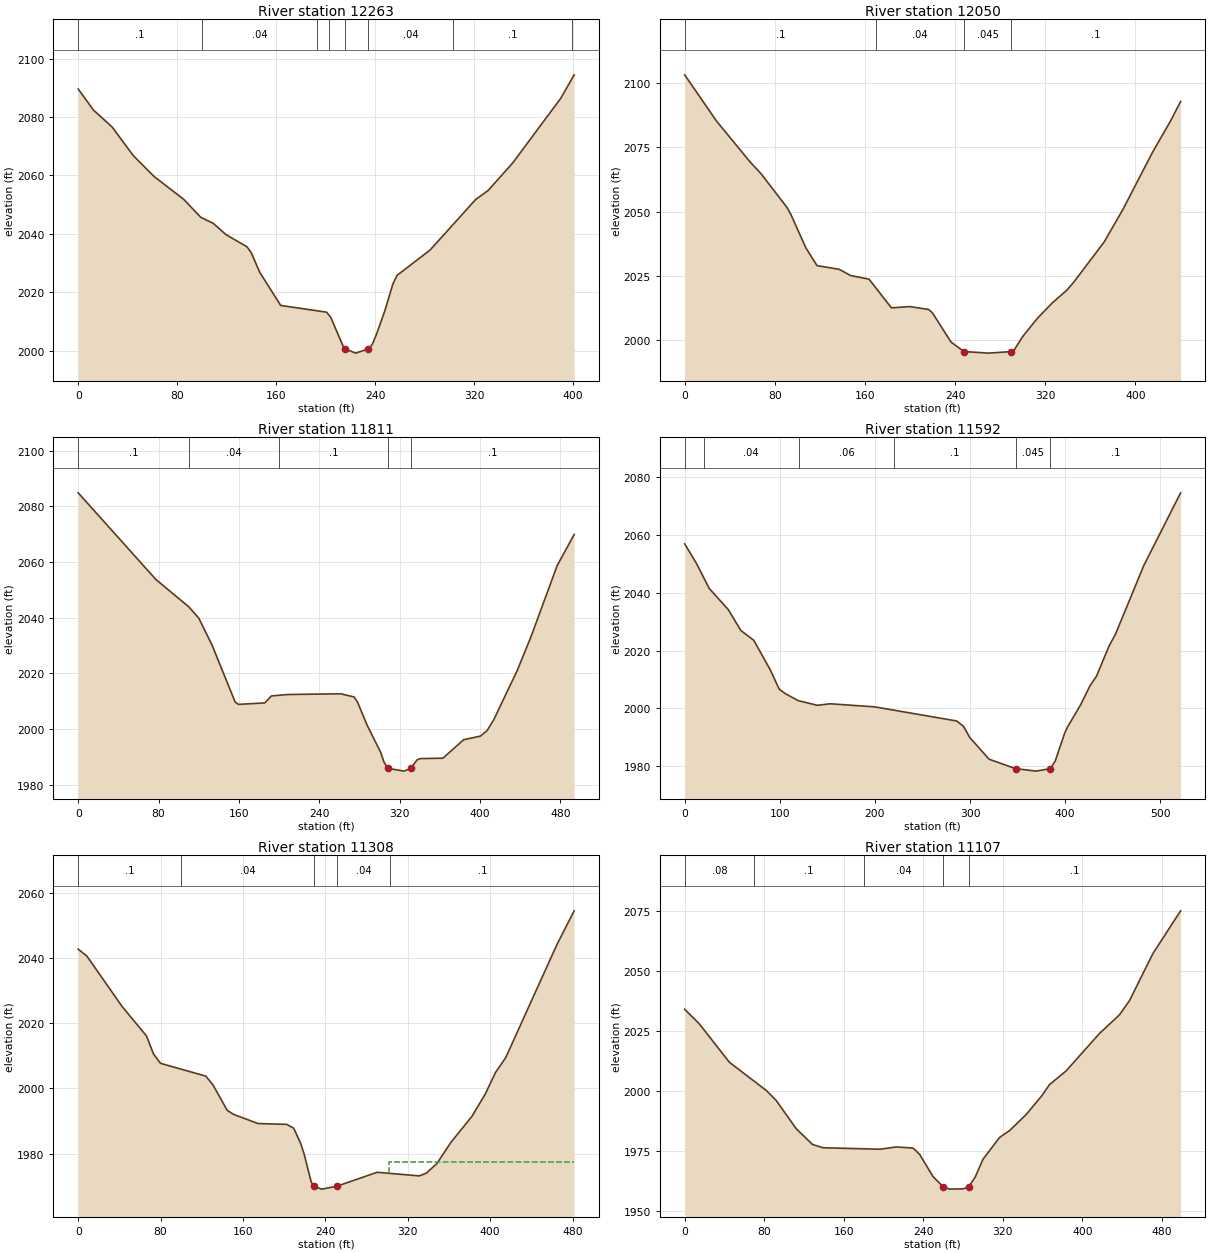
Type RM Length L Ch R = 1 ,12263   ,214.5,213.4,213.2
XS GIS Cut Line= 4
1984096.11591553203113.5778987791984145.31278859202937.289103657
1984174.01096454202793.7982239071984186.20193638202723.192178661
#Sta/Elev= 30
       02089.575  12.369 2082.36  27.4772076.551  44.5082066.799  61.5392059.575
  85.3832051.796  99.0072045.698 109.2262043.588 119.4452039.754 136.4762035.576
 139.882 2033.59 146.6942026.925 163.7252015.503 200.8712013.193 204.2172011.423
 214.2542001.501  216.072000.625 224.2921999.182   234.62000.626 237.6752002.082
 241.0212005.469 247.7122013.391 254.4042022.785  257.752025.784 284.5162034.468
  321.322051.739 331.3482054.813 351.3242064.257  390.212086.429 401.0082094.433
#Mann= 8 ,-1 , 0
       0      .1       0     100     .04       0  193.02      .1       0
  203.02     .04       0  216.07    .045       0   234.6     .04       0
  303.02      .1       0  399.36     .12       0
Bank Sta=216.07,234.6
XS Rating Curve= 0 ,0
Exp/Cntr(USF)=0,0
Exp/Cntr=0.3,0.1

Type RM Length L Ch R = 1 ,12050   ,243.5,238.4,229.2
XS GIS Cut Line= 4
1984332.53422217203187.3732083641984353.03291927203005.618094014
1984381.73109522202797.8979633281984383.09579808202750.474538916
#Sta/Elev= 30
       02103.247  28.2612085.246  57.9762069.384  67.8812064.706  90.9922051.501
  94.2942048.857   107.52035.938 117.405    2029 137.2152027.531  147.122025.152
 163.6282023.709  183.442012.562     2002013.049  216.562011.904 219.8722010.591
 236.4321999.198  247.811995.546 269.5511994.936  289.761995.533 292.7351996.377
 299.3592001.066 312.607  2008.3 325.8552014.357 339.1032019.439 345.7272022.837
 372.2232038.194 388.7832050.805 415.0752073.056 431.4862085.588 440.044 2092.89
#Mann= 4 ,-1 , 0
       0      .1       0     170     .04       0  247.81    .045       0
  289.76      .1       0
Bank Sta=247.81,289.76
XS Rating Curve= 0 ,0
Exp/Cntr(USF)=0,0
Exp/Cntr=0.3,0.1

Type RM Length L Ch R = 1 ,11811   ,210.9,219.7,226.7
XS GIS Cut Line= 4
1984596.28412495203220.171123736 1984607.2167634202975.553338257
1984583.98490668202791.0650642921984565.47374545202731.016663219
#Sta/Elev= 30
       02084.882  77.3622053.743 110.2032043.899 120.0562039.849 133.1922030.231
 156.1812009.782 159.4652008.906 185.7382009.431 192.3062011.937 208.7272012.451
 261.3862012.719 274.6122011.569 277.9192009.791 287.8392001.249 301.0661991.681
 304.3731988.183  308.361985.934 324.2141984.938  331.051985.924 337.4411989.024
 340.7471989.452 362.9341989.577 383.7351996.231 400.2691997.508 406.8821999.446
 413.4962003.307 436.8662020.986 450.599 2033.12 476.7452058.753 493.6442069.913
#Mann= 5 ,-1 , 0
       0      .1       0     110     .04       0     200      .1       0
  308.36    .045       0  331.05      .1       0
Bank Sta=308.36,331.05
XS Rating Curve= 0 ,0
Exp/Cntr(USF)=0,0
Exp/Cntr=0.3,0.1

Type RM Length L Ch R = 1 ,11592   ,274.5,283.7,290.2
XS GIS Cut Line= 4
 1984739.7750047203233.8369218071984787.60529795202990.585716136
1984823.13637293202781.4990056421984832.54556389202720.809723929
#Sta/Elev= 30
       02056.895  12.4452050.123  25.819 2041.48  45.8812034.168  58.9922026.968
  72.6312023.571  89.7292013.515   99.382006.673 106.0672005.067 119.4422002.696
 139.5042001.097 152.8782001.619  199.692000.557 285.9981995.673 293.0971993.848
 299.753 1989.96 320.1321982.439  347.891979.201 369.6381978.337  384.44 1979.21
 389.6061981.866 399.5891991.547 402.6221993.654 416.2292001.241 426.2122007.895
 432.8682011.088 446.1792021.571 452.8352025.612 482.7322049.444 521.4082074.542
#Mann= 6 ,-1 , 0
       0     .08       0      20     .04       0     120     .06       0
     220      .1       0  347.89    .045       0  384.44      .1       0
Bank Sta=347.89,384.44
XS Rating Curve= 0 ,0
Exp/Cntr(USF)=0,0
Exp/Cntr=0.3,0.1

Type RM Length L Ch R = 1 ,11308   ,202.5,201.4,200.1
XS GIS Cut Line= 4
1984914.69722001203311.7319708151984961.16093345203145.009234343
1985011.72438632202950.9549017281985027.88737883 202844.27915115
#Sta/Elev= 30
       02042.668   8.3932040.567  42.4522025.175  66.2932016.085  73.1052010.563
  79.9162007.698 123.9572003.771 131.004 2001.01 144.6281993.313 150.5931992.101
 174.5791989.259 202.3931989.008 209.1741987.854 215.9551983.191 219.3451979.929
 226.1261971.485  228.611970.039 236.4391969.171  251.011970.049 290.231 1974.33
 331.2281973.219 338.0081974.077  348.181976.977 361.7411983.456 382.2521991.451
 395.1761998.282 405.131 2004.89 415.0862009.455  464.862044.115 481.5032054.406
#Mann= 5 ,-1 , 0
       0      .1       0     100     .04       0  228.61    .045       0
  251.01     .04       0  303.08      .1       0
#XS Ineff= 2 , 0
                          301.35         1977.63
Permanent Ineff=
       F       F
Bank Sta=228.61,251.01
XS Rating Curve= 0 ,0
Exp/Cntr(USF)=0,0
Exp/Cntr=0.3,0.1

Type RM Length L Ch R = 1 ,11107   ,221.2,220.7,220.8
XS GIS Cut Line= 4
1985116.95103147203386.8938602071985159.31500549203198.305846822
1985201.67897951  202983.75281711985221.67737772202899.315135773
#Sta/Elev= 30
       02034.167  14.7072028.101  44.9712012.052  81.9592000.325  92.0471996.128
 112.2221984.307 128.5041977.772 139.1231976.383 196.2711975.772 212.9921976.722
 229.7131976.247 236.4011973.581 249.7781964.333  260.141960.046 266.4991959.118
 279.8751959.219  285.511960.045 292.168 1964.11  299.941971.543 316.6611980.682
 326.6941983.521 343.4151990.237 359.1941998.105 366.8242002.713 383.5452008.436
 417.0282024.018 437.257 2031.85 447.3722037.797 470.9732057.482 498.7572075.256
#Mann= 5 ,-1 , 0
       0     .08       0      70      .1       0     180     .04       0
  260.14    .045       0  285.51      .1       0
Bank Sta=260.14,285.51
XS Rating Curve= 0 ,0
Exp/Cntr(USF)=0,0
Exp/Cntr=0.3,0.1

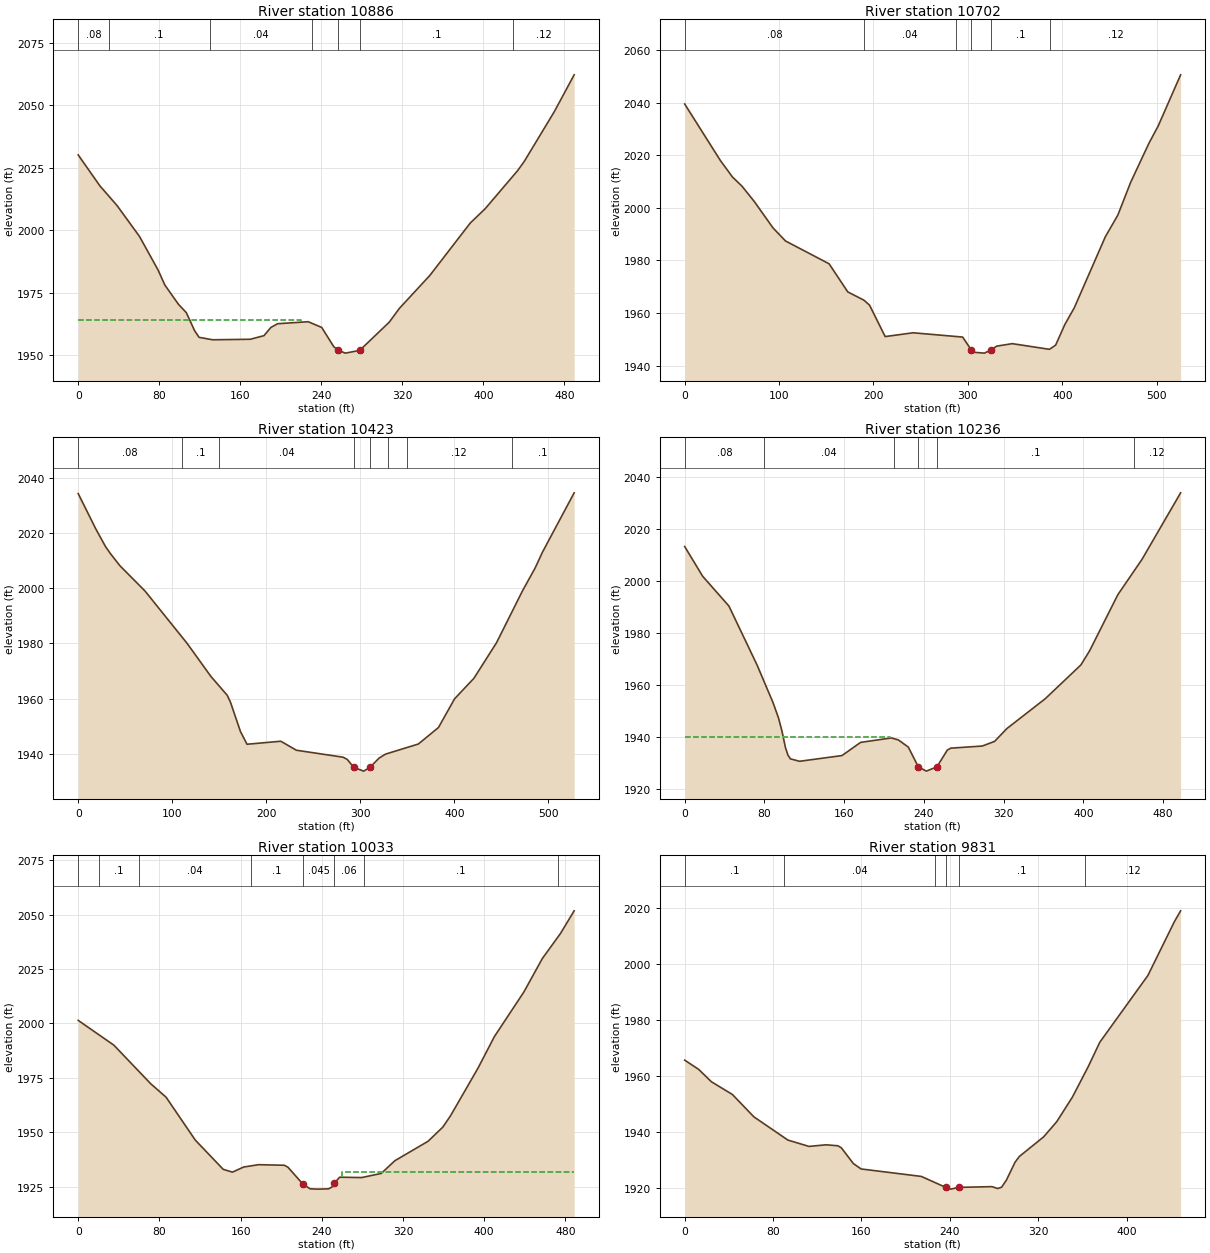
Type RM Length L Ch R = 1 ,10886   ,187.3,183.7,178.5
XS GIS Cut Line= 4
1985328.77090157203436.0907332651985377.96777463203231.103762193
1985412.13226981203045.2489084211985425.00097986 202956.24033055
#Sta/Elev= 30
       02030.084  21.4892017.668  38.359 2009.83  60.4951997.489  78.8471984.064
  85.595 1978.02  99.0911970.287 106.7521967.004 114.9141959.806 119.3351957.125
 132.8311956.146 169.9451956.354 183.4411957.795 190.1891961.062 196.9371962.571
 227.1161963.368 240.4591961.079 252.3921953.361  257.011951.907  263.811950.808
  277.961951.907 307.1751963.206 317.1551968.709 347.2051981.879 387.2352002.896
 401.7912008.528 433.722 2023.71 440.352 2027.42 470.1872047.421 489.7112062.111
#Mann= 7 ,-1 , 0
       0     .08       0      30      .1       0     130     .04       0
  230.81      .1       0  257.01    .045       0  277.96      .1       0
  429.78     .12       0
#XS Ineff= 2 , 0
          220.39  1964.2
Permanent Ineff=
       F       F
Bank Sta=257.01,277.96
XS Rating Curve= 0 ,0
Exp/Cntr(USF)=0,0
Exp/Cntr=0.3,0.1

Type RM Length L Ch R = 1 ,10702   ,263.2,279.1,295.8
XS GIS Cut Line= 4
1985550.15683033203501.6865640081985573.38868705203285.766954479
1985566.55578802203093.0792016711985555.99053615202978.182087637
#Sta/Elev= 30
       02039.533  37.9792017.942  50.6932011.725  60.5932008.308  73.7922002.411
   93.591992.375 106.7891987.416 152.986 1978.73 172.7851968.024 189.9191964.884
 195.8781962.969 212.3821951.031 241.9521952.478 294.4791950.844  303.661945.896
  307.611945.022 317.4591944.736  324.041945.861 330.5911947.397 347.0051948.342
   386.41946.185 392.9661947.778 402.8141955.699 412.673 1961.95 445.6191989.018
 458.7981997.211 472.4032009.695 491.7452024.552 501.6292031.191 525.3572050.629
#Mann= 6 ,-1 , 0
       0     .08       0     190     .04       0  287.17      .1       0
  303.66    .045       0  324.04      .1       0  387.17     .12       0
Bank Sta=303.66,324.04
XS Rating Curve= 0 ,0
Exp/Cntr(USF)=0,0
Exp/Cntr=0.3,0.1

Type RM Length L Ch R = 1 ,10423   ,193.6,186.5,175.4
XS GIS Cut Line= 4
1985669.04927355203511.2526226581985752.41064179203287.133534286
1985843.97148887203206.505325664 1985892.6978286203047.582494551
#Sta/Elev= 30
       02034.278  18.4772021.627  28.9782015.109  34.2542012.537  44.4592008.097
  70.9831999.001 115.8991979.969 140.9921968.077 158.494 1961.19 161.9941958.621
 172.496 1948.09 179.4971943.462 215.4051944.559 232.0031941.294 281.6921938.768
 286.0631937.972   293.1 1935.07 303.5231933.724   310.2 1935.08 319.7951938.412
 326.7681939.885 361.7041943.549 383.053 1949.52 400.2111959.924 420.8011967.377
 444.8221980.256 472.2751998.951 486.0012007.412 493.5312012.976 527.3462034.555
#Mann= 8 ,-1 , 0
       0     .08       0     110      .1       0     150     .04       0
   293.1    .045       0   310.2     .04       0  329.12      .1       0
  349.12     .12       0  461.12      .1       0
Bank Sta=293.1,310.2
XS Rating Curve= 0 ,0
Exp/Cntr(USF)=0,0
Exp/Cntr=0.3,0.1

Type RM Length L Ch R = 1 ,10236   ,202.6,203.2,204.9
XS GIS Cut Line= 4
1985841.23832925203580.9481928221985909.56731961 203414.22545635
1985977.89630997203236.5700814221986039.77868535203125.545819712
#Sta/Elev= 30
       0 2013.13   18.072001.681  44.398 1990.24  72.7631967.459  88.4891953.261
  94.0371947.353  97.5831942.222 101.1291935.825 103.5791932.951 106.0941931.481
 115.3111930.542 157.8591932.747 176.5131937.808 207.2641939.516 214.2941938.786
 224.3871936.012  234.48 1928.38 242.4841926.759  253.131928.408 263.5061934.838
 267.0211935.594 298.657 1936.41  311.03 1938.21 323.2631943.114 361.9291954.645
 397.5471967.583 406.4131973.102 434.5931994.565 458.9972008.255 497.6292033.771
#Mann= 6 ,-1 , 0
       0     .08       0      80     .04       0  210.18      .1       0
  234.48    .045       0  253.13      .1       0  450.52     .12       0
#XS Ineff= 2 , 0
          206.15 1939.73
Permanent Ineff=
       T       F
Bank Sta=234.48,253.13
XS Rating Curve= 0 ,0
Exp/Cntr(USF)=0,0
Exp/Cntr=0.3,0.1

Type RM Length L Ch R = 1 ,10033   ,192,201.9,225.8
XS GIS Cut Line= 4
1986007.96106573203662.9429812511986088.58927435  203500.3199842
1986200.64881853203263.9016775641986220.25620003203222.856892299
#Sta/Elev= 30
       02001.423  35.1561990.022  71.458 1972.27  86.5671966.111 115.4011946.336
 142.8741932.912 152.0211931.628 163.0071933.979 177.6541935.057 203.1021934.789
 206.7331933.861   221.31926.139 228.5171923.958 235.7791923.813 246.6711923.934
 250.3021924.881   252.51926.654 257.5631929.296 279.347 1929.14 298.4871931.019
 312.0241936.886   344.71945.825 359.2231952.322 366.7871957.514 393.8831979.445
 410.053 1993.97 439.0992014.482 457.2732029.857 475.1342041.372 488.6322051.808
#Mann= 8 ,-1 , 0
       0     .08       0      20      .1       0      60     .04       0
     170      .1       0   221.3    .045       0   252.5     .06       0
  281.51      .1       0  473.14     .12       0
#XS Ineff= 2 , 0
                          260.12         1931.86
Permanent Ineff=
       F       T
Bank Sta=221.3,252.5
XS Rating Curve= 0 ,0
Exp/Cntr(USF)=0,0
Exp/Cntr=0.3,0.1

Type RM Length L Ch R = 1 ,9831    ,230.7,225.1,230.4
XS GIS Cut Line= 4
1986152.53251999203688.5431995581986223.55527359203571.633858457
1986361.90523578203448.3899515291986409.99841273203331.129059412
#Sta/Elev= 30
       0 1965.73    12.7  1962.4    24.2 1957.98    43.2 1953.43    62.6 1945.44
    93.4 1937.12   112.5 1934.85   127.9 1935.43   138.7 1935.08   141.8 1934.34
   152.6 1928.74   159.6 1926.79   214.1 1924.12   236.3 1920.19   240.9 1919.57
   247.9 1920.19   278.1 1920.46   283.2 1919.79   286.8 1920.25   291.2 1922.84
     299 1929.22   302.9 1931.27   324.8 1938.25   336.7  1943.7   350.9 1952.51
   365.1 1963.32   375.7 1972.14   419.2 1996.02   443.2 2015.29   448.8 2019.14
#Mann= 6 ,-1 , 0
       0      .1       0      90     .04       0  226.79      .1       0
   236.3    .045       0   247.9      .1       0  362.07     .12       0
Bank Sta=236.3,247.9
XS Rating Curve= 0 ,0
Exp/Cntr(USF)=0,0
Exp/Cntr=0.3,0.1

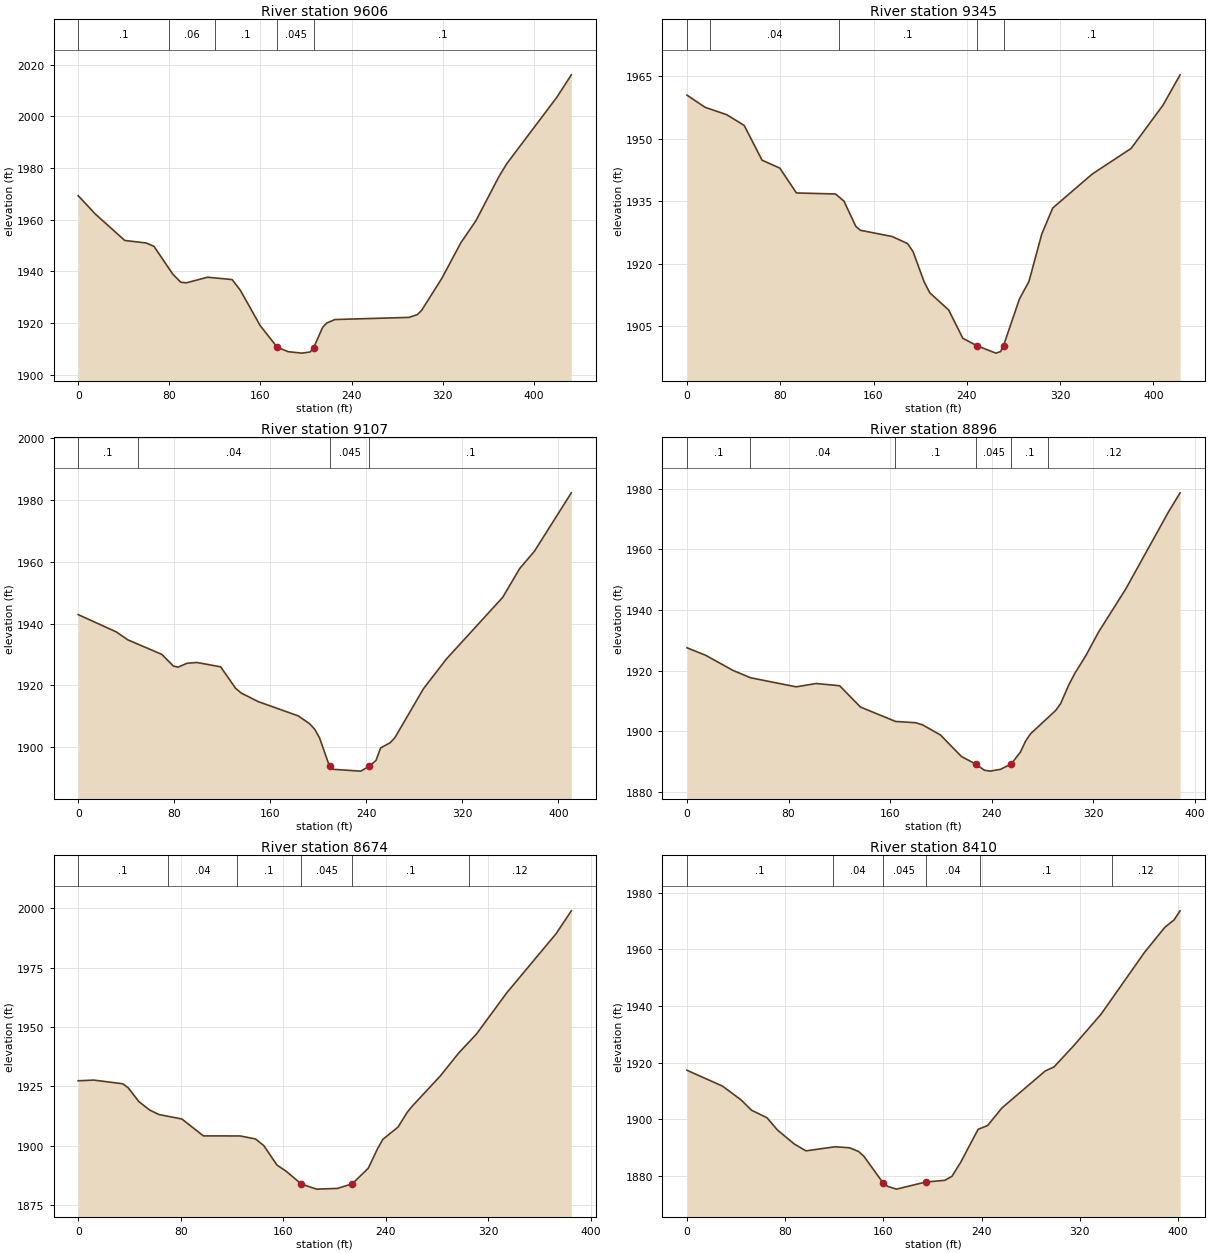
Type RM Length L Ch R = 1 ,9606    ,256.3,261.2,261.9
XS GIS Cut Line= 4
1986364.54431172203803.2349242591986441.16686459203699.840636044
1986517.69533379203534.4844793791986546.73713851203416.039471889
#Sta/Elev= 30
       0 1969.28    15.1 1962.14    40.9 1951.95    59.7 1950.96    66.5 1949.69
    83.1 1938.88    90.1 1935.77      95 1935.56   113.6 1937.72   135.1 1936.81
   142.3 1932.72   159.7 1919.05   174.8 1910.59   184.5  1908.9   196.5 1908.35
   203.7 1908.82   206.7 1910.43   214.6 1918.33   218.2    1920   225.4 1921.35
   290.5 1922.18   297.7 1923.26   301.4 1924.84   319.3 1937.33   335.8 1950.96
   349.3 1959.69   369.5 1976.78   376.3 1981.68   420.2 2007.35   432.9 2016.03
#Mann= 5 ,-1 , 0
       0      .1       0      80     .06       0     120      .1       0
   174.8    .045       0   206.7      .1       0
Bank Sta=174.8,206.7
XS Rating Curve= 0 ,0
Exp/Cntr(USF)=0,0
Exp/Cntr=0.3,0.1

Type RM Length L Ch R = 1 ,9345    ,239.9,238.5,237.2
XS GIS Cut Line= 4
1986570.27546843203916.6057367381986657.08647412203772.269365822
1986774.61233753203609.6463687721986806.95825938 203566.60984564
#Sta/Elev= 30
       0 1960.53    15.6 1957.59    34.1 1955.83    49.1 1953.24    64.4  1944.9
    79.6    1943    93.9 1937.03   127.4 1936.78   134.6 1935.09   144.8 1929.01
   148.7 1928.07   175.9 1926.57   189.2 1924.87   193.9 1922.94   203.3 1915.76
   208.2 1913.06   224.4 1908.94   236.6 1902.12   248.81900.322   264.9 1898.56
     269 1898.93   271.51900.389   285.2  1911.6   293.3 1915.78   304.3 1927.18
   313.7 1933.42   347.6 1941.58   380.9 1947.72   408.2 1958.09   422.9  1965.4
#Mann= 5 ,-1 , 0
       0      .1       0      20     .04       0     130      .1       0
   248.8    .045       0   271.5      .1       0
Bank Sta=248.8,271.5
XS Rating Curve= 0 ,0
Exp/Cntr(USF)=0,0
Exp/Cntr=0.3,0.1

Type RM Length L Ch R = 1 ,9107    ,211.2,210.9,211
XS GIS Cut Line= 4
1986777.41758507204029.0782376711986851.14080673203918.493405187
1986953.63429227203761.3367273651987007.89566774203689.154163667
#Sta/Elev= 30
       0 1942.93    31.8 1937.32    41.2 1934.79    69.6 1930.07    79.3 1926.27
    83.2 1925.94    90.9  1927.2      99 1927.43   118.7 1926.02   131.1 1919.09
   135.9 1917.53     150 1914.77   183.3 1910.16   192.8 1907.61   197.2 1905.74
   201.1    1903   209.4 1893.81   212.8 1892.85   235.4 1892.28   242.6 1893.91
   248.1 1895.75     252 1899.81   259.8 1901.44   263.8 1903.09   287.6 1918.92
   306.8 1928.59   353.6 1948.49   367.7 1957.77   380.1 1963.45   410.8 1982.33
#Mann= 4 ,-1 , 0
       0      .1       0      50     .04       0   209.4    .045       0
   242.6      .1       0
Bank Sta=209.4,242.6
XS Rating Curve= 0 ,0
Exp/Cntr(USF)=0,0
Exp/Cntr=0.3,0.1

Type RM Length L Ch R = 1 ,8896    ,221.3,221.1,218.8
XS GIS Cut Line= 4
1986951.48781593204136.9848241171987017.86354321204044.218747444
1987144.95546527203852.8975744441987170.96807562203816.823482735
#Sta/Elev= 30
       0 1927.51    14.7 1925.03    36.3 1920.02      50 1917.61      86 1914.61
   101.7 1915.71   120.2 1914.97   136.6 1907.93   164.2 1903.18   179.9 1902.77
   185.4 1902.08   199.6  1898.7   216.1  1891.6   227.2 1889.14   234.2 1887.07
   238.7 1886.78   246.9 1887.38   255.41889.196   262.5 1893.08   266.6 1896.71
   270.5 1899.12   290.2 1906.78   294.2 1909.11   300.4 1915.09   305.2 1918.96
   313.9 1924.83   324.1 1932.75   345.4 1946.89     379 1972.31   388.2 1978.66
#Mann= 6 ,-1 , 0
       0      .1       0      50     .04       0  164.07      .1       0
   227.2    .045       0   255.4      .1       0  284.07     .12       0
Bank Sta=227.2,255.4
XS Rating Curve= 0 ,0
Exp/Cntr(USF)=0,0
Exp/Cntr=0.3,0.1

Type RM Length L Ch R = 1 ,8674    ,264.5,264.5,262.3
XS GIS Cut Line= 4
1987122.96759321204249.3589624521987194.15233833204160.378031051
1987273.41396714204044.2187474441987327.73980263203925.946876433
#Sta/Elev= 30
       0 1927.35    12.2 1927.64    34.7 1926.09    38.9 1924.47    47.3 1918.61
    55.7 1915.04      63 1913.14    80.9 1911.25    97.7 1904.13   126.4 1904.12
   138.3 1902.85   144.8 1900.05   155.1 1891.84   162.2 1889.28   174.1 1883.84
     186 1881.72   202.3 1882.02   213.8 1883.97   226.3 1890.51   233.6 1898.81
   237.7  1902.7   249.5 1907.84   256.7 1914.09   260.8 1916.78   282.5 1929.38
   296.9 1939.09   310.7 1947.01   334.2  1964.3     373 1989.41   384.7 1998.92
#Mann= 6 ,-1 , 0
       0      .1       0      70     .04       0  123.95      .1       0
   174.1    .045       0   213.8      .1       0  304.58     .12       0
Bank Sta=174.1,213.8
XS Rating Curve= 0 ,0
Exp/Cntr(USF)=0,0
Exp/Cntr=0.3,0.1

Type RM Length L Ch R = 1 ,8410    ,260.6,261.2,258.8
XS GIS Cut Line= 4
1987349.60840374204391.117929053 1987399.1393094204329.833927137
1987526.23123146204128.9466954871987566.36405175204053.874713999
#Sta/Elev= 30
       0 1917.29    28.9 1911.71    44.1 1906.82    52.6 1903.17    65.2 1900.52
    73.7 1896.19    87.4 1891.25    96.9 1888.83   120.7 1890.28   132.5 1889.91
   139.7 1888.62     144 1886.97   159.5 1877.64   163.4 1876.29   170.6 1875.31
   194.3  1877.8     210 1878.43   215.8 1879.83   222.9 1884.77   237.1 1896.43
   244.9 1897.79   256.5 1903.98   291.8 1917.06     299  1918.5   314.8 1925.89
   337.2 1937.08   372.7 1958.98   389.2 1967.79   396.7 1970.41   401.6 1973.61
#Mann= 6 ,-1 , 0
       0      .1       0   118.8     .04       0   159.5    .045       0
   194.3     .04       0   238.8      .1       0  346.51     .12       0
Bank Sta=159.5,194.3
XS Rating Curve= 0 ,0
Exp/Cntr(USF)=0,0
Exp/Cntr=0.3,0.1

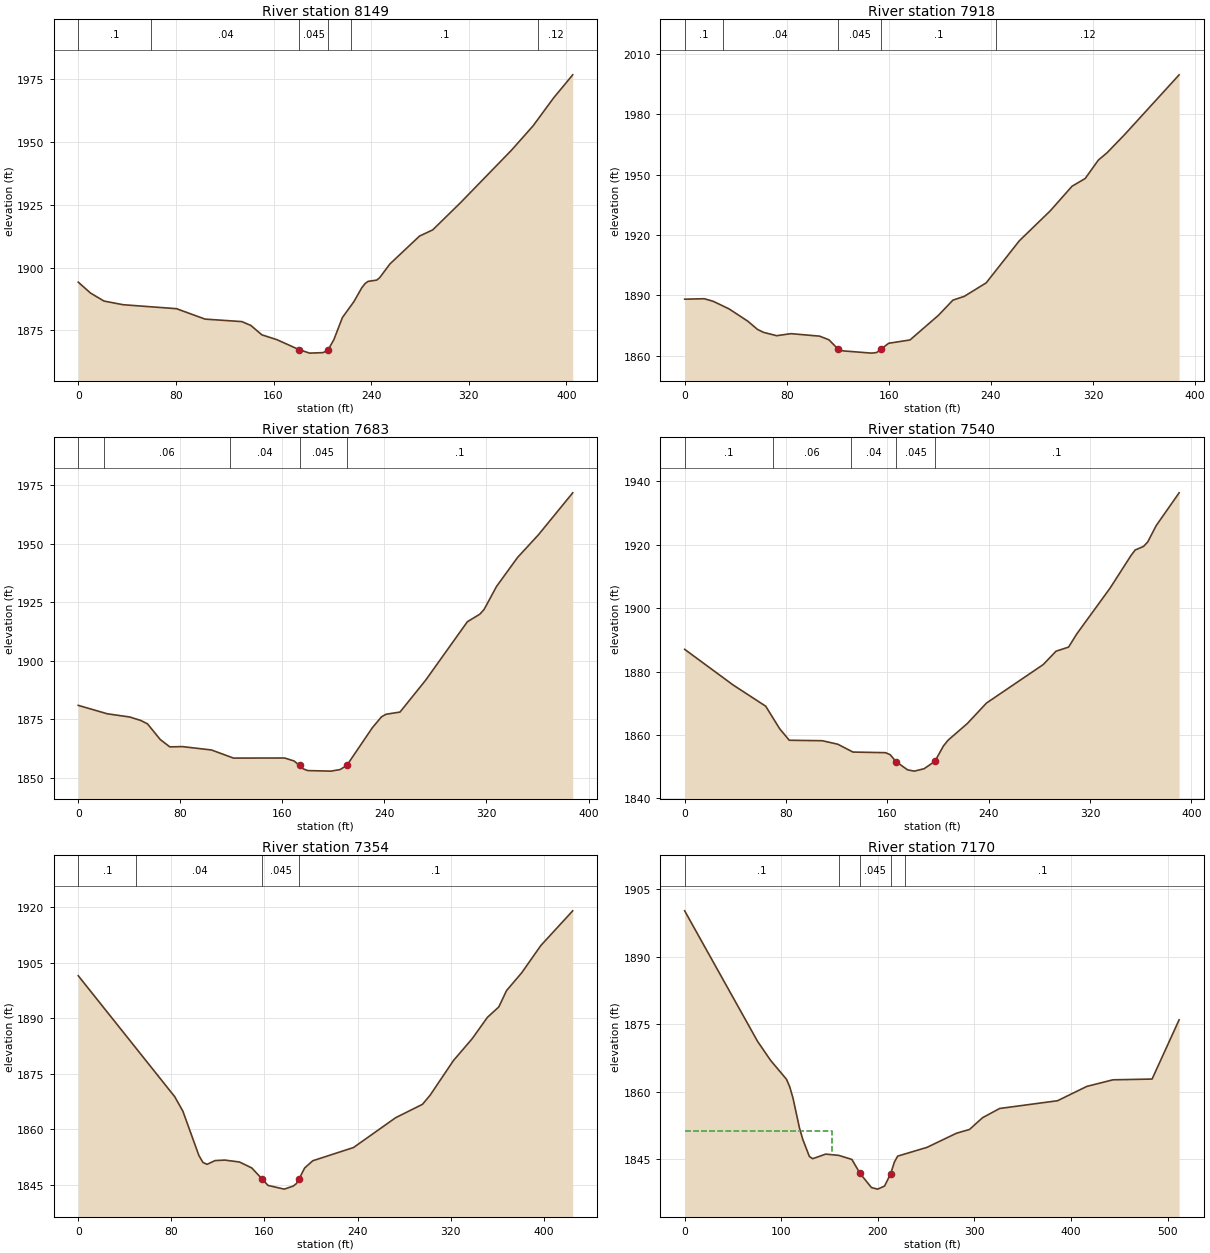
Type RM Length L Ch R = 1 ,8149    ,233.5,231.2,227.7
XS GIS Cut Line= 4
1987563.59126966204515.4566359551987598.65996124 204462.39216843
1987720.28556408 204299.769171381987775.58562269204172.830400481
#Sta/Elev= 30
       0 1894.18    10.1 1889.82    21.1 1886.65    36.8 1885.19    80.5 1883.61
   103.9 1879.46     134 1878.47   141.4 1876.94   150.4  1873.2   162.7 1871.28
   181.2 1867.24   189.6 1865.91   200.6 1866.11   204.61867.137   209.4 1871.26
   216.4 1880.08   225.8  1886.4   232.3 1891.95   235.1 1893.67   237.5 1894.49
   244.5    1895   246.9 1895.93   255.3 1901.41   279.6 1912.54   290.4    1915
   312.9  1925.7   354.8 1946.67   372.7 1956.48   389.3 1967.48   405.1 1976.76
#Mann= 6 ,-1 , 0
       0      .1       0      60     .04       0   181.2    .045       0
   204.6     .04       0  223.61      .1       0  376.68     .12       0
Bank Sta=181.2,204.6
XS Rating Curve= 0 ,0
Exp/Cntr(USF)=0,0
Exp/Cntr=0.3,0.1

Type RM Length L Ch R = 1 ,7918    ,237,234.7,234.4
XS GIS Cut Line= 4
1987791.43839917204613.7175587741987826.87878903 204548.48669628
 1987915.7064765204384.4971194231987953.99318179204263.654705846
#Sta/Elev= 30
       0 1888.16    15.4 1888.38    22.3 1887.13    34.8 1883.34    49.7 1877.14
      57 1873.18    61.8 1871.68    72.1 1870.03    83.3 1871.04   105.7 1869.81
   113.1 1867.98   119.91863.593   124.3 1862.48   146.5 1861.37   150.5 1861.68
   154.2 1863.54   159.9 1866.26   176.6 1867.91     199 1880.22   210.2 1887.68
   219.1 1889.56   236.3 1896.27   262.3 1917.18   286.4 1931.96   303.6 1944.26
   313.9  1948.1   324.2 1957.23   331.1 1960.92   344.9 1969.97   387.5 1999.58
#Mann= 5 ,-1 , 0
       0      .1       0      30     .04       0   119.9    .045       0
   154.2      .1       0  244.24     .12       0
Bank Sta=119.9,154.2
XS Rating Curve= 0 ,0
Exp/Cntr(USF)=0,0
Exp/Cntr=0.3,0.1

Type RM Length L Ch R = 1 ,7683    ,140.1,142.6,145.2
XS GIS Cut Line= 4
1988010.04452464204706.3203492111988037.33207934204631.848064516
1988111.12738892 204471.958227081988112.89027334204339.741895714
#Sta/Elev= 30
       0 1881.02    22.8 1877.42    40.3 1876.06      49 1874.58    54.3 1873.12
    64.3 1866.43    71.8 1863.31    81.6 1863.43   104.4 1861.99   121.7 1858.53
   161.8 1858.56   169.1 1857.31   173.61855.374   176.3 1853.95   179.9  1853.2
     198 1852.97   205.2 1853.62   210.5 1855.39   230.5 1871.46   237.7 1876.13
   241.3 1877.23   252.2 1878.16   272.2 1891.67     305 1916.67   314.8 1919.91
   318.1  1921.9   327.9 1931.75   344.3 1944.05   360.7 1953.75   387.6 1971.66
#Mann= 5 ,-1 , 0
       0      .1       0      20     .06       0  119.31     .04       0
   173.6    .045       0   210.5      .1       0
Bank Sta=173.6,210.5
XS Rating Curve= 0 ,0
Exp/Cntr(USF)=0,0
Exp/Cntr=0.3,0.1

Type RM Length L Ch R = 1 ,7540    ,189.7,186.1,180.7
XS GIS Cut Line= 4
1988122.53994471  204755.24699231988158.95768217204682.411517381
1988258.71800809204512.9556212951988250.40168202204400.962430166
#Sta/Elev= 30
       0 1886.99    38.3 1875.75      64 1869.07      75 1861.97    82.6 1858.34
   108.7 1858.19   120.9 1857.09   132.9 1854.62   158.5 1854.43   162.3 1853.78
   166.9  1851.6     176 1849.01   181.4 1848.61     189 1849.36   197.6  1851.7
   204.2 1856.47     208 1858.36   223.2 1863.62   238.3 1870.06   283.1 1882.19
   293.2  1886.4   303.1 1887.69   309.6 1891.85     336 1906.35   352.4 1916.55
   355.7 1918.29   362.3 1919.42   365.6 1920.82   372.3 1925.98   390.4 1936.31
#Mann= 5 ,-1 , 0
       0      .1       0      70     .06       0  131.43     .04       0
   166.9    .045       0   197.6      .1       0
Bank Sta=166.9,197.6
XS Rating Curve= 0 ,0
Exp/Cntr(USF)=0,0
Exp/Cntr=0.3,0.1

Type RM Length L Ch R = 1 ,7354    ,187.3,184.3,182
XS GIS Cut Line= 4
1988317.71579097204838.8321723231988357.11175421204723.408911595
1988398.10914842204612.7159472161988393.94535899204427.843696163
#Sta/Elev= 30
       0 1901.43    82.9 1868.77    89.9 1864.86   103.7 1852.86   107.2    1851
   110.7 1850.51   117.6 1851.52     126 1851.65   138.6 1851.13   149.1 1849.53
   158.1 1846.51   163.1 1844.81     177 1843.81   184.7 1844.63   187.5 1845.32
   189.8 1846.59   194.5  1849.5   201.5 1851.47   236.5 1855.04   272.8 1863.11
   295.8 1866.71   302.4 1869.19   322.4 1878.53   338.5 1884.43   351.6  1890.2
   361.4 1893.01     368 1897.41   381.1 1902.25   397.5 1909.59   424.9 1918.96
#Mann= 4 ,-1 , 0
       0      .1       0      50     .04       0   158.1    .045       0
   189.8      .1       0
Bank Sta=158.1,189.8
XS Rating Curve= 0 ,0
Exp/Cntr(USF)=0,0
Exp/Cntr=0.3,0.1

Type RM Length L Ch R = 1 ,7170    ,61.6,62.1,63.6
XS GIS Cut Line= 4
1988505.14895895204915.1477477991988536.13370894204790.371322145
1988567.56504451204667.379139502 1988507.2007626204418.239285076
#Sta/Elev= 30
       0 1900.21    75.5  1871.2    89.1 1866.94   105.4 1862.79   108.8 1861.09
   112.2 1858.56   118.9 1851.92   122.3 1849.42   129.1 1845.64   132.5 1845.13
     146 1846.15   159.3 1845.88   173.1 1844.97   181.6 1841.85   193.4 1838.72
   199.8 1838.37     207 1839.06   213.3 1841.81   217.1 1844.37   220.5  1845.7
   250.9 1847.65   281.4 1850.79   294.9 1851.63   308.4 1854.24   326.1 1856.29
     386 1858.01   416.4  1861.2   443.4 1862.66   483.9 1862.83   511.9 1875.99
#Mann= 5 ,-1 , 0
       0      .1       0   159.3     .04       0   181.6    .045       0
   213.3     .04       0  228.57      .1       0
#XS Ineff= 2 , 0
          152.92 1851.25
Permanent Ineff=
       F       F
Bank Sta=181.6,213.3
XS Rating Curve= 0 ,0
Exp/Cntr(USF)=0,0
Exp/Cntr=0.5,0.3

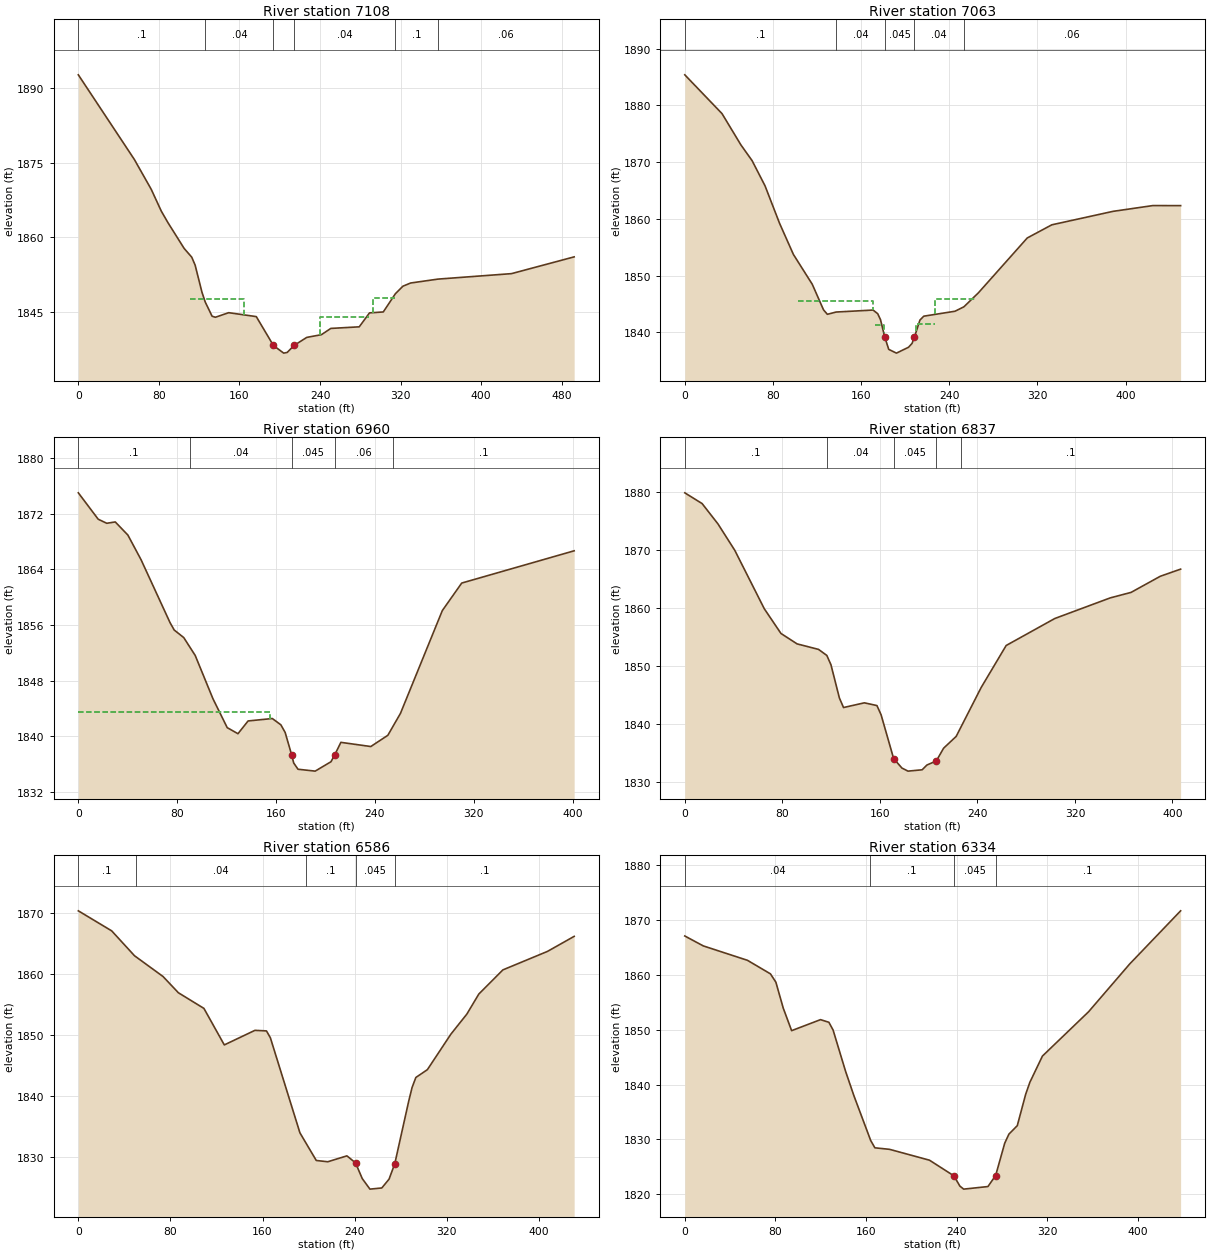
Type RM Length L Ch R = 1 ,7108    ,42.3,44.7,48.7
XS GIS Cut Line= 4
1988568.15746936204936.0628544031988601.17019659204782.382917303
 1988641.5177821204638.9248354681988722.42699537204471.327179415
#Sta/Elev= 30
       0 1892.71    55.6 1875.66    72.4 1869.63    82.4 1865.23    89.1 1862.88
   105.1 1857.71   112.6 1855.96     116 1854.34   122.7 1848.93     126 1846.92
   132.8 1844.06   136.1 1843.85   149.3 1844.77   176.7 1843.98   193.7 1838.16
   203.9 1836.62   207.4 1836.76   214.2 1838.17   226.8 1839.79   241.4 1840.34
   250.7  1841.6   278.9 1841.92   289.1 1844.73   302.8 1844.92   314.8 1848.59
   322.3 1850.11   329.9 1850.75   357.2 1851.54   430.1 1852.64   492.3 1856.02
#Mann= 6 ,-1 , 0
       0      .1       0     126     .04       0   193.7    .045       0
   214.2     .04       0   314.8      .1       0   357.2     .06       0
#XS Ineff= 4 ,-1
  110.94  164.92 1847.47  166.84   175.4 1843.99  239.93  288.24    1844
  292.83  314.08 1847.72
Permanent Ineff=
       F       F       F       F
Bank Sta=193.7,214.2
XS Rating Curve= 0 ,0
Exp/Cntr(USF)=0,0
Exp/Cntr=0.5,0.3

Type RM Length L Ch R = 1 ,7063    ,104.7,103.5,102.2
XS GIS Cut Line= 4
1988597.58066624204940.4653896661988639.74041039204793.364405238
1988688.34391449204672.2022096151988757.17719615204520.708156313
#Sta/Elev= 30
       0  1885.4    33.8 1878.56    50.9 1873.06    61.1 1870.27    72.8 1865.85
      86 1859.24    98.6 1853.74   115.7 1848.49   125.9 1843.99   129.4  1843.2
   137.3  1843.6   170.9 1843.95   175.1  1843.3   177.6 1842.27   181.5 1839.18
   185.1 1837.02   192.1 1836.36   203.1  1837.4   206.3 1838.09   208.4 1839.18
   213.4 1842.18   216.9 1842.87   245.2 1843.74   253.3 1844.52   266.4 1846.97
   310.8 1856.65   333.1 1858.97   388.6 1861.34   424.8 1862.36     450 1862.35
#Mann= 5 ,-1 , 0
       0      .1       0   137.3     .04       0   181.5    .045       0
   208.4     .04       0   253.3     .06       0
#XS Ineff= 4 ,-1
   102.7  170.91 1845.51  172.56  180.58 1841.37  210.11  226.97 1841.55
  227.43  262.97 1845.85
Permanent Ineff=
       F       F       F       F
Bank Sta=181.5,208.4
XS Rating Curve= 0 ,0
Exp/Cntr(USF)=0,0
Exp/Cntr=0.5,0.3

Type RM Length L Ch R = 1 ,6960    ,123.1,122.2,120.8
XS GIS Cut Line= 4
1988696.66156658204969.5210689361988723.10956614204875.630670496
1988770.63005575204736.6556537181988811.07390168204585.119218361
#Sta/Elev= 30
       0 1874.97    16.1 1871.18      23  1870.6    29.9 1870.79    40.1 1868.91
    50.8 1865.36    74.2 1856.35    77.6 1855.28    85.3  1854.2    94.6 1851.63
   108.9 1845.44   120.5 1841.27   129.2  1840.4   137.4 1842.23     157 1842.58
   163.9 1841.68   167.4 1840.58   172.71837.335   174.3  1836.2   177.8  1835.3
   191.7 1835.03   204.5 1836.38   207.51837.357   212.5 1839.16   236.7 1838.56
   250.5 1840.17   260.7 1843.31   294.6 1858.07   310.3 1862.02   401.3 1866.65
#Mann= 5 ,-1 , 0
       0      .1       0      90     .04       0   172.7    .045       0
   207.5     .06       0  254.42      .1       0
#XS Ineff= 2 , 0
          155.17 1843.46
Permanent Ineff=
       F       F
Bank Sta=172.7,207.5
XS Rating Curve= 0 ,0
Exp/Cntr(USF)=0,0
Exp/Cntr=0.3,0.1

Type RM Length L Ch R = 1 ,6837    ,254.1,251.7,247.4
XS GIS Cut Line= 4
1988814.71405728205002.7659338931988835.41468671204939.328521124
 1988891.4444588 204749.373927931988930.79364829204613.057092904
#Sta/Elev= 30
       0 1879.87    14.2 1878.02    27.2 1874.52      41 1869.97    65.2 1859.91
    78.9 1855.65    92.1 1853.86   109.7 1852.91   116.5 1851.87   119.9 1850.26
   126.8 1844.55   130.2  1842.9   147.3 1843.71   157.6 1843.24     161 1841.66
   171.3 1834.11   178.1 1832.48   183.1 1831.95   194.7 1832.18   198.6    1833
   206.31833.703   212.3  1835.9   222.6 1837.93   243.1 1846.35   263.6 1853.58
   303.5 1858.23     349 1861.78   366.1 1862.73     390  1865.5   406.7 1866.73
#Mann= 5 ,-1 , 0
       0      .1       0  116.73     .04       0   171.3    .045       0
   206.3     .04       0  226.73      .1       0
Bank Sta=171.3,206.3
XS Rating Curve= 0 ,0
Exp/Cntr(USF)=0,0
Exp/Cntr=0.3,0.1

Type RM Length L Ch R = 1 ,6586    ,243.5,251.8,260.7
XS GIS Cut Line= 4
1989049.57367357205077.8229342391989097.79800968204959.827218231
1989129.22934524204775.3389442661989168.11255933204665.938714792
#Sta/Elev= 30
       0 1870.37      29 1867.08    48.8    1863    73.6 1859.59    86.9 1856.93
   109.1 1854.36   126.8 1848.37   153.4 1850.76   163.4 1850.67   166.8 1849.55
   192.5 1833.94   206.7 1829.41   216.7  1829.2   233.3 1830.17   240.8 1829.02
   246.6 1826.45   253.3 1824.71   263.6  1824.9   269.9 1826.34   274.91828.889
   286.9 1839.07   289.9 1841.38   293.2 1843.03   303.2 1844.31   323.6 1850.13
   337.5 1853.43   347.9 1856.72   368.8 1860.68   407.5 1863.71   430.7 1866.18
#Mann= 5 ,-1 , 0
       0      .1       0      50     .04       0  197.47      .1       0
   240.8    .045       0   274.9      .1       0
Bank Sta=240.8,274.9
XS Rating Curve= 0 ,0
Exp/Cntr(USF)=0,0
Exp/Cntr=0.3,0.1

Type RM Length L Ch R = 1 ,6334    ,230.8,234.2,235.7
XS GIS Cut Line= 4
1989241.72888111205132.6698783331989316.45077882204987.158814374
1989405.27846629204816.3363384811989434.38361106204740.133777624
#Sta/Elev= 30
       0 1867.13    16.3 1865.32    55.3 1862.69    75.6 1860.22    80.4  1858.7
    86.9 1853.97    94.3 1849.85   119.8 1851.86   127.2 1851.38   130.9 1849.97
   141.9 1842.45   149.3 1837.97   164.1 1829.81   167.8 1828.47   180.8 1828.19
     216 1826.21   237.6 1823.35   242.8 1821.49   246.2 1820.93   267.6  1821.4
   274.4 1823.41   282.4  1829.3   286.1 1830.96   293.5 1832.51   300.9 1838.23
   304.6 1840.42   315.7 1845.21   356.4 1853.29   392.7 1862.01   437.7 1871.72
#Mann= 4 ,-1 , 0
       0     .04       0  163.58      .1       0   237.6    .045       0
   274.4      .1       0
Bank Sta=237.6,274.4
XS Rating Curve= 0 ,0
Exp/Cntr(USF)=0,0
Exp/Cntr=0.3,0.1