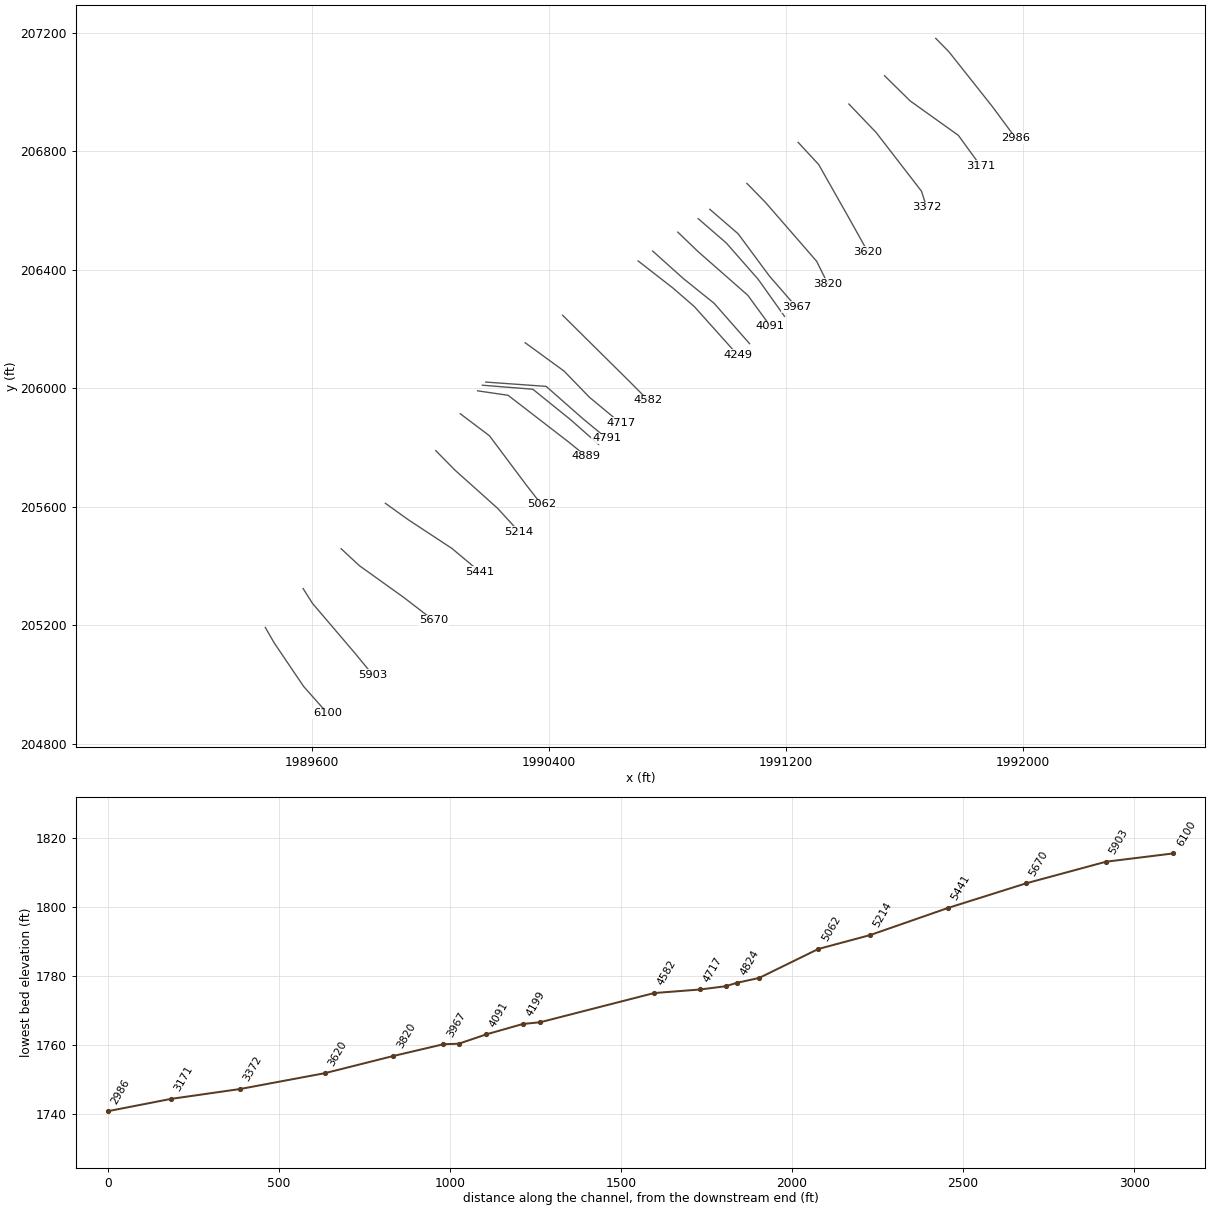
HEC-RAS study PIPESTCK2_A.prj: PIPESTCK2_A

--- PIPESTCK2_A.g01 (geometry) --- (continued)

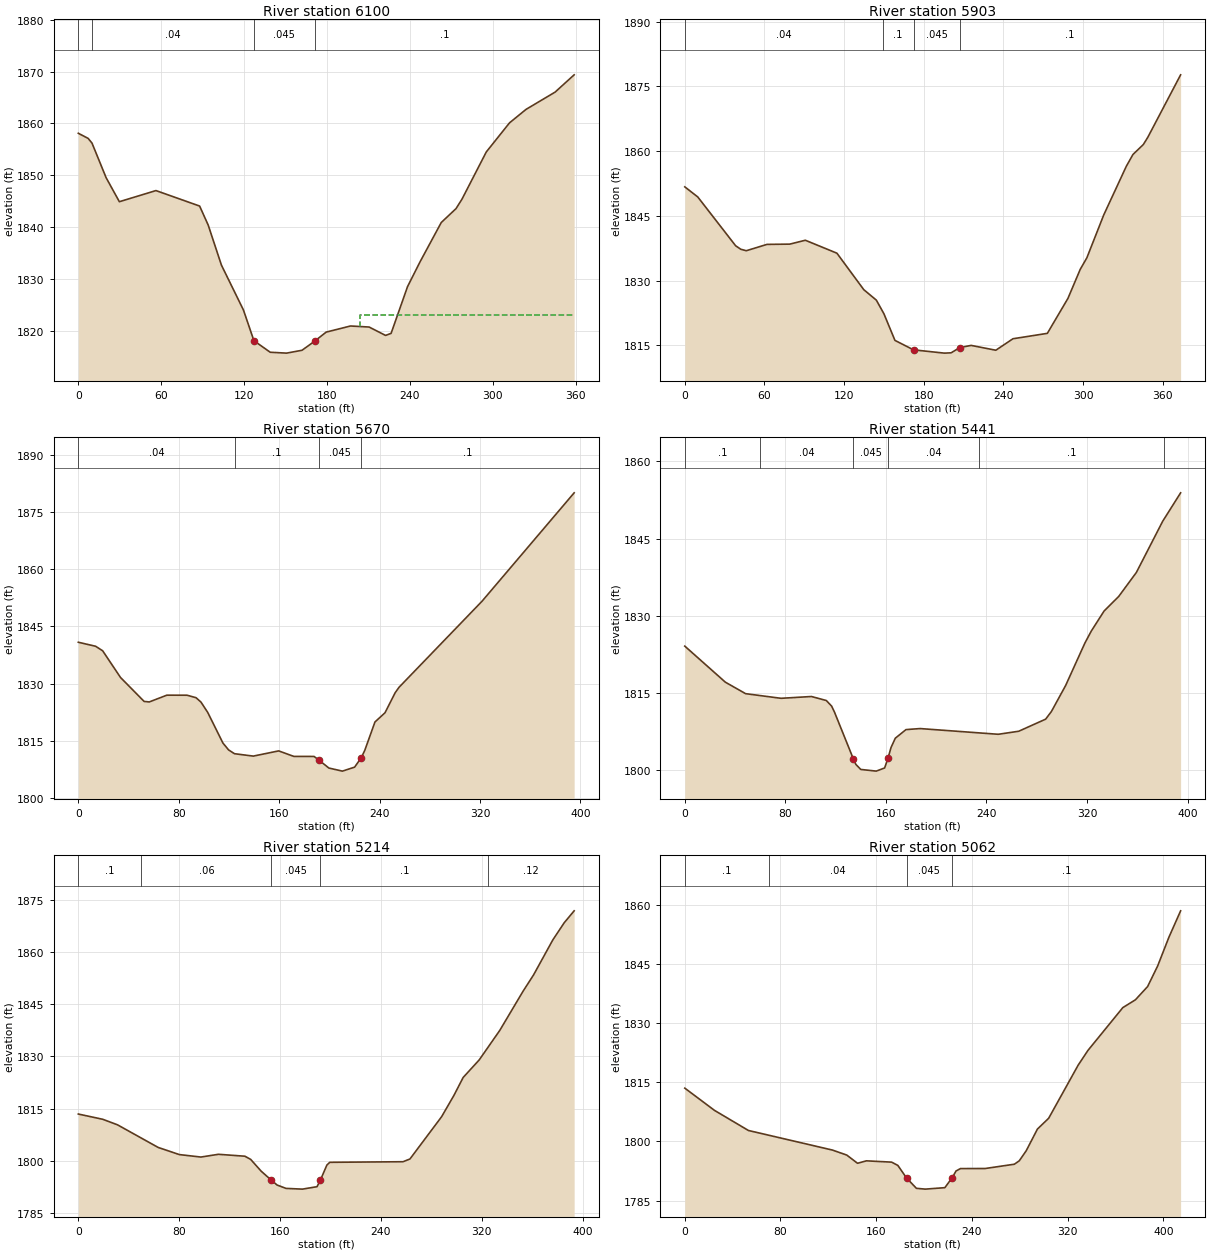
Type RM Length L Ch R = 1 ,6100    ,193.9,197,199.8
XS GIS Cut Line= 4
1989444.15116366205192.9864517021989473.60745664205141.582332581
1989573.36778257204993.9917134091989653.97872188204903.032072433
#Sta/Elev= 30
       0  1858.1     7.1 1857.11     9.9  1856.2    20.1 1849.53    29.7 1844.88
    56.2 1847.03    87.8 1844.04      94 1840.37   103.6 1832.62   119.5 1823.97
   127.1 1818.03   138.9  1815.8   150.7 1815.63   161.9 1816.18     1711817.926
   179.4 1819.69     197 1820.87   210.5 1820.67   222.4 1819.05   226.4 1819.45
   238.3 1828.48   247.4 1833.29   262.7 1840.86   273.4 1843.55   277.7 1845.37
   295.3 1854.49   312.1 1860.11   324.1 1862.72   345.1 1866.05   358.9 1869.39
#Mann= 4 ,-1 , 0
       0      .1       0      10     .04       0   127.1    .045       0
     171      .1       0
#XS Ineff= 2 , 0
                           203.9         1823.02
Permanent Ineff=
       F       F
Bank Sta=127.1,171
XS Rating Curve= 0 ,0
Exp/Cntr(USF)=0,0
Exp/Cntr=0.3,0.1

Type RM Length L Ch R = 1 ,5903    ,226.9,233.2,240
XS GIS Cut Line= 4
1989571.74776035205324.2025230741989603.43253832205274.140573874
1989745.55683827205107.4178374021989805.97525047205033.825485696
#Sta/Elev= 30
       0 1851.74     9.8 1849.39    38.3 1838.09    42.2 1837.28    46.3 1836.94
    61.9 1838.41    79.1 1838.47    90.8 1839.37   114.6 1836.37   134.8 1827.93
   144.3 1825.49     150 1822.34   158.3 1816.17   172.31813.982   195.5 1813.22
   200.6 1813.29   207.2 1814.51   215.7 1815.01   234.3 1813.89   247.2 1816.55
   273.1  1817.8   288.6 1825.89   297.9 1832.64   302.9 1835.32   315.6 1845.24
   332.6 1856.51   337.6 1859.24   345.4 1861.54   348.8 1863.23   373.5 1877.69
#Mann= 4 ,-1 , 0
       0     .04       0  149.25      .1       0   172.3    .045       0
   207.2      .1       0
Bank Sta=172.3,207.2
XS Rating Curve= 0 ,0
Exp/Cntr(USF)=0,0
Exp/Cntr=0.3,0.1

Type RM Length L Ch R = 1 ,5670    ,227.2,228.7,229.9
XS GIS Cut Line= 4
1989700.03529131205458.6768195191989761.95579595205401.232495938
1989910.91299493205294.6392709811990011.89654929205217.062500748
#Sta/Elev= 30
       0 1840.85    13.8 1839.79    19.4  1838.6    33.6 1831.59    52.4 1825.29
    56.5 1825.15    70.5 1826.93    86.7 1826.92    93.8 1826.26    97.7 1825.12
   103.1 1822.39   115.2 1814.34   119.7 1812.54   124.4 1811.54   139.4 1810.91
   159.6 1812.28   171.7 1810.83   187.8 1810.82   191.81809.829   199.6 1807.77
   210.4 1806.96   220.1 1808.01   225.41810.484   228.2 1812.42   236.3 1819.88
   244.3  1822.3   252.4 1827.57   255.5 1829.01   321.6 1851.63     395 1880.14
#Mann= 4 ,-1 , 0
       0     .04       0  124.46      .1       0   191.8    .045       0
   225.4      .1       0
Bank Sta=191.8,225.4
XS Rating Curve= 0 ,0
Exp/Cntr(USF)=0,0
Exp/Cntr=0.3,0.1

Type RM Length L Ch R = 1 ,5441    ,229.5,227.4,224.6
XS GIS Cut Line= 4
1989849.30136615205612.0063378621989925.94537281205557.022593953
1990073.53599198205459.995427646 1990168.3532126 205380.75532184
#Sta/Elev= 30
       0 1824.09    32.3 1817.08    48.4 1814.85    76.6 1813.95   100.8  1814.3
   112.6 1813.52   116.8 1812.44   119.1 1811.27   134.2 1802.12   136.1 1801.11
     140 1800.13   152.3  1799.8     159 1800.42   161.8  1802.4   164.1  1804.4
   167.5  1806.2     176 1807.87   187.2 1808.07   249.4 1806.96   265.7 1807.55
   287.1  1809.9   291.7 1811.39     303 1816.43   318.3 1824.67   323.4 1827.01
   333.6 1830.91   345.3 1833.76   359.3 1838.41   380.2 1848.34   394.5 1853.88
#Mann= 6 ,-1 , 0
       0      .1       0      60     .04       0   134.2    .045       0
   161.8     .04       0  234.33      .1       0  380.95     .12       0
Bank Sta=134.2,161.8
XS Rating Curve= 0 ,0
Exp/Cntr(USF)=0,0
Exp/Cntr=0.3,0.1

Type RM Length L Ch R = 1 ,5214    ,156.2,151.6,144.3
XS GIS Cut Line= 4
1990019.41250748205789.6688683511990084.46863044205723.745330425
1990227.95951019205595.2868285531990300.84728626205515.587110795
#Sta/Elev= 30
       0 1813.48    19.4 1811.97    31.1 1810.38    63.3  1803.9    80.1 1801.85
    97.2 1801.14   111.1 1801.93   132.1 1801.38   136.7 1800.46     145 1797.09
     1531794.524   157.6 1793.12   164.7 1792.15   177.7 1791.94   189.3 1792.64
     1921794.559   197.1 1798.84   199.4 1799.63   257.5  1799.8     263 1800.59
   288.1 1812.72   297.8 1818.79   305.2 1823.98   317.9    1829   334.2 1837.46
   352.7 1848.72     361 1853.38   376.3 1863.44   385.3 1868.34   393.2 1871.77
#Mann= 5 ,-1 , 0
       0      .1       0      50     .06       0     153    .045       0
     192      .1       0  325.21     .12       0
Bank Sta=153,192
XS Rating Curve= 0 ,0
Exp/Cntr(USF)=0,0
Exp/Cntr=0.3,0.1

Type RM Length L Ch R = 1 ,5062    ,167.1,172.5,180
XS GIS Cut Line= 4
1990101.85914882205914.4301368891990200.62791405205839.904614032
 1990326.3532563205671.8152977531990376.04370202205608.002304302
#Sta/Elev= 30
       0 1813.49    24.8 1807.86    53.2 1802.76   123.4  1797.8   135.4 1796.53
   144.4 1794.45   151.8 1795.07   172.9 1794.74   178.1 1793.91   185.4 1790.72
   193.6 1788.11     201  1787.9   217.4 1788.27   223.4 1790.75   226.8 1792.51
   230.5 1793.11     251 1793.12   275.5 1794.21   279.6 1795.07   285.4 1797.61
   294.8 1803.12   304.2 1805.86   328.8 1819.29     337 1823.04   366.2  1833.9
   376.7 1835.87   386.9 1839.23   395.3 1844.45   404.7 1851.72   414.5 1858.42
#Mann= 4 ,-1 , 0
       0      .1       0      70     .04       0   185.4    .045       0
   223.4      .1       0
Bank Sta=185.4,223.4
XS Rating Curve= 0 ,0
Exp/Cntr(USF)=0,0
Exp/Cntr=0.3,0.1

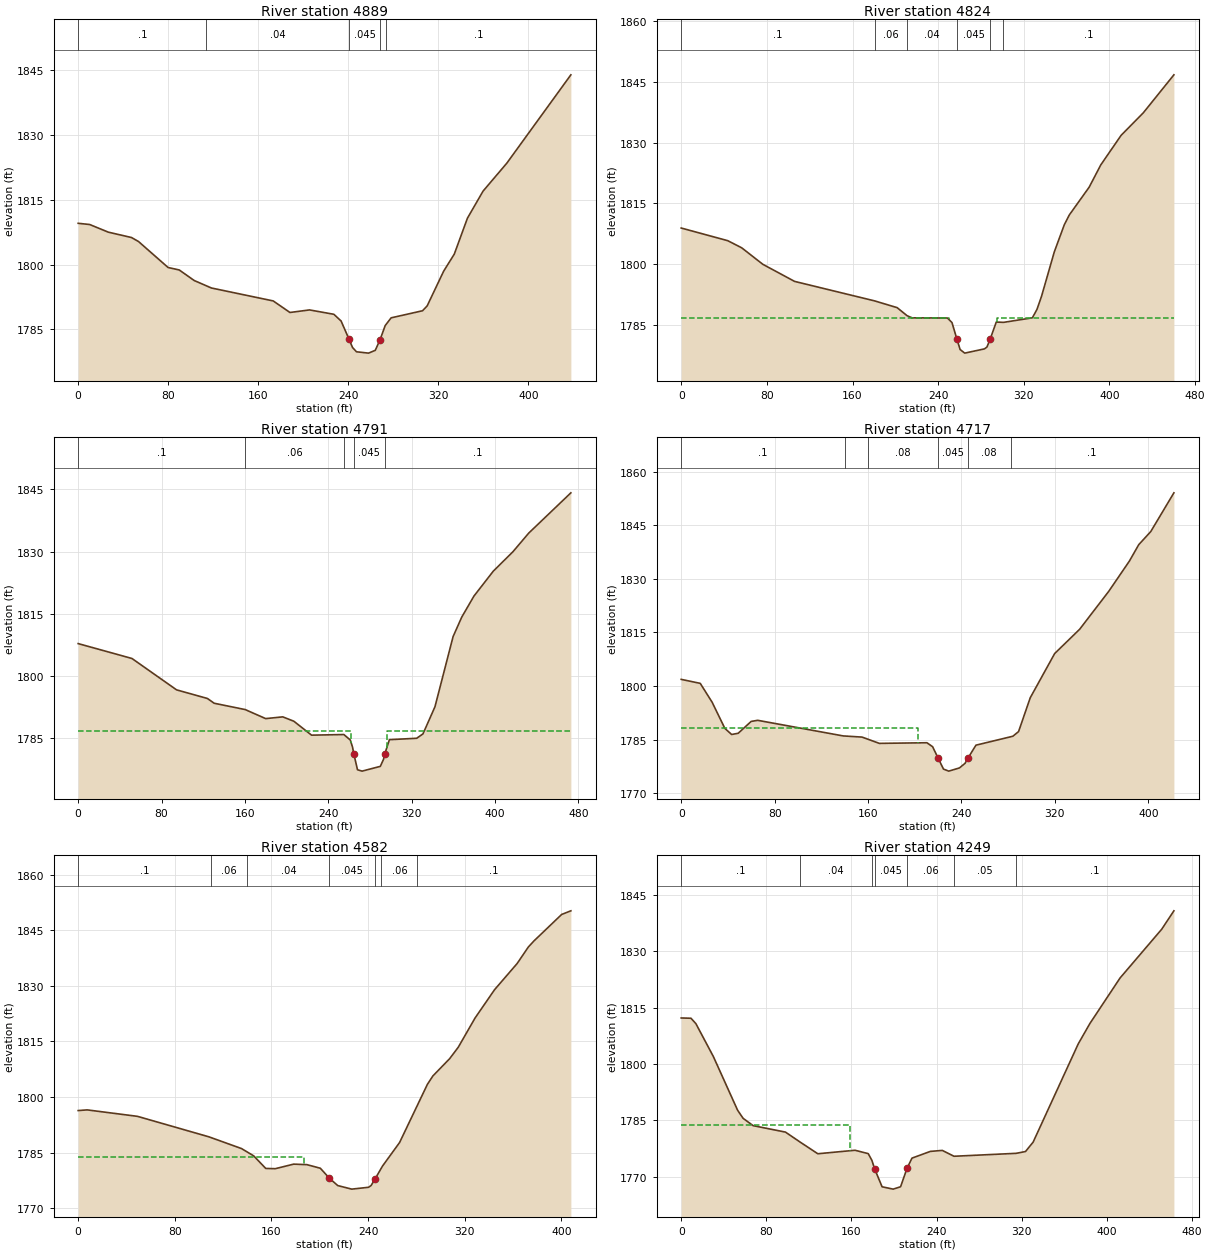
Type RM Length L Ch R = 1 ,4889    ,65.6,65.3,64.8
XS GIS Cut Line= 4
1990160.70094604205991.6209495241990263.49058517205976.562594746
1990467.11097644205819.4059169251990526.67402515205771.111553106
#Sta/Elev= 30
       0 1809.53    10.2 1809.25    26.8 1807.48    47.4 1806.24    53.6 1805.32
    79.9 1799.31    89.8 1798.74   103.1  1796.3   118.4 1794.57   173.3 1791.58
   188.2 1788.91   205.6  1789.5   227.2 1788.49   233.6 1786.95   240.61782.781
   243.8 1780.81   247.3 1779.82     258 1779.51     264 1780.16   268.21782.581
   272.8 1785.88   278.1 1787.67     306 1789.31   310.1 1790.43   324.8 1798.48
   334.2  1802.4   345.9 1810.72   359.8 1816.98   380.9 1823.44   437.8 1843.86
#Mann= 5 ,-1 , 0
       0      .1       0  113.89     .04       0   240.6    .045       0
   268.2     .04       0  273.89      .1       0
Bank Sta=240.6,268.2
XS Rating Curve= 0 ,0
Exp/Cntr(USF)=0,0
Exp/Cntr=0.5,0.3

Type RM Length L Ch R = 1 ,4824    ,33.7,33,31.5
XS GIS Cut Line= 4
1990176.82513469206010.5435946591990346.85195341205997.061291853
1990473.94387547205894.5678063181990568.73305602205810.996280269
#Sta/Elev= 30
       0 1808.92    43.4 1805.81    56.5 1804.05    76.3 1799.97   105.9 1795.77
   180.6 1790.97   201.7  1789.3   210.9 1787.33   215.6 1786.79   248.7 1786.74
   252.9 1785.63   257.6 1781.47   260.5 1778.99   264.8 1778.09   283.3 1779.14
   285.6  1779.6   288.71781.635   294.3 1785.75     301 1785.67     328 1786.79
   332.3 1788.87   336.5 1792.04   348.5 1803.05   357.8 1809.71   362.5 1812.14
   381.1 1819.01   391.9 1824.48   410.9 1831.77   431.6 1837.31   460.2 1846.68
#Mann= 6 ,-1 , 0
       0      .1       0   180.6     .06       0   210.9     .04       0
   257.6    .045       0   288.7     .04       0     301      .1       0
#XS Ineff= 2 , 0
             250 1786.81     295         1786.81
Permanent Ineff=
       F       F
Bank Sta=257.6,288.7
XS Rating Curve= 0 ,0
Exp/Cntr(USF)=0,0
Exp/Cntr=0.5,0.3

Type RM Length L Ch R = 1 ,4791    ,75.4,73.7,71.4
XS GIS Cut Line= 4
1990188.25439282206021.1769715191990391.94908705206006.627350503
 1990516.3078495205897.3009659321990595.66694668205831.789764904
#Sta/Elev= 30
       0 1807.84    51.6 1804.25    94.4 1796.69     124 1794.61   130.5 1793.46
   160.2 1791.94   179.9 1789.76   196.3 1790.18   206.9 1789.13   223.9 1785.77
   254.9 1785.92   261.1 1784.59   263.2 1782.91   264.51781.203     268 1777.43
   272.4  1777.1   289.9 1778.25     293 1779.98   294.31781.338   298.6 1784.68
   324.8 1785.02   330.8 1786.08   342.3 1792.61   359.7 1809.53     368 1814.22
   379.7 1819.29   398.3 1825.31     417 1829.95   432.3 1834.48   472.7 1844.18
#Mann= 5 ,-1 , 0
       0      .1       0   160.2     .06       0   254.9     .04       0
   264.5    .045       0   294.3      .1       0
#XS Ineff= 2 , 0
             262 1786.81     296         1786.81
Permanent Ineff=
       F       F
Bank Sta=264.5,294.3
XS Rating Curve= 0 ,0
Exp/Cntr(USF)=0,0
Exp/Cntr=0.5,0.3

Type RM Length L Ch R = 1 ,4717    ,132.7,135.2,135.6
XS GIS Cut Line= 4
1990321.11940484206153.8757836681990452.07859856206058.557383175
1990538.17312641205969.7296957111990643.07930406205882.864707843
#Sta/Elev= 30
       0 1801.86    16.3 1800.74    26.5 1795.45    37.4 1788.12    43.2 1786.42
    48.8 1786.76    59.9 1790.08    65.5 1790.39   138.7 1786.02   154.9 1785.69
   169.7 1783.93   210.4 1784.11   215.3 1782.99     220 1779.79   224.6 1776.73
   229.1 1776.16   238.3 1777.06   243.1 1778.36   245.4 1779.72   252.4 1783.43
     284 1785.93   288.9 1787.24   298.9 1796.72   319.8 1809.09   341.2 1815.89
   366.1 1826.51   383.8 1834.99   391.8 1839.58   402.1 1843.26   421.9  1854.1
#Mann= 6 ,-1 , 0
       0      .1       0     140     .06       0     160     .08       0
     220    .045       0   245.4     .08       0  281.98      .1       0
#XS Ineff= 2 , 0
           202.4 1788.31
Permanent Ineff=
       F       F
Bank Sta=220,245.4
XS Rating Curve= 0 ,0
Exp/Cntr(USF)=0,0
Exp/Cntr=0.3,0.1

Type RM Length L Ch R = 1 ,4582    ,330.2,332.9,333.3
XS GIS Cut Line= 4
1990447.65748412206246.5888619261990547.73918506206147.385070639
1990672.09794751206024.3928879961990736.88109028205959.031324313
#Sta/Elev= 30
       0 1796.34     7.5 1796.52    49.1 1794.78   108.2 1789.25   135.2 1786.08
   145.3 1784.11   155.3 1780.71   163.2 1780.64   178.4 1781.87   189.4 1781.73
   200.5 1780.76     2081778.059   214.9 1776.08   226.5 1775.12   240.4 1775.62
   242.5 1776.09   245.81777.873     252 1781.37   266.1 1787.71   289.1 1803.41
   293.7  1805.7   307.6 1810.38   314.7 1813.46   328.6 1821.35   344.8 1829.02
   363.4 1836.05   372.7 1840.52   377.4 1842.18   400.3 1849.32   407.9 1850.29
#Mann= 7 ,-1 , 0
       0      .1       0     110     .06       0     140     .04       0
     208    .045       0   245.8     .04       0  250.92     .06       0
  280.92      .1       0
#XS Ineff= 2 , 0
          186.66 1783.73
Permanent Ineff=
       F       F
Bank Sta=208,245.8
XS Rating Curve= 0 ,0
Exp/Cntr(USF)=0,0
Exp/Cntr=0.5,0.3

Type RM Length L Ch R = 1 ,4249    ,49,50.2,50.5
XS GIS Cut Line= 4
1990702.30860542206430.0017690641990819.68856668 206338.70624364
1990892.11729646206275.843572511 1991037.9451996 206113.09640989
#Sta/Elev= 30
       0 1812.27     9.2  1812.2    13.8 1810.76    30.2 1802.01      53 1787.69
    58.2 1785.52    67.6 1783.57      98 1781.85     112 1779.15   128.4 1776.08
   163.4 1777.01   175.8 1776.11   179.2 1774.34     182 1771.92   188.8 1767.28
   199.2 1766.65   206.2 1767.28   212.2 1772.15   216.9 1774.91   234.2 1776.71
   245.4 1776.97   256.4 1775.41   314.8 1776.19   323.6 1776.67   330.8 1779.18
   373.2 1805.37   384.2 1810.82   412.5 1822.93   451.6 1835.91   463.1 1840.83
#Mann= 7 ,-1 , 0
       0      .1       0     112     .04       0   179.2     .06       0
     182    .045       0   212.2     .06       0   256.4     .05       0
   314.8      .1       0
#XS Ineff= 3 ,-1
     159     162 1773.94       0     159 1783.81     232   463.1 1773.94
Permanent Ineff=
       F       F       F
Bank Sta=182,212.2
XS Rating Curve= 0 ,0
Exp/Cntr(USF)=0,0
Exp/Cntr=0.5,0.3

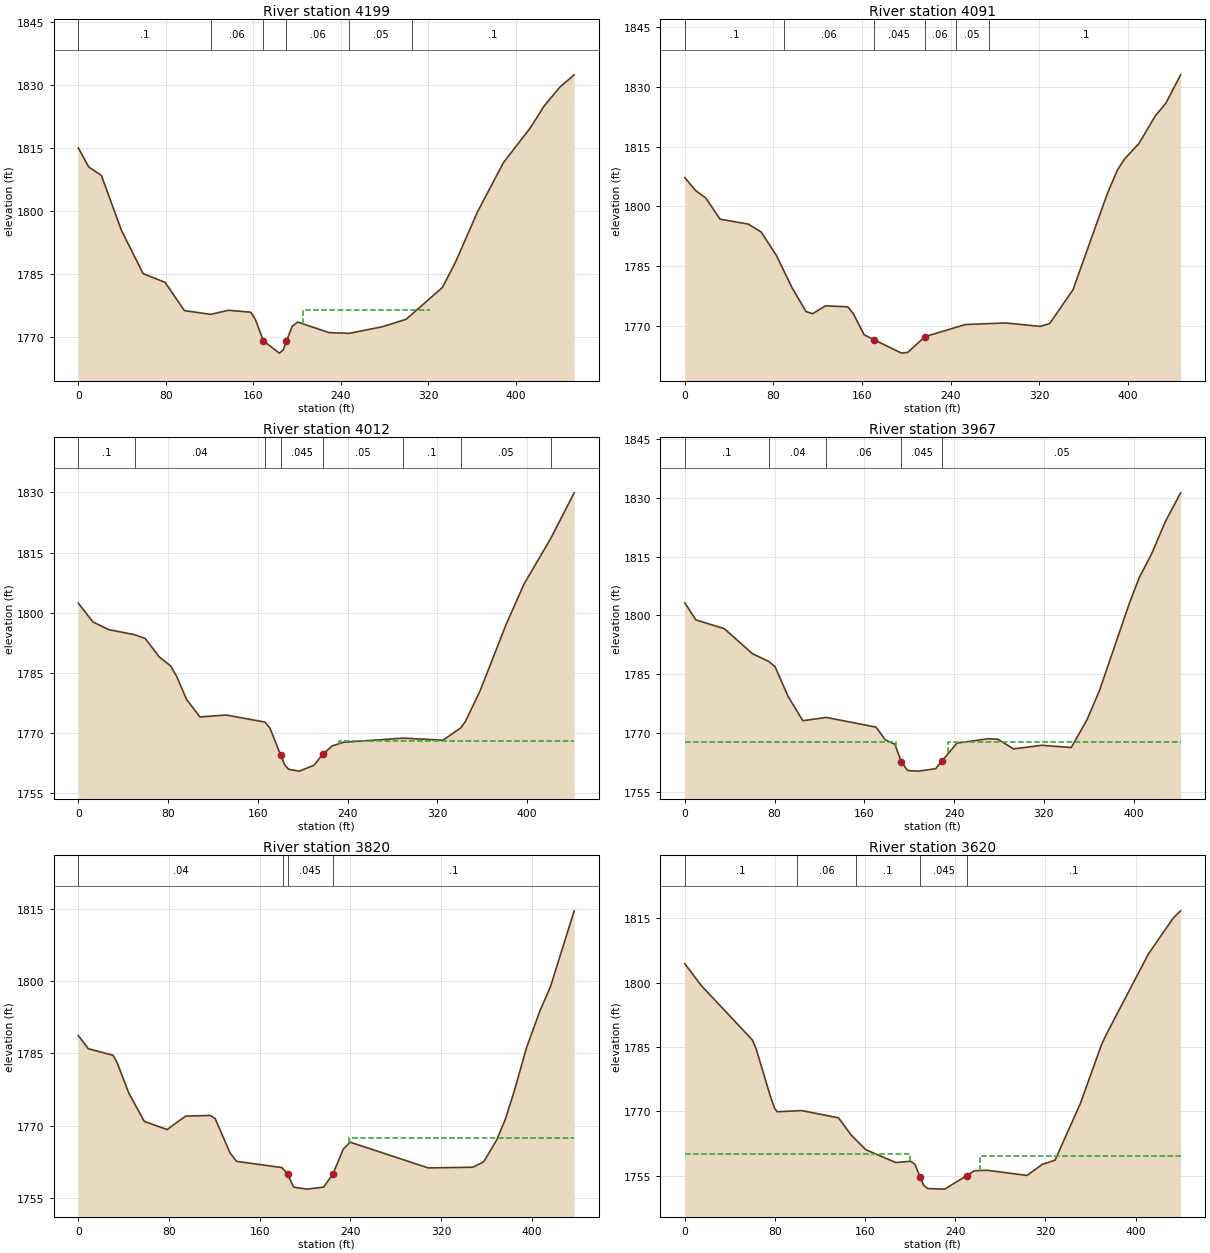
Type RM Length L Ch R = 1 ,4199    ,104.2,107.8,113.5
XS GIS Cut Line= 4
1990751.47930173206463.3103051871990853.85306186206371.504159011
1990959.07970701206286.7762109681991078.55259459206150.772483603
#Sta/Elev= 30
       0 1815.01     9.5 1810.46    21.1 1808.44    39.6 1795.28    59.3 1785.08
    79.4 1782.99      97 1776.29     121 1775.38   137.3 1776.36   157.8  1775.9
     162 1774.13   169.3  1769.1   183.9 1766.16   187.3 1766.89   190.3 1768.94
   195.7 1772.56   200.7 1773.55   229.4 1771.04   247.8 1770.87   278.1 1772.44
   299.9 1774.21   305.2 1775.43   333.1  1781.8   344.7 1787.62   365.4 1799.89
   388.8 1811.45   413.5 1819.77     426 1824.92   440.3  1829.4   453.6 1832.39
#Mann= 6 ,-1 , 0
       0      .1       0     121     .06       0   169.3    .045       0
   190.3     .06       0   247.8     .05       0   305.2      .1       0
#XS Ineff= 3 ,-1
       0  161.59 1771.64  197.15  200.15 1771.41   205.4  321.59  1776.4
Permanent Ineff=
       F       F       F
Bank Sta=169.3,190.3
XS Rating Curve= 0 ,0
Exp/Cntr(USF)=0,0
Exp/Cntr=0.5,0.3

Type RM Length L Ch R = 1 ,4091    ,85,79.7,74.8
XS GIS Cut Line= 4
1990836.31044459206527.2050280911990904.41651472206461.698426283
  1991072.505831206314.1078071111991148.78595968206209.623261099
#Sta/Elev= 30
       0 1807.19     9.8 1803.93    18.9 1802.11    31.8 1796.76    57.3 1795.52
    68.9 1793.54    82.7 1787.66    96.8 1779.55   109.4 1773.57   115.4 1773.02
     127    1775   147.1 1774.75   152.1 1773.04   161.9 1767.73   170.5 1766.53
   195.7 1763.12   201.4 1763.32   216.7 1767.25   253.4  1770.3   289.7  1770.7
   320.6 1769.83   329.4 1770.54   350.5 1779.08   381.5  1803.2   390.4 1809.02
     397 1811.88     410 1815.77   424.8 1822.72   434.3 1825.88   447.6    1833
#Mann= 6 ,-1 , 0
       0      .1       0      90     .06       0   170.5    .045       0
   216.7     .06       0   244.5     .05       0   274.5      .1       0
Bank Sta=170.5,216.7
XS Rating Curve= 0 ,0
Exp/Cntr(USF)=0,0
Exp/Cntr=0.5,0.3

Type RM Length L Ch R = 1 ,4012    ,48.1,45.1,43.1
XS GIS Cut Line= 4
1990905.08753534206572.7208926631991000.07710122206490.396602233
1991108.03690599 206367.40441959 1991196.3806987206242.949295559
#Sta/Elev= 30
       0 1802.34    13.1 1797.66      27 1795.76    50.3 1794.48    59.6 1793.54
    72.2 1788.93    82.2 1786.71    87.5 1784.18    96.4 1778.36   108.4 1773.96
   131.7 1774.44   166.4 1772.67   170.8 1771.17   180.5 1764.37   183.9 1762.04
   187.5 1760.88     197 1760.43   210.1  1761.9   217.7  1764.6   226.4 1766.74
   236.3 1767.63   289.8 1768.67   325.1 1768.14     341 1771.25     345  1772.8
     358 1780.38   381.5 1797.15   397.3 1807.12     421 1818.45     442  1829.9
#Mann= 8 ,-1 , 0
       0      .1       0    50.3     .04       0   166.4     .06       0
   180.5    .045       0   217.7     .05       0   289.8      .1       0
     341     .05       0     421      .1       0
#XS Ineff= 2 , 0
          170.34 1768.02  232.54         1768.07
Permanent Ineff=
       F       F
Bank Sta=180.5,217.7
XS Rating Curve= 0 ,0
Exp/Cntr(USF)=0,0
Exp/Cntr=0.5,0.3

Type RM Length L Ch R = 1 ,3967    ,144.5,146.6,149
XS GIS Cut Line= 4
1990944.38311393206604.2516385171991039.70791563206521.827937797
1991144.93456078206379.7036378541991236.18812661206274.604703418
#Sta/Elev= 30
       0 1803.22     9.9 1798.85    35.2 1796.62    60.3 1790.23    74.7 1788.28
    80.4 1786.95      92 1779.39   105.2 1773.14   126.2 1773.97   170.5  1771.5
   178.7 1768.27   187.2 1767.15   193.1 1762.61   198.6 1760.41   208.3 1760.27
   223.6 1760.89   229.3 1762.88   242.7 1767.43   270.3 1768.52   279.1 1768.41
     293 1765.95   318.3 1766.86   344.5  1766.3   358.4 1773.29   369.6 1780.78
   396.6 1803.34   405.3 1809.77   416.1 1815.68   428.4 1823.94     442 1831.28
#Mann= 5 ,-1 , 0
       0      .1       0    74.7     .04       0   126.2     .06       0
   193.1    .045       0   229.3     .05       0
#XS Ineff= 2 , 0
             188  1767.7     235          1767.7
Permanent Ineff=
       F       F
Bank Sta=193.1,229.3
XS Rating Curve= 0 ,0
Exp/Cntr(USF)=0,0
Exp/Cntr=0.5,0.3

Type RM Length L Ch R = 1 ,3820    ,205,199.8,193
XS GIS Cut Line= 4
  1991069.506878206691.7745213631991132.63534252206627.054582947
1991304.82439822206428.9005109111991342.39867045206353.230101556
#Sta/Elev= 30
       0  1788.7     8.8 1785.97    30.7  1784.6    34.3 1783.02    44.5 1776.79
    58.2 1770.89    78.4 1769.21    94.6    1772   116.4 1772.13   120.7 1771.49
   133.8 1764.38   139.6 1762.62   179.7 1761.32   184.61759.937     190 1757.27
   201.6 1756.86   216.4 1757.28   224.7 1760.04   233.7 1765.14   239.7  1766.6
   308.6 1761.26   348.1  1761.4   357.7 1762.55   369.1 1767.07   376.4 1771.17
   384.4 1777.05   395.3 1786.12   407.2 1793.82   416.4 1798.75   437.4 1814.55
#Mann= 4 ,-1 , 0
       0     .04       0  180.41      .1       0   184.6    .045       0
   224.7      .1       0
#XS Ineff= 2 , 0
                          239.13         1767.44
Permanent Ineff=
       F       F
Bank Sta=184.6,224.7
XS Rating Curve= 0 ,0
Exp/Cntr(USF)=0,0
Exp/Cntr=0.3,0.1

Type RM Length L Ch R = 1 ,3620    ,242.3,248.2,250.5
XS GIS Cut Line= 4
1991242.37317714206830.3399345421991311.65729725206755.513084819
1991411.41762318206579.2242896971991477.50398321206460.996397891
#Sta/Elev= 30
       0 1804.44    14.7 1799.32    59.9 1786.68    63.5 1784.44    75.7 1773.72
    79.7 1770.73      82 1769.92   103.8  1770.2   136.4  1768.5   147.7 1764.47
   160.7 1761.06   187.2 1758.09   200.5 1758.37   204.3 1757.64   208.81754.716
   211.8 1752.84   215.6 1752.01   230.6 1751.88   250.31755.048     257 1756.16
   268.3 1756.28   303.7 1755.07   317.1 1757.63   328.6 1758.65     351 1771.84
   369.9 1785.62   373.7 1787.76   411.2 1806.62   433.8 1815.21     440 1816.77
#Mann= 5 ,-1 , 0
       0      .1       0     100     .06       0  151.98      .1       0
   208.8    .045       0   250.3      .1       0
#XS Ineff= 2 , 0
          200.15 1760.08  261.62         1759.61
Permanent Ineff=
       F       F
Bank Sta=208.8,250.3
XS Rating Curve= 0 ,0
Exp/Cntr(USF)=0,0
Exp/Cntr=0.3,0.1

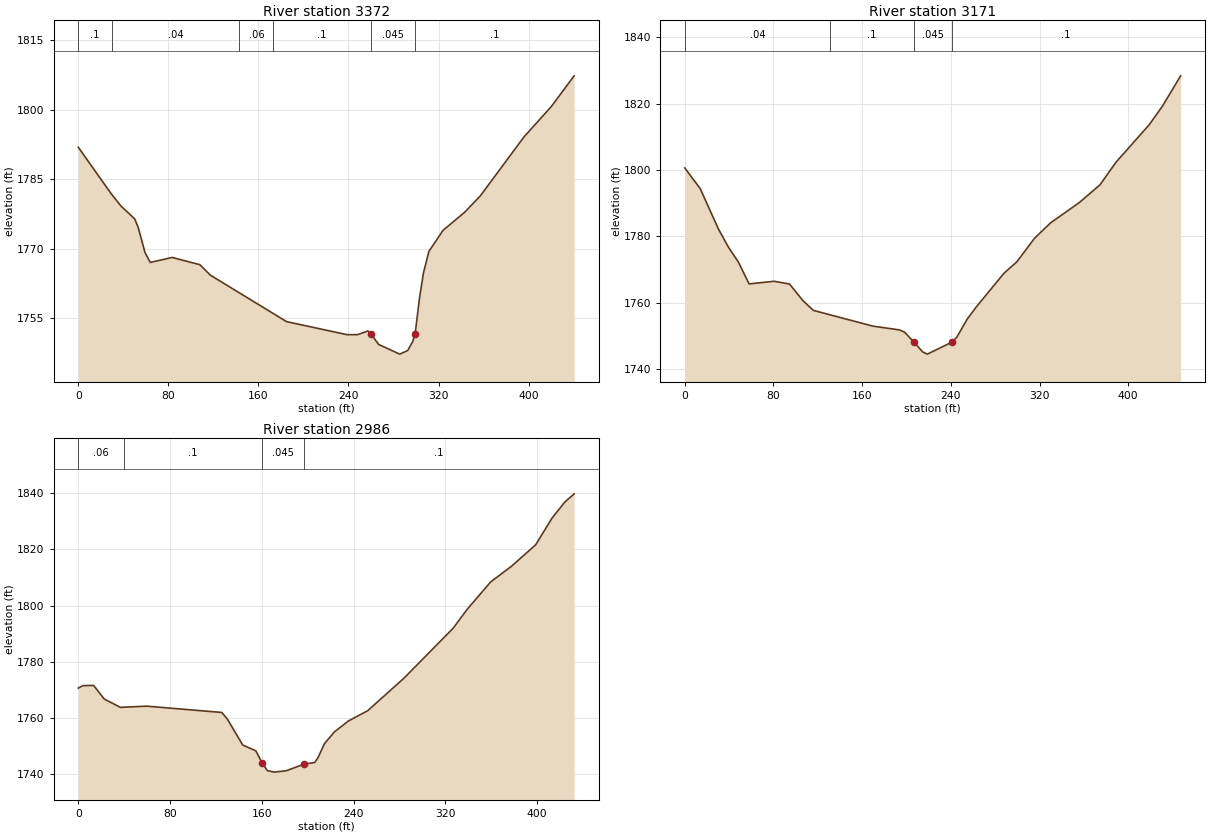
Type RM Length L Ch R = 1 ,3372    ,189.7,201.4,207.3
XS GIS Cut Line= 4
1991413.64287242206959.6154858611991505.71162987206863.472889583
1991658.76856827206665.318817547 1991676.1588303206611.084780015
#Sta/Elev= 30
       0 1791.89    28.8    1782    37.9 1779.22      50 1776.47    53.1  1774.7
    59.2 1769.21    63.9 1767.05    83.3 1768.13     108 1766.57   117.3 1764.31
     185 1754.29   238.8 1751.47   248.1 1751.48   257.2 1752.27   259.8  1751.7
   266.8 1749.37   285.5 1747.28   292.6 1748.05   297.2 1750.05     2991751.679
   299.6 1752.42   303.2 1759.52   306.6 1764.79   311.5 1769.46     324 1773.97
   343.1 1777.85   357.1  1781.4     396 1794.15   420.2 1800.67   440.5  1807.3
#Mann= 6 ,-1 , 0
       0      .1       0      30     .04       0  143.12     .06       0
  173.12      .1       0   259.8    .045       0     299      .1       0
Bank Sta=259.8,299
XS Rating Curve= 0 ,0
Exp/Cntr(USF)=0,0
Exp/Cntr=0.3,0.1

Type RM Length L Ch R = 1 ,3171    ,191.3,185.1,175.6
XS GIS Cut Line= 4
1991533.93553038207055.2157571171991620.50433367 206970.06611454
1991783.12733072206853.9068309331991857.22988301206752.015821537
#Sta/Elev= 30
       0 1800.62    13.9 1794.38    30.3 1782.22    39.2 1776.79    48.4 1772.18
      58 1765.62    80.7 1766.41    94.5 1765.57   106.7 1760.52     116 1757.62
   169.6 1752.88   193.6 1751.73   198.3 1751.05   206.71748.024   214.7 1745.06
   218.8 1744.42   240.6 1747.97   245.3 1749.47   254.7 1754.95   263.1 1758.73
   288.1 1768.89   299.4 1772.22   315.5 1779.38     330 1784.05   355.8 1790.14
   374.6 1795.53   388.9  1802.3   419.2 1813.75   431.3 1819.47   447.3 1828.42
#Mann= 4 ,-1 , 0
       0     .04       0  131.43      .1       0   206.7    .045       0
   240.6      .1       0
Bank Sta=206.7,240.6
XS Rating Curve= 0 ,0
Exp/Cntr(USF)=0,0
Exp/Cntr=0.3,0.1

Type RM Length L Ch R = 1 ,2986    ,244.3,244.5,243.2
XS GIS Cut Line= 4
1991706.81339958207181.3022577931991751.69599515207135.422271205
1991897.92003452 206950.933997241991976.86091329206844.131631846
#Sta/Elev= 30
       0 1770.69     3.9 1771.57    13.3 1771.65    22.6 1766.81    36.7 1763.85
    59.7 1764.28   125.1 1762.04   129.8 1759.79   143.4 1750.46   154.8 1748.42
   160.2 1744.19   164.8 1741.41   170.6 1740.84   181.2 1741.32     197 1743.69
   206.2 1744.27   209.2 1746.13   214.6 1750.93   223.4 1755.16   235.5 1759.01
   252.3 1762.65   283.9 1774.19   326.9 1791.98   339.1 1798.69   359.5 1808.38
   377.7 1813.98   398.8  1821.6   413.2 1831.14   424.2 1836.78   432.4 1839.72
#Mann= 4 ,-1 , 0
       0     .06       0      40      .1       0   160.2    .045       0
     197      .1       0
Bank Sta=160.2,197
XS Rating Curve= 0 ,0
Exp/Cntr(USF)=0,0
Exp/Cntr=0.3,0.1