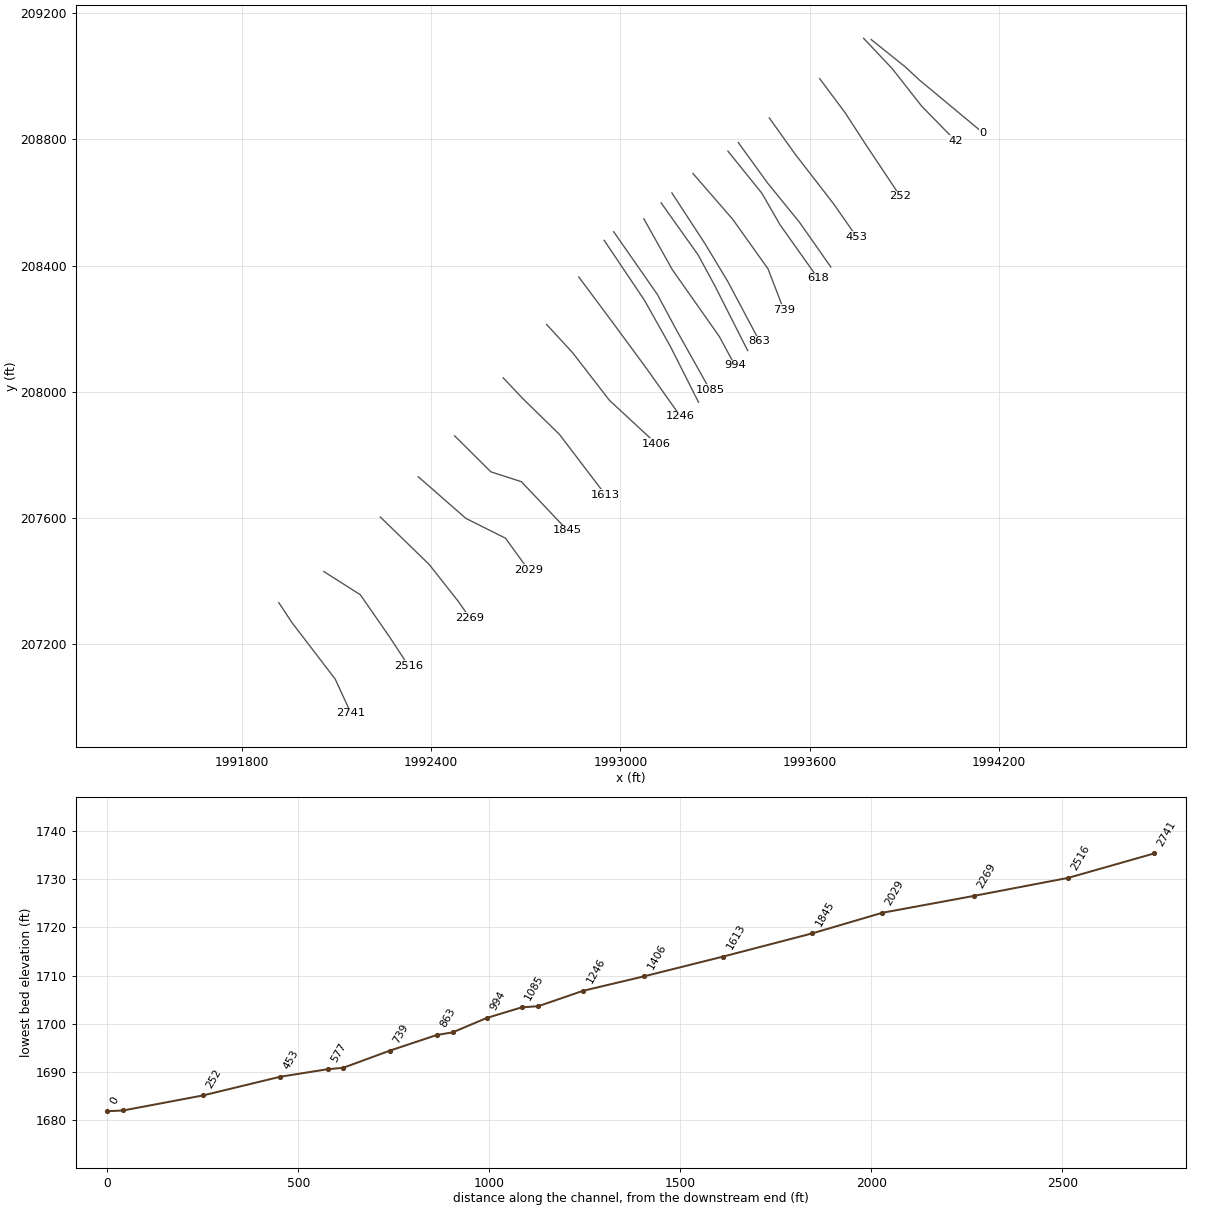
HEC-RAS study PIPESTCK2_A.prj: PIPESTCK2_A

--- PIPESTCK2_A.g01 (geometry) --- (continued)

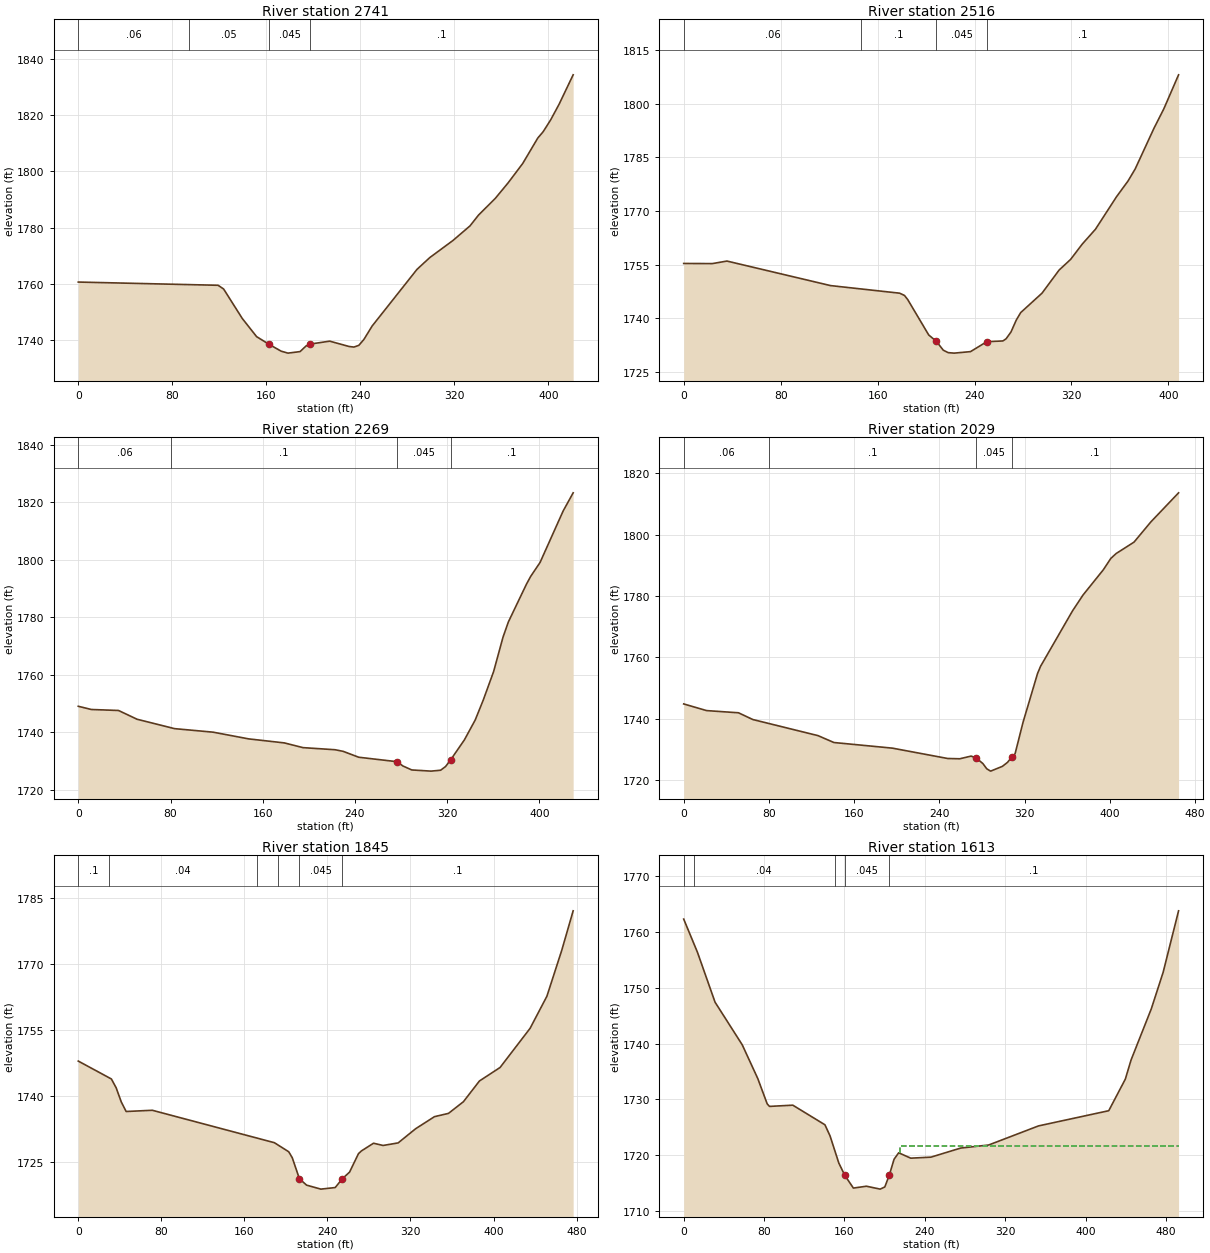
Type RM Length L Ch R = 1 ,2741    ,228,225.3,226.8
XS GIS Cut Line= 4
1991917.08939192207331.6526788441991958.04954603207269.347092305
1992096.07410655207088.9585577621992146.02562862206980.421917222
#Sta/Elev= 30
       0 1760.62     119 1759.47   123.7 1758.15   139.6 1747.64   151.8 1741.18
   162.3 1738.47   172.7 1736.01   178.5 1735.32   188.8 1735.87   193.9 1737.88
   197.41738.547     214 1739.58   230.5 1737.68   234.6 1737.48   238.8 1738.09
   243.1 1740.19   250.1 1744.96   288.3 1765.14   299.2 1769.34   318.9 1775.42
   333.4 1780.61   340.6 1784.43     355 1790.44   365.9 1795.96   378.3 1802.85
   391.1 1811.89   395.6  1814.1     402 1818.31   409.2 1823.89   421.2 1834.39
#Mann= 4 ,-1 , 0
       0     .06       0   94.56     .05       0   162.3    .045       0
   197.4      .1       0
Bank Sta=162.3,197.4
XS Rating Curve= 0 ,0
Exp/Cntr(USF)=0,0
Exp/Cntr=0.3,0.1

Type RM Length L Ch R = 1 ,2516    ,243.3,247,247.6
XS GIS Cut Line= 4
1992059.96111251207430.0964824091992175.33573537207356.808199962
1992268.26316226207222.8833788621992327.91492777 207132.03757084
#Sta/Elev= 30
       0 1755.32    23.6 1755.28    35.7 1755.99   121.2 1749.13   178.2 1747.01
   182.2 1746.38   184.9 1745.21   202.2 1735.33   208.51733.551   214.2 1731.08
   218.2 1730.39   223.2 1730.25   236.7 1730.67   250.21733.456   263.4 1733.65
   266.1 1734.27   270.1 1736.16   274.4 1739.45   278.1 1741.58   295.7 1747.01
   309.8 1753.47   319.3 1756.45   328.8 1760.69   339.8 1764.88   357.2 1773.98
   366.7 1778.38   372.6 1781.75     388 1793.05   396.2 1798.53   408.4 1808.06
#Mann= 4 ,-1 , 0
       0     .06       0  146.68      .1       0   208.5    .045       0
   250.2      .1       0
Bank Sta=208.5,250.2
XS Rating Curve= 0 ,0
Exp/Cntr(USF)=0,0
Exp/Cntr=0.3,0.1

Type RM Length L Ch R = 1 ,2269    ,225.6,239.7,251.5
XS GIS Cut Line= 4
1992239.12525843207602.9073683711992393.98850451207452.468786462
1992485.54935159207336.309502855 1992523.2897919207282.731556348
#Sta/Elev= 30
       0 1749.07    11.4 1747.95    34.9 1747.61      51 1744.56    83.5 1741.29
     117 1740.06   147.9 1737.72   178.7 1736.33     195 1734.68   222.8 1733.95
   229.8 1733.39   243.3 1731.34   276.8 1729.78   281.5 1728.32   289.3 1726.92
     306 1726.51   314.3 1726.82   318.6  1728.1   323.2 1730.54   334.9 1737.35
   344.3 1744.27   351.3 1751.22   360.3 1761.15   368.5 1773.18   373.1 1778.41
   388.8 1791.56   392.5 1794.29   400.6 1799.11   420.6    1817   429.3 1823.33
#Mann= 4 ,-1 , 0
       0     .06       0      80      .1       0   276.8    .045       0
   323.2      .1       0
Bank Sta=276.8,323.2
XS Rating Curve= 0 ,0
Exp/Cntr(USF)=0,0
Exp/Cntr=0.3,0.1

Type RM Length L Ch R = 1 ,2029    ,178.7,183.5,186.6
XS GIS Cut Line= 4
1992359.50160174207730.5082389131992510.14778812207598.692825827
1992635.87313038207535.8301546981992708.44977381207435.635850489
#Sta/Elev= 30
       0 1744.88    21.5 1742.71    51.4    1742    64.9  1739.8   126.1 1734.56
     141 1732.32   195.9 1730.49   247.8 1727.12   259.1 1727.03   269.8  1727.9
   274.5 1727.29   280.8 1725.48   284.5 1723.75   288.1 1723.01   299.1 1724.56
   303.9 1725.85     308 1727.61   310.1 1727.99   311.2 1728.88   318.5 1738.89
   332.1 1754.75   334.9 1757.09   364.9 1775.14   374.8 1780.32   393.9 1788.56
   400.9 1792.24   405.9 1793.83   422.7 1797.55   438.5 1804.13   464.5 1813.59
#Mann= 4 ,-1 , 0
       0     .06       0      80      .1       0   274.5    .045       0
     308      .1       0
Bank Sta=274.5,308
XS Rating Curve= 0 ,0
Exp/Cntr(USF)=0,0
Exp/Cntr=0.3,0.1

Type RM Length L Ch R = 1 ,1845    ,244.4,232.3,216.8
XS GIS Cut Line= 4
1992474.52686833207860.4001099431992589.40941693207746.283444998
1992686.43658324207714.8521094341992832.60849008207560.230959429
#Sta/Elev= 30
       0 1747.92    31.9 1743.84    36.5 1741.82    41.4 1738.62    46.1 1736.43
    71.3 1736.71   188.9 1729.32   202.7 1727.26   206.1 1725.91     213 1721.11
   219.9 1719.65   233.7 1718.74   247.5  1719.1   254.4 1721.12   261.3 1722.61
   269.9 1726.82   272.7 1727.44   284.4  1729.2   293.6 1728.69   308.1 1729.27
     325 1732.51   343.1 1735.25   356.6    1736     371 1738.66   386.4 1743.38
   406.3 1746.46   435.2 1755.38   451.4 1762.69   465.7 1773.15   476.7 1782.16
#Mann= 6 ,-1 , 0
       0      .1       0      30     .04       0  171.93    .035       0
  191.93      .1       0     213    .045       0   254.4      .1       0
Bank Sta=213,254.4
XS Rating Curve= 0 ,0
Exp/Cntr(USF)=0,0
Exp/Cntr=0.3,0.1

Type RM Length L Ch R = 1 ,1613    ,212,207.2,203.8
XS GIS Cut Line= 4
1992628.62858496208044.1947342981992690.53632266207978.602012213
1992806.69560627 207865.175888221992952.11630443207674.149882349
#Sta/Elev= 30
       0 1762.26    13.7 1756.32    31.2  1747.4    58.3 1739.76    73.8 1733.71
    83.1 1729.21    85.4 1728.75   108.6 1728.97   140.6 1725.46   145.7 1723.46
   154.4 1718.62   160.41716.401   168.9 1714.14   181.9 1714.47   195.6 1713.95
   200.2 1714.34   204.8 1716.53   209.4  1719.3     214 1720.45     226 1719.49
   246.1 1719.67   275.8  1721.3   303.5 1721.84   353.2 1725.26   423.1 1727.98
   439.6 1733.63   445.3 1737.05   465.5 1746.23   477.2 1752.72   492.6 1763.74
#Mann= 5 ,-1 , 0
       0     .12       0      10     .04       0  150.19      .1       0
   160.4    .045       0   204.8      .1       0
#XS Ineff= 2 , 0
                          215.14         1721.59
Permanent Ineff=
       F       F
Bank Sta=160.4,204.8
XS Rating Curve= 0 ,0
Exp/Cntr(USF)=0,0
Exp/Cntr=0.3,0.1

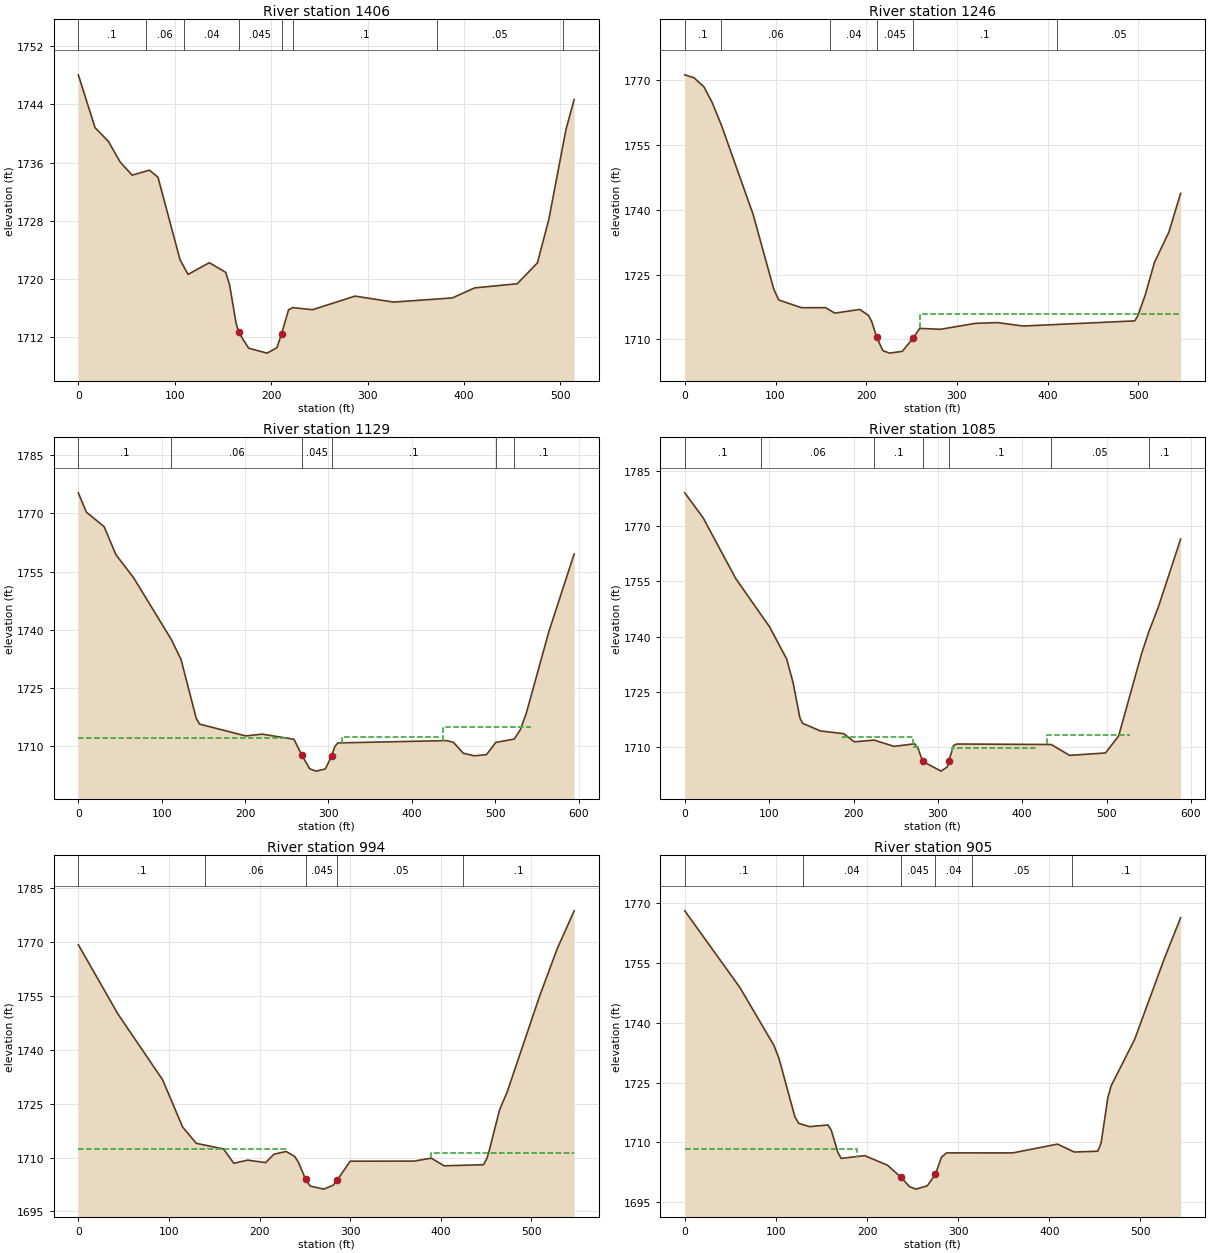
Type RM Length L Ch R = 1 ,1406    ,159.8,160.2,159.1
XS GIS Cut Line= 4
1992766.20738498208213.4717333411992849.05958029 208123.45947177
 1992965.2188639207973.1356929841993113.39935862207835.989915956
#Sta/Elev= 30
       0 1748.07    17.3 1740.83    31.2 1738.92    43.3 1736.11    55.8 1734.29
    73.7 1734.98    82.6 1734.01   105.5 1722.67   113.8 1720.66   135.8 1722.27
   152.8 1720.95   156.9 1719.21   163.5 1714.03   166.31712.692   176.6 1710.53
   195.7 1709.85     206  1710.6   210.71712.483     218 1715.79   222.3  1716.1
   242.9 1715.81   286.9 1717.68   326.9 1716.86   387.8 1717.43   411.1 1718.81
   455.2 1719.38   476.1 1722.25   487.9 1728.19   505.7 1740.56   514.2 1744.68
#Mann= 8 ,-1 , 0
       0      .1       0      70     .06       0     110     .04       0
   166.3    .045       0   210.7     .04       0  222.34      .1       0
  372.31     .05       0  502.31      .1       0
Bank Sta=166.3,210.7
XS Rating Curve= 0 ,0
Exp/Cntr(USF)=0,0
Exp/Cntr=0.3,0.1

Type RM Length L Ch R = 1 ,1246    ,120.2,116.9,113.1
XS GIS Cut Line= 4
1992868.19169759208363.9775178281992972.05176293208224.586377499
1993082.74472731208074.2625987131993190.23095294207922.469073978
#Sta/Elev= 30
       0 1771.26  10.1241770.586  21.1061768.487  30.2441764.818  40.4091759.572
  75.249 1738.98  97.9811721.697 103.4721719.154 128.4381717.355 155.2911717.364
 165.2611716.094 192.819 1716.95  202.531715.561  206.041714.136   211.61710.489
 218.263 1707.42  225.671706.838 239.7491707.253   251.51710.279 259.0061712.568
 281.9851712.358 320.1221713.726 344.5681713.906 372.921 1713.11 495.9211714.301
 499.3071715.466 507.6891720.412 517.6441727.836 533.5771734.853 546.5081743.824
#Mann= 6 ,-1 , 0
       0      .1       0      40     .06       0     160     .04       0
   211.6    .045       0   251.5      .1       0  410.51     .05       0
#XS Ineff= 2 , 0
                          259.07         1715.83
Permanent Ineff=
       F       F
Bank Sta=211.6,251.5
XS Rating Curve= 0 ,0
Exp/Cntr(USF)=0,0
Exp/Cntr=0.5,0.3

Type RM Length L Ch R = 1 ,1129    ,44.3,43.6,43.1
XS GIS Cut Line= 4
1992948.81990621208480.1368014351993077.27840808208288.815628435
1993159.27319651 208142.591589071993247.81487035207967.061604105
#Sta/Elev= 30
       01775.275   9.6121770.324  31.0061766.545  45.0771759.361   66.381753.394
 111.277 1737.62 123.0991732.452 141.4631717.223 145.4151715.755 200.7391712.718
 220.4981713.169 258.5921711.862     2681707.799 277.3991704.279 284.9041703.656
 296.2061704.206   303.71707.518  307.491709.931 311.2521710.913 441.8681711.514
 449.9711711.054 461.682 1708.26 474.9391707.589 489.6371707.913 500.6611711.039
 522.7451711.909 530.1031714.292 537.388 1718.62 564.2681739.499 594.687 1759.54
#Mann= 6 ,-1 , 0
       0      .1       0 111.277     .06       0     268    .045       0
   303.7      .1       0 500.661     .05       0 522.745      .1       0
#XS Ineff= 3 ,-1
       0     250 1712.16   316.8  430.87 1712.34  437.18  542.43 1714.92
Permanent Ineff=
       F       F       F
Bank Sta=268,303.7
XS Rating Curve= 0 ,0
Exp/Cntr(USF)=0,0
Exp/Cntr=0.5,0.3

Type RM Length L Ch R = 1 ,1085    ,88.4,91.1,94
XS GIS Cut Line= 4
1992978.88466197208507.4683975781993116.90922249208309.314325542
1993177.03873401208197.2547813561993284.14134993 208006.11780525
#Sta/Elev= 30
       01779.052  21.7581772.251  60.4871755.728  90.103 1746.02  100.471742.639
 120.7411733.879 128.4581727.382 136.4541717.874 139.5941716.414 160.8051714.325
 188.4321713.592 200.8691711.375 224.4171711.844 247.9311710.141 272.4181710.837
  276.421709.597   282.11706.045  303.78 1703.41 311.188 1704.56  312.931706.172
 318.6731710.386 322.3971710.777 434.4151710.649 456.1071707.693 498.6881708.344
 514.3471713.007 541.1931735.141 550.1061741.313 561.3281747.996 587.7581766.481
#Mann= 7 ,-1 , 0
       0      .1       0  90.103     .06       0 224.417      .1       0
   282.1    .045       0  312.93      .1       0 434.415     .05       0
 550.106      .1       0
#XS Ineff= 4 ,-1
   186.9  270.261712.732   270.8  277.71 1709.85  316.56  419.11 1709.76
  429.74  527.51 1713.17
Permanent Ineff=
       F       F       F       F
Bank Sta=282.1,312.93
XS Rating Curve= 0 ,0
Exp/Cntr(USF)=0,0
Exp/Cntr=0.5,0.3

Type RM Length L Ch R = 1 ,994     ,94.2,89.5,86.6
XS GIS Cut Line= 4
1993074.54524847208548.4657917921993164.73951574208387.209374549
1993313.69671472208175.3895044421993362.86920471208084.446834788
#Sta/Elev= 30
       01769.248  43.6971749.969  92.9861731.659 115.1211718.494 130.158 1713.97
 160.2311712.402 171.5081708.424 186.9541709.288 206.7181708.599 215.8831710.946
 229.3411711.706 238.8051710.304 242.8161708.703   250.81703.937 255.8071702.077
 270.8921701.221 281.1481702.298   285.91703.837 299.9871708.993 370.6321709.027
 389.4711709.837   403.61707.716 447.1131708.012 450.8931709.809 453.3131711.871
  464.781723.257 473.2211728.277 508.992 1754.95 528.3581768.099 547.1031778.684
#Mann= 5 ,-1 , 0
       0      .1       0     140     .06       0   250.8    .045       0
   285.9     .05       0  424.77      .1       0
#XS Ineff= 2 , 0
          229.39 1712.34  389.51         1711.39
Permanent Ineff=
       F       F
Bank Sta=250.8,285.9
XS Rating Curve= 0 ,0
Exp/Cntr(USF)=0,0
Exp/Cntr=0.3,0.1

Type RM Length L Ch R = 1 ,905     ,40.6,41.3,44.8
XS GIS Cut Line= 4
1993129.20844076208599.0292446571993246.73430417208433.673087992
1993300.03091665208335.279341878 1993403.6397455208130.673671462
#Sta/Elev= 30
       0 1768.14  60.5211748.856  97.8921734.296 103.5551730.918 120.7511716.444
 124.9221714.763 136.9981713.926 157.1231714.354 160.7491713.045 167.8071707.577
 171.5131705.954 197.3741706.644 222.468 1704.24     2371701.259 246.6711698.852
 253.7431698.233 266.0331699.063   274.91701.914 281.8331706.304 287.3241707.338
 359.9311707.332 409.0771709.541 427.464 1707.55 453.207 1707.76 456.8841709.832
 464.2391721.206 467.9171724.204 493.6591735.846 526.8261756.504 544.111  1766.4
#Mann= 6 ,-1 , 0
       0      .1       0     130     .04       0     237    .045       0
   274.9     .04       0  314.77     .05       0  424.77      .1       0
#XS Ineff= 2 , 0
          188.91 1708.31
Permanent Ineff=
       F       F
Bank Sta=237,274.9
XS Rating Curve= 0 ,0
Exp/Cntr(USF)=0,0
Exp/Cntr=0.3,0.1

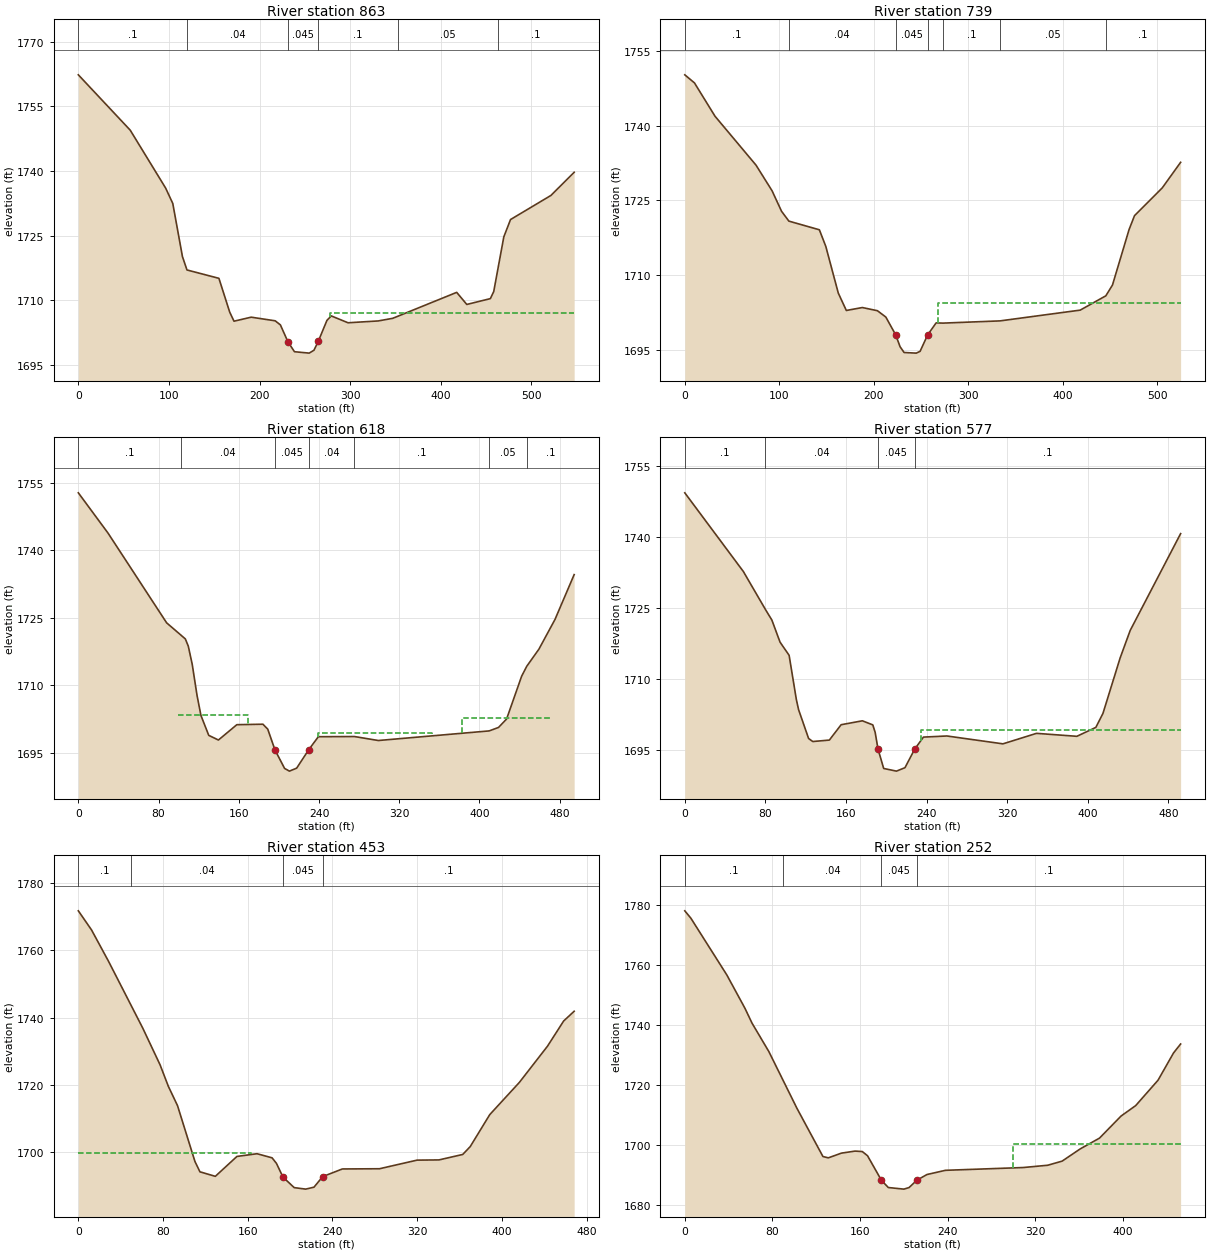
Type RM Length L Ch R = 1 ,863     ,120.3,123.9,124.7
XS GIS Cut Line= 4
1993163.37293593208630.4605802211993268.59958108208469.204162978
1993341.02831086208348.9451399491993441.64116559208159.610040604
#Sta/Elev= 30
       01762.354   57.261749.501  96.4361736.019 104.271 1732.46 114.9481720.105
 119.9411717.009 155.1991715.069 167.1021707.218 171.8431705.105 190.8081706.041
 217.3131705.198  223.071704.248   231.41700.311 238.5991698.015 254.8651697.688
 260.1121698.359   264.91700.438 274.4541705.304 279.2351706.336 297.742 1704.74
 331.1751705.169 347.0941705.777 417.6841711.806  428.831708.998 454.8371710.352
 458.5531711.987 469.6991724.705 477.1291728.732 521.713 1734.33 547.3461739.706
#Mann= 6 ,-1 , 0
       0      .1       0     120     .04       0   231.4    .045       0
   264.9      .1       0  352.94     .05       0  462.94      .1       0
#XS Ineff= 2 , 0
                          277.96         1707.08
Permanent Ineff=
       F       F
Bank Sta=231.4,264.9
XS Rating Curve= 0 ,0
Exp/Cntr(USF)=0,0
Exp/Cntr=0.3,0.1

Type RM Length L Ch R = 1 ,739     ,123.7,121.6,118.4
XS GIS Cut Line= 4
1993230.33534648208691.9566715421993356.06068874208547.099211985
1993468.12023293208389.9425341641993518.42004546208259.272369016
#Sta/Elev= 30
       01750.169  10.2541748.545  31.9751741.877  75.4171732.071  92.4081726.931
 102.4181722.832 110.1711720.863 142.4611719.126 149.2691715.792 162.4821706.445
  170.991702.963 187.9681703.551 203.9071702.913 212.7931701.647   223.21698.091
 227.9121695.691 232.1621694.541 245.0281694.418 249.0581694.777   257.11698.083
 266.0691700.479 273.2351700.431 333.6771700.876 418.5641703.033 445.6661705.898
 452.6971708.054 470.2741719.172 476.0161721.949 505.4291727.526 524.8431732.643
#Mann= 7 ,-1 , 0
       0      .1       0 110.171     .04       0   223.2    .045       0
   257.1     .04       0 273.235      .1       0 333.677     .05       0
 445.666      .1       0
#XS Ineff= 2 , 0
                           267.9         1704.47
Permanent Ineff=
       F       F
Bank Sta=223.2,257.1
XS Rating Curve= 0 ,0
Exp/Cntr(USF)=0,0
Exp/Cntr=0.5,0.3

Type RM Length L Ch R = 1 ,618     ,36.9,40.4,45.4
XS GIS Cut Line= 4
1993341.02831086208763.0188215141993448.98811563208629.094000414
1993506.38446753208529.3336744921993626.33432724208360.237691711
#Sta/Elev= 30
       01752.774  29.5831743.827  88.0631723.856 102.0621721.175 106.7281720.272
 109.6511718.674 113.5581714.651 118.3951707.684 122.293 1703.24 130.0611698.829
 139.6961697.793 158.0591701.203 184.073 1701.31 188.8791700.216   196.11695.583
 205.698 1691.47 210.5031690.875 217.7111691.538   229.71695.617 239.3361698.528
 275.3761698.568  299.151697.684  409.751699.822 419.0211700.595 427.0661702.468
 442.0451711.977 447.1791714.202 459.2461717.985 475.3361724.619 494.434 1734.58
#Mann= 7 ,-1 , 0
       0      .1       0 102.062     .04       0   196.1    .045       0
   229.7     .04       0 275.376      .1       0  409.75     .05       0
 447.179      .1       0
#XS Ineff= 4 ,-1
   98.95  169.42 1703.41  172.41  185.91 1699.37  239.13  352.32 1699.37
  382.31  472.26 1702.69
Permanent Ineff=
       F       F       F       F
Bank Sta=196.1,229.7
XS Rating Curve= 0 ,0
Exp/Cntr(USF)=0,0
Exp/Cntr=0.5,0.3

Type RM Length L Ch R = 1 ,577     ,124.7,124.1,123.3
XS GIS Cut Line= 4
1993373.82622623208790.3504176571993466.75365312208661.891915785
1993567.88055885208537.5331533351993667.40995469208395.568743766
#Sta/Elev= 30
       01749.357   58.11 1732.75  80.0661724.724  86.4551722.488  94.5541717.828
 103.5621715.044 110.7511705.701  112.961703.575 122.8991697.481 127.0581696.843
 143.5051697.147 155.1971700.391 176.2931701.218 186.6361700.356 188.979 1698.78
   191.81695.257 197.4361691.154 210.1221690.592  218.581691.321   228.21695.226
 236.9041697.776 260.2261698.012 315.8391696.353 349.1481698.568  389.191697.944
 408.0341699.824   415.11702.775 432.1941714.506 442.155  1720.3 492.2121740.741
#Mann= 4 ,-1 , 0
       0      .1       0  80.066     .04       0   191.8    .045       0
   228.2      .1       0
#XS Ineff= 2 , 0
             185 1699.34     234         1699.34
Permanent Ineff=
       F       F
Bank Sta=191.8,228.2
XS Rating Curve= 0 ,0
Exp/Cntr(USF)=0,0
Exp/Cntr=0.5,0.3

Type RM Length L Ch R = 1 ,453     ,203.3,201.8,199.3
XS GIS Cut Line= 4
1993472.21997235208868.2454666641993554.21476078208753.452762864
1993675.84036361208596.2960850421993749.33901654208490.891040149
#Sta/Elev= 30
       01771.758  12.4711766.079  28.5991756.711  60.8531736.886   77.211725.983
  85.0441719.575  93.6731713.853 110.1361697.253  114.841694.179 129.3941692.834
 149.7991698.745 168.7771699.554 182.9881698.332 187.1371696.678   193.31692.599
 203.8571689.479 214.741 1689.03 222.5661689.611   230.8 1692.75 249.3651695.026
 284.4281695.088 319.8911697.647 340.6041697.715 363.0621699.337 370.132 1701.67
   388.61711.185 416.598 1720.77 443.1841731.553 458.3661739.005 468.2931741.904
#Mann= 4 ,-1 , 0
       0      .1       0      50     .04       0   193.3    .045       0
   230.8      .1       0
#XS Ineff= 2 , 0
          163.42 1699.66
Permanent Ineff=
       T       F
Bank Sta=193.3,230.8
XS Rating Curve= 0 ,0
Exp/Cntr(USF)=0,0
Exp/Cntr=0.3,0.1

Type RM Length L Ch R = 1 ,252     ,208.1,209.2,211.8
XS GIS Cut Line= 4
1993632.10980978208992.6042291141993712.73801841 208884.64442435
1993775.60068954208787.6172580431993887.81166062208619.300801427
#Sta/Elev= 30
       01778.091   5.488 1775.66  38.3851756.674  54.8341745.607  61.4141740.563
  76.7661731.072 102.3621712.164 126.112 1696.05 131.0261695.606 142.9221697.177
 155.4131697.862 162.0671697.703 166.8111696.313   179.51688.117 185.7891685.697
 200.0231685.162 204.7671685.693   211.91688.154 221.1061690.041 237.9791691.444
 308.9881692.373 331.2591693.133 344.4761694.512 361.0361698.608 378.5761702.191
 398.291 1709.57 411.6171713.049 432.0121721.524 446.2071730.653 452.648 1733.62
#Mann= 4 ,-1 , 0
       0      .1       0      90     .04       0   179.5    .045       0
   211.9      .1       0
#XS Ineff= 2 , 0
                          299.85         1700.17
Permanent Ineff=
       F       F
Bank Sta=179.5,211.9
XS Rating Curve= 0 ,0
Exp/Cntr(USF)=0,0
Exp/Cntr=0.3,0.1

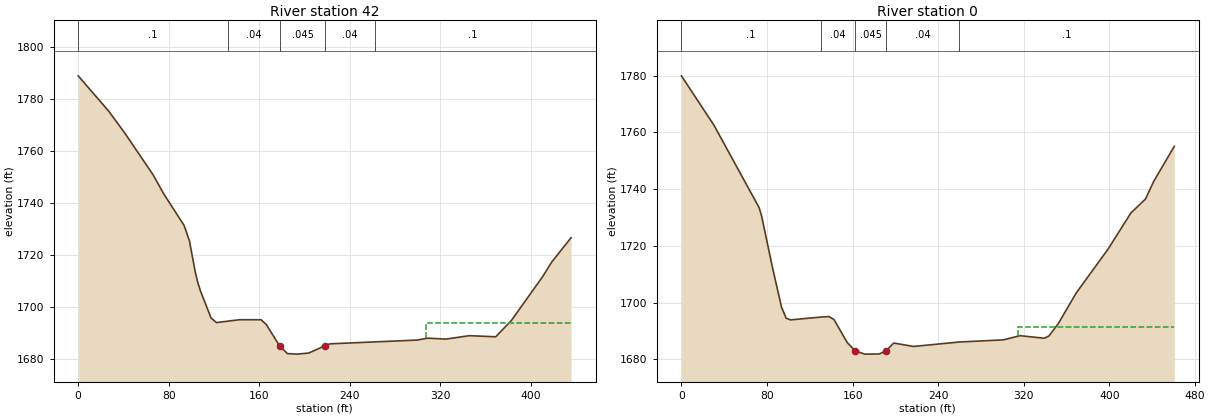
Type RM Length L Ch R = 1 ,42      ,42,41.9,42
XS GIS Cut Line= 4
1993771.34380427209120.6121954761993862.11203506209024.309316467
1993955.09412514208905.8678445811994061.83603378208796.629049189
#Sta/Elev= 30
       0 1788.99  26.8691775.482  40.9561767.143  66.3251750.872  75.6091743.662
  93.5731731.518  98.3571725.563  103.461713.661 105.7811709.461 108.101  1706.3
  117.491695.881 122.2731694.173 142.4111695.258  161.68 1695.26 166.3541693.352
     1781685.221 184.916 1682.25 193.4911682.043  203.741682.459   218.51685.337
 222.689    1686 299.249 1687.44 308.9941688.183 324.9461687.819 345.8261689.135
 369.0271688.698 382.947    1695 410.7881711.993 418.5131717.402 435.648 1726.79
#Mann= 5 ,-1 , 0
       0      .1       0  132.34     .04       0     178    .045       0
   218.5     .04       0  262.34      .1       0
#XS Ineff= 2 , 0
                          307.35         1694.03
Permanent Ineff=
       F       F
Bank Sta=178,218.5
XS Rating Curve= 0 ,0
Exp/Cntr(USF)=0,0
Exp/Cntr=0.3,0.1

Type RM Length L Ch R = 1 ,0       ,,,
XS GIS Cut Line= 4
1993795.24124382209116.6832291171993902.54957056209030.807022974
1993947.82847458208988.7728180741994148.83830052208821.762891856
#Sta/Elev= 30
       0  1779.9    30.5 1762.45    72.6 1733.49    74.9  1730.6    85.2 1712.19
    93.6 1698.38    97.8 1694.57     102 1693.94     1301694.928   137.9  1695.1
   142.6 1694.04     155 1685.93   162.4 1683.04   171.3 1681.88   184.8 1681.93
   191.3 1683.08   198.4 1685.79   216.9 1684.58  259.221686.137   300.8  1686.9
   316.4 1688.38     339 1687.48   343.3 1688.24   352.1 1692.58   368.9 1703.41
   398.6 1718.83     420  1731.6   433.6 1736.48   441.4 1742.77  460.56 1755.08
#Mann= 5 ,-1 , 0
       0      .1       0     130     .04       0   162.4    .045       0
   191.3     .04       0  259.22      .1       0
#XS Ineff= 2 , 0
                          314.09         1691.36
Permanent Ineff=
       F       F
Bank Sta=162.4,191.3
XS Rating Curve= 0 ,0
Exp/Cntr=0.3,0.1
LCMann Table=0

Chan Stop Cuts=-1
Use User Specified Reach Order=0
Composite Channel Slope=5